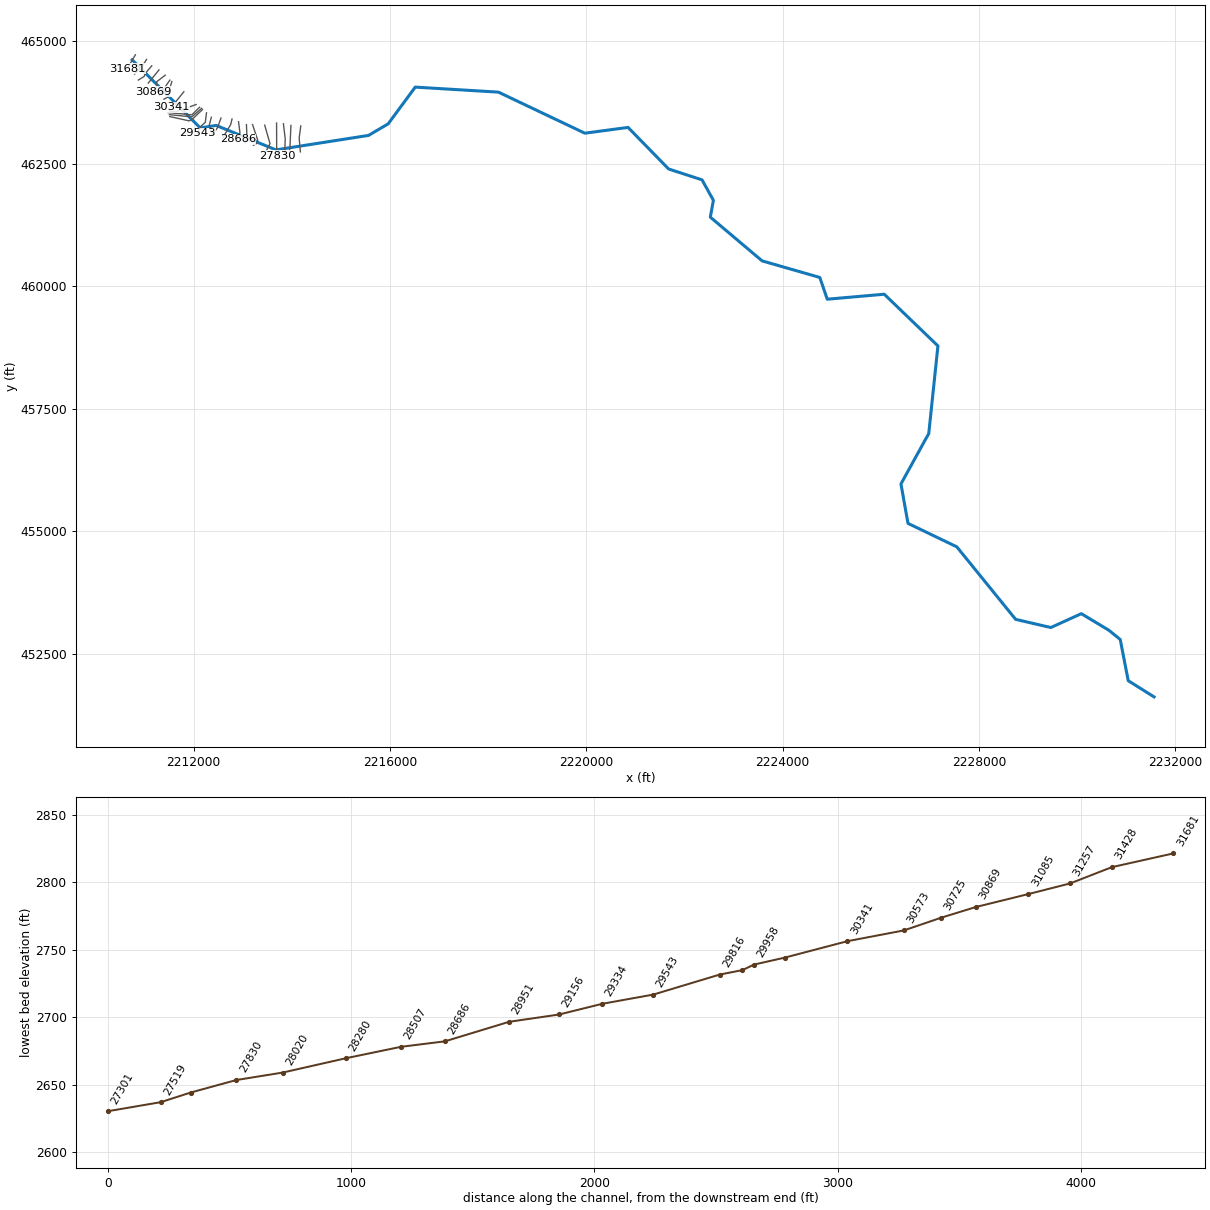
--- STONYCK.prj (project) ---

Proj Title=STONYCK
Current Plan=p01
Default Exp/Contr=0,0
English Units
Geom File=g01
Flow File=f01
Plan File=p01
Background Map Layer=Inundation Boundary (01pct Value_0)
BEGIN DESCRIPTION:
----------MODEL BY WOOD PLC 2021----------
Stream Name: Stony Creek
Flood Zone: Enhanced Approximate
Pocahontas County, WV
HEC-RAS Version: RAS 6.1
Vertical Datum: NAVD88
Projection: NAD 1983 StatePlane West Virginia S FIPS 4702 (US Feet)
Terrain: 1-meter LIDAR (FEMA Region III 3DEP collected 2016-2018)
Land Use: 2019 NLCD
Hydrologic Method:
WV SIR2010-5033 regression equations
END DESCRIPTION:
DSS File=dss
DSS Export Rating Curves= 0
DSS Export Rating Curve Sorted= 0
DSS Export Volume Flow Curves= 0
DXF OffsetX= 0
DXF OffsetY= 0
DXF ScaleX= 0
DXF ScaleY= 0

--- STONYCK.p01 (plan) ---

Plan Title=Floodplain
Program Version=6.10
Short Identifier=Floodplain
Geom File=g01
Flow File=f01
Subcritical Flow
K Sum by GR= 0
Std Step Tol= 0.01
Critical Tol= 0.01
Num of Std Step Trials= 20
Max Error Tol= 0.3
Flow Tol Ratio= 0.001
Split Flow NTrial= 30
Split Flow Tol= 0.02
Split Flow Ratio= 0.02
Log Output Level= 0
Friction Slope Method= 1
Unsteady Friction Slope Method= 2
Unsteady Bridges Friction Slope Method= 1
Parabolic Critical Depth
Global Vel Dist= 0 , 0 , 0
Global Log Level= 0
CheckData=True
Encroach Param=-1 ,0,0, 0
Computation Interval=0.1SEC
Output Interval=1SEC
Instantaneous Interval=Max Profile
Mapping Interval=1HOUR
Computation Time Step Use Courant=        0
Computation Time Step Use Time Series=    0
Computation Time Step Count To Double=0
Computation Time Step Max Doubling=0
Computation Time Step Max Halving=0
Computation Time Step Residence Courant=0
Run HTab= 0
Run UNet= 0
Run Sediment= 0
Run PostProcess= 0
Run WQNet= 0
Run RASMapper=-1
UNET Theta= 0
UNET Theta Warmup= 0
UNET ZTol= 0
UNET ZSATol= 0
UNET MxIter= 0
UNET Max Iter WO Improvement= 0
UNET MaxInSteps= 0
UNET DtIC= 0
UNET DtMin= 0
UNET MaxCRTS= 0
UNET WFStab= 0
UNET SFStab= 0
UNET WFX= 1
UNET SFX= 1
UNET Gravity=32.174
UNET 1D Methodology=Finite Difference
UNET DSS MLevel= 1
UNET Pardiso=0
UNET DZMax Abort= 0
UNET Use Existing IB Tables= 0
UNET Froude Reduction=False
UNET Froude Limit= 0
UNET Froude Power= 0
UNET D1 Cores= 0
UNET WindReference=Eulerian
UNET WindDragFormulation=Hsu (1988)
UNET D2 Coriolis=0
UNET D2 Cores= 0
UNET D2 Theta= 1
UNET D2 Theta Warmup= 1
UNET D2 Z Tol= 0.01
UNET D2 Volume Tol= 0.01
UNET D2 Max Iterations= 20
UNET D2 Equation= 0
UNET D2 RampUpFraction=0.1
UNET D2 TimeSlices= 1
UNET D2 Turbulence Formulation=Non-Conservative (original)
UNET D2 Eddy Viscosity=0.3
UNET D2 Transverse Eddy Viscosity=0.1
UNET D2 Smagorinsky Mixing=0
UNET D2 BCVolumeCheck=0
UNET D2 Cores=0
UNET D2 SolverType=PARDISO (Direct)
UNET D2 Minimum Iterations= 2147483647
UNET D2 Maximum Iterations= 2147483647
UNET D2 Restart Number= 10
UNET D2 Relaxation Coeff=1.3
UNET D2 SOR Precondition Iterations= 10
UNET D2 ILUT Maximum Fill= 8
UNET D2 ILUT Tolerance=1E-08
UNET D1D2 MaxIter= 0
UNET D1D2 ZTol=0.01
UNET D1D2 QTol=0.1
UNET D1D2 MinQTol=1
DSS File=dss
Write IC File= 0
Write IC File at Fixed DateTime=0
Write IC File at Sim End=0
Echo Input=False
Echo Parameters=False
Echo Output=False
Write Detailed= 0
HDF Write Warmup=0
HDF Write Time Slices=0
HDF Flush=0
HDF Compression= 1
HDF Chunk Size= 1
HDF Spatial Parts= 1
HDF Use Max Rows=0
HDF Fixed Rows= 1
Calibration Method= 0
Calibration Iterations= 20
Calibration Max Change=0.05
Calibration Tolerance=0.2
Calibration Maximum=1.5
Calibration Minimum=0.5
Calibration Optimization Method= 1
WQ AD Non Conservative
WQ ULTIMATE=-1
WQ Max Comp Step=1HOUR
WQ Output Interval=15MIN
WQ Output Selected Increments= 0
WQ Output face flow=0
WQ Output face velocity=0
WQ Output face area=0
WQ Output face dispersion=0
WQ Output cell volume=0
WQ Output cell surface area=0
WQ Output cell continuity=0
WQ Output cumulative cell continuity=0
WQ Output face conc=0
WQ Output face dconc_dx=0
WQ Output face courant=0
WQ Output face peclet=0
WQ Output face adv mass=0
WQ Output face disp mass=0
WQ Output cell mass=0
WQ Output cell source sink temp=0
WQ Output nsm pathways=0
WQ Output nsm derived pathways=0
WQ Create Restart=0
WQ Fixed Restart=0
WQ System Summary=0
WQ Write To DSS=0
Sorting and Armoring Iterations= 10
XS Update Threshold= 0.02
Bed Roughness Predictor= 0
Hydraulics Update Threshold= 0.02
Energy Slope Method= 1
Volume Change Method= 1
Sediment Retention Method= 0
Sediment TS Multiplier= 1
Warm Up Method= 0
XS Weighting Method= 0
Number of US Weighted Cross Sections= 1
Number of DS Weighted Cross Sections= 1
Upstream XS Weight=0
Main XS Weight=1
Downstream XS Weight=0
Number of DS XS's Weighted with US Boundary= 1
Upstream Boundary Weight= 1
Weight of XSs Associated with US Boundary= 0
Number of US XS's Weighted with DS Boundary= 1
Downstream Boundary Weight= 0.5
Weight of XSs Associated with DS Boundary= 0.5
Percentile Method= 0
Sediment Output Level= 3
Mass or Volume Output= 0
Output Increment Type= 1
Profile and TS Output Increment= 1
Transport Output Increment 1
XS Output Flag= 0
XS Output Increment= 10
Read HDF5 Sediment Hotstart= 0
Sediment Hotstart Type= 0
Write Gradation File= 0
Read Gradation Hotstart= 0
Write HDF5 File= 1
Write Binary Output= 1
Write DSS Sediment File= 0
DSS Sediment Output Type= 1
SV Curve= 0
Specific Gage Flag= 0
Subcell Erosion Methods= 0
Subcell Deposition Methods= 0
Advection Scheme= 1
Matrix Solver= 0
Implicit Weighting Factor= 1
Maximum Outer Loop Convergence Iterations= 5
Convergence Maximum Absolute= 0.001
Convergence RMSE= 0.0001
Grain Fractions Max Abs Error= 0.001
Max Subgrid Regions= 1
Max Subgrid Length Scale= 3.402823E+38
Initial Layer Thickness= 3.402823E+38
Min Layer Thickness= 3.402823E+38
Max Layer Thickness= 3.402823E+38
Number of Layers= 5

--- STONYCK.f01 (steady flow) ---

Flow Title=Flow
Program Version=6.10
Number of Profiles= 6
Profile Names=01pct,10pct,04pct,02pct,0_2pct,01plus
River Rch & RM=STONYCK,Main,31681
     770     412     545     654    1070    1140
River Rch & RM=STONYCK,Main,25577
    1060     575     756     904    1470    1570
River Rch & RM=STONYCK,Main,25313
    1210     655     860    1030    1660    1780
River Rch & RM=STONYCK,Main,21383
    1720     946    1230    1470    2350    2540
River Rch & RM=STONYCK,Main,16811
    1970    1090    1420    1680    2680    2910
River Rch & RM=STONYCK,Main,11404
    2330    1300    1680    1990    3160    3440
River Rch & RM=STONYCK,Main,9224
    2660    1490    1930    2280    3610    3930
River Rch & RM=STONYCK,Main,2128
    3680    2090    2680    3170    4960    5440
Boundary for River Rch & Prof#=STONYCK,Main            , 1
Up Type= 0
Dn Type= 3
Dn Slope=0.0077
Boundary for River Rch & Prof#=STONYCK,Main            , 2
Up Type= 0
Dn Type= 3
Dn Slope=0.0077
Boundary for River Rch & Prof#=STONYCK,Main            , 3
Up Type= 0
Dn Type= 3
Dn Slope=0.0077
Boundary for River Rch & Prof#=STONYCK,Main            , 4
Up Type= 0
Dn Type= 3
Dn Slope=0.0077
Boundary for River Rch & Prof#=STONYCK,Main            , 5
Up Type= 0
Dn Type= 3
Dn Slope=0.0077
Boundary for River Rch & Prof#=STONYCK,Main            , 6
Up Type= 0
Dn Type= 3
Dn Slope=0.0077
DSS Import GetInterval= 0
DSS Import GetPeak= 0
DSS Import FillOption= 0

--- STONYCK.g01 (geometry) ---

Geom Title=Geometry
Program Version=6.10

River Reach=STONYCK         ,Main
Reach XY= 30
     2210748.873      464624.7752212137.05677724463235.488703627
     2212460.848      463286.413     2213678.574       462787.03
     2215564.401       463082.51     2215964.627        463318.9
2216516.04037564464068.044962104     2218210.614      463965.366
     2219969.912      463127.688     2220850.691       463245.48
     2221677.463      462396.781     2222357.376      462175.327
     2222589.159      461757.844     2222526.493      461413.958
     2223580.797      460521.717     2224756.655      460183.183
     2224908.602      459739.064     2226069.394      459841.229
     2227162.766      458785.991     2226976.128      456998.502
     2226409.399      455968.876     2226553.405      455164.101
     2227547.468       454685.04     2228745.652      453205.226
     2229462.209      453038.273     2230083.542      453321.022
     2230643.118      452983.837      2230876.33      452794.384
     2231039.199      451952.844     2231565.564      451622.535

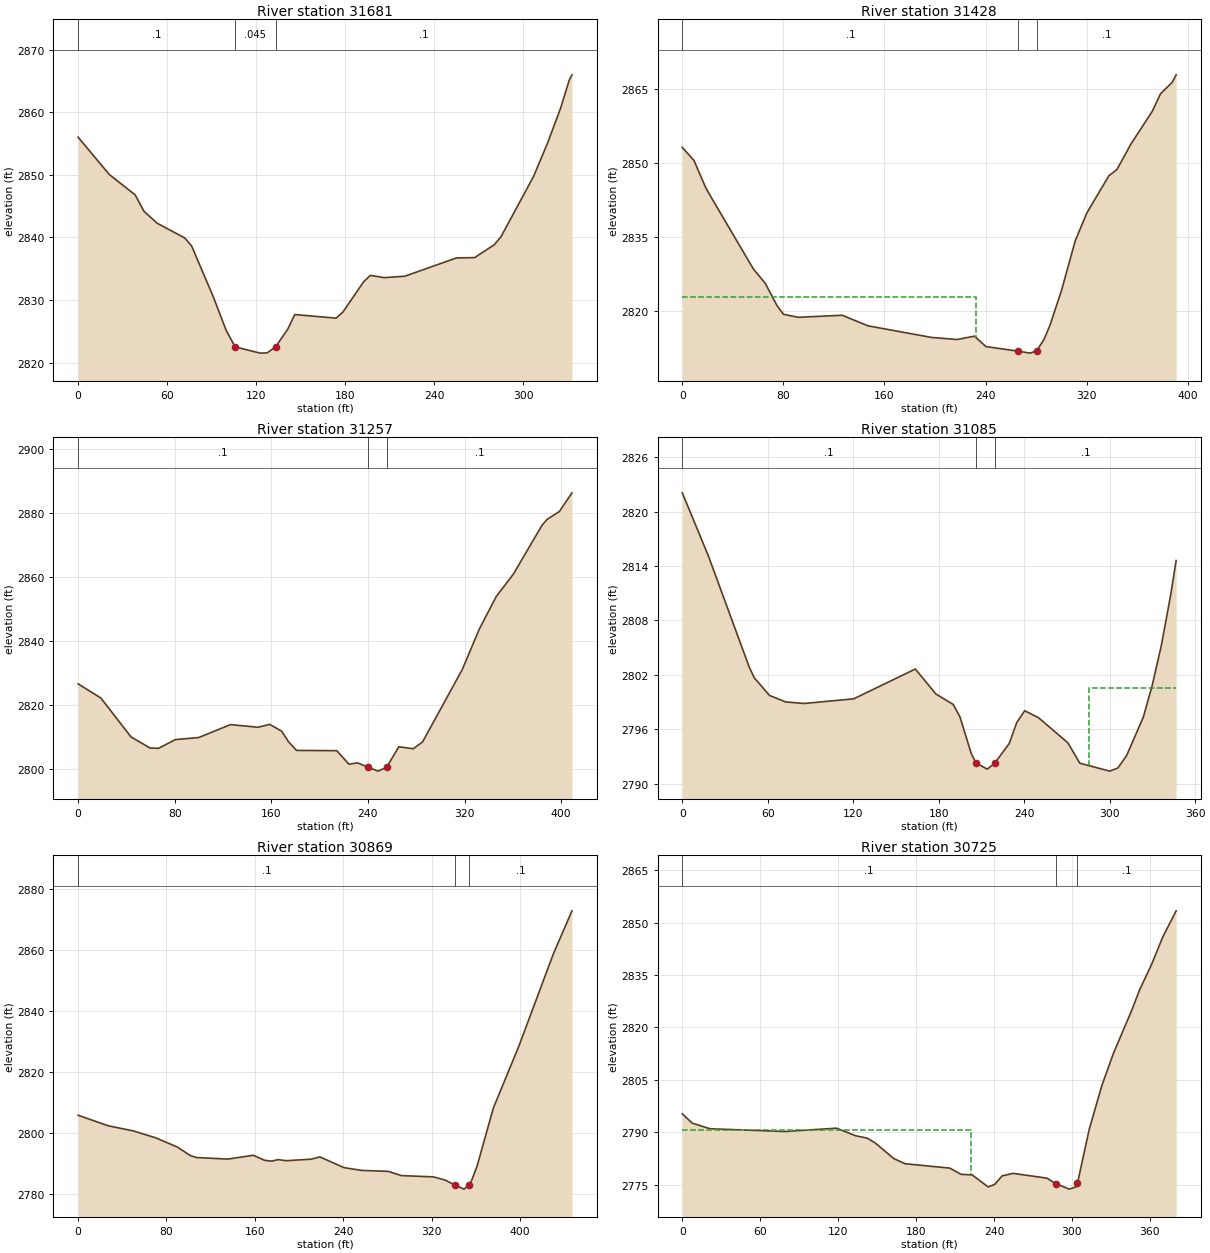
Type RM Length L Ch R = 1 ,31681   ,253,253,253
XS GIS Cut Line= 2
2210814.77974313464727.2685764382210647.13123896  464439.8305732
#Sta/Elev= 30
       0 2856.03      21 2850.07    38.5  2846.8    44.4 2844.18    53.4 2842.26
    71.9 2839.92    76.5 2838.64    91.2 2830.46    99.7 2825.19   105.8 2822.51
   122.8 2821.51   127.4 2821.55   133.12822.519   141.3 2825.35     146 2827.68
   173.8  2827.1   178.4 2828.06   192.3 2832.88   196.9 2833.94   206.2 2833.58
   220.1  2833.8     255 2836.73   267.2 2836.78   280.3 2838.81   284.9 2840.08
   306.9 2849.75   316.4 2855.11   325.2 2860.71     331 2865.18   332.8    2866
#Mann= 3 ,-1,0
       0      .1       0   105.8    .045       0   133.1      .1       0
Bank Sta=105.8,133.1
XS Rating Curve= 0 ,0
Exp/Cntr(USF)=0,0
Exp/Cntr=0.3,0.1

Type RM Length L Ch R = 1 ,31428   ,156.1,171.4,174.8
XS GIS Cut Line= 4
 2211042.5520139464633.0154511452210921.90752207 464438.05356945
2210868.98875231464408.6542529182210799.71483532464334.973411955
#Sta/Elev= 30
       0  2853.2     9.2 2850.57    18.6 2844.99    23.3 2842.86    56.3 2828.45
    65.7 2825.53    75.1 2820.95    80.1 2819.24    91.7 2818.62   126.6 2819.04
   146.9 2816.89   197.4 2814.52   217.4  2814.1   231.2 2814.78   240.4 2812.66
     2662811.726   275.3 2811.33   280.5 2811.82   286.2 2814.06     291 2816.99
   300.1 2824.04     311 2834.17   320.2 2839.86   337.7 2847.45     344  2848.7
   355.1 2853.88   372.1  2860.6   378.6 2864.15   387.9 2866.49   390.9 2867.98
#Mann= 3 ,-1,0
       0      .1       0     266    .045       0   280.5      .1       0
#XS Ineff= 2 , 0
          232.56 2822.73
Permanent Ineff=
       F       F
Bank Sta=266,280.5
XS Rating Curve= 0 ,0
Exp/Cntr(USF)=0,0
Exp/Cntr=0.3,0.1

Type RM Length L Ch R = 1 ,31257   ,174.2,171.6,167.5
XS GIS Cut Line= 4
2211148.28683737464502.8808244492211016.33171113464345.185210637
2210993.18504124464285.1753257322210874.81321902464212.261524698
#Sta/Elev= 30
       0 2826.59    18.9 2822.13    43.8 2809.97    59.6  2806.5    66.6  2806.4
    80.5 2809.13    99.9 2809.78   126.2 2813.82   148.9    2813   158.7 2813.89
   168.5 2811.79   174.3 2808.44   180.9 2805.74   214.2 2805.66   224.3 2801.42
   231.4 2801.85   240.3 2800.46   248.5 2799.26   255.62800.515   265.6 2806.88
   277.6 2806.27   285.3 2808.42   318.1 2831.03   332.2 2843.67   346.3 2853.93
   360.4  2860.9   384.3 2876.28   388.6 2878.12   398.6 2880.54     409 2886.38
#Mann= 3 ,-1,0
       0      .1       0   240.3    .045       0   255.6      .1       0
Bank Sta=240.3,255.6
XS Rating Curve= 0 ,0
Exp/Cntr(USF)=0,0
Exp/Cntr=0.3,0.1

Type RM Length L Ch R = 1 ,31085   ,216,216.4,216.6
XS GIS Cut Line= 2
2211295.94709185464419.4783621182211077.62116879464150.177664076
#Sta/Elev= 30
       0 2822.06    18.4 2815.07      47 2802.84    50.5 2801.67    61.2 2799.72
    72.6    2799    85.4 2798.83   120.3 2799.34   163.6 2802.63     178 2799.88
   190.2 2798.72   194.9 2797.37   202.9 2793.29   206.2 2792.28   214.1 2791.59
   219.2 2792.22   229.5 2794.41   234.8 2796.73   240.4 2798.03   250.1 2797.26
   270.7 2794.49   279.1 2792.24   300.1 2791.37   305.8 2791.72   311.9 2793.08
   323.6  2797.3   329.9 2800.82   336.3 2805.23   342.8 2810.74   346.7 2814.59
#Mann= 3 ,-1,0
       0      .1       0   206.2    .045       0   219.2      .1       0
#XS Ineff= 2 , 0
                          285.47          2800.5
Permanent Ineff=
       F       F
Bank Sta=206.2,219.2
XS Rating Curve= 0 ,0
Exp/Cntr(USF)=0,0
Exp/Cntr=0.3,0.1

Type RM Length L Ch R = 1 ,30869   ,143,143.8,143.8
XS GIS Cut Line= 4
2211423.96518945464311.6253915872211250.00314379464178.791015806
2211257.71870042464081.0606318192211181.35379763463975.570036122
#Sta/Elev= 30
       0  2805.9    27.3 2802.44    50.1 2800.76    70.2 2798.52    90.1 2795.46
   101.5 2792.72   107.2 2792.06   135.6 2791.56   158.6 2792.81   168.8 2791.16
   175.4 2790.89   180.9 2791.38   188.6 2791.03   211.1 2791.53   218.9 2792.27
   240.6 2788.78   256.6 2787.86   280.7 2787.55   292.7 2786.16   321.7 2785.74
   332.3  2784.7   341.5 2783.02   349.4 2781.74   353.7 2783.06   356.3 2784.59
   361.2 2789.26     376 2808.32   398.9 2828.36   430.3 2858.69   447.1 2872.72
#Mann= 3 ,-1,0
       0      .1       0   341.5    .045       0   353.7      .1       0
Bank Sta=341.5,353.7
XS Rating Curve= 0 ,0
Exp/Cntr(USF)=0,0
Exp/Cntr=0.3,0.1

Type RM Length L Ch R = 1 ,30725   ,144.4,151.4,155.8
XS GIS Cut Line= 2
2211517.15837953464210.7703211362211300.75603289463898.189153765
#Sta/Elev= 30
       0  2795.3     7.6 2792.63    21.4 2791.01      79 2790.22   118.7 2791.18
   133.3 2789.03   142.3 2788.33   148.5 2786.96   162.8 2782.49   171.5 2781.01
     206 2779.75   214.6 2777.97   223.2  2777.8   235.5 2774.36   240.5 2775.09
   246.2 2777.52   254.7 2778.25   280.7 2776.88   287.72775.276     298 2773.74
   303.6 2774.46   304.22775.366   313.3 2790.86     323 2803.36     332 2812.66
   346.1 2824.98   352.2 2830.87   361.2 2837.94   369.8  2845.8   380.2 2853.36
#Mann= 3 ,-1,0
       0      .1       0   287.7    .045       0   304.2      .1       0
#XS Ineff= 2 , 0
          221.93 2790.73
Permanent Ineff=
       F       F
Bank Sta=287.7,304.2
XS Rating Curve= 0 ,0
Exp/Cntr(USF)=0,0
Exp/Cntr=0.3,0.1

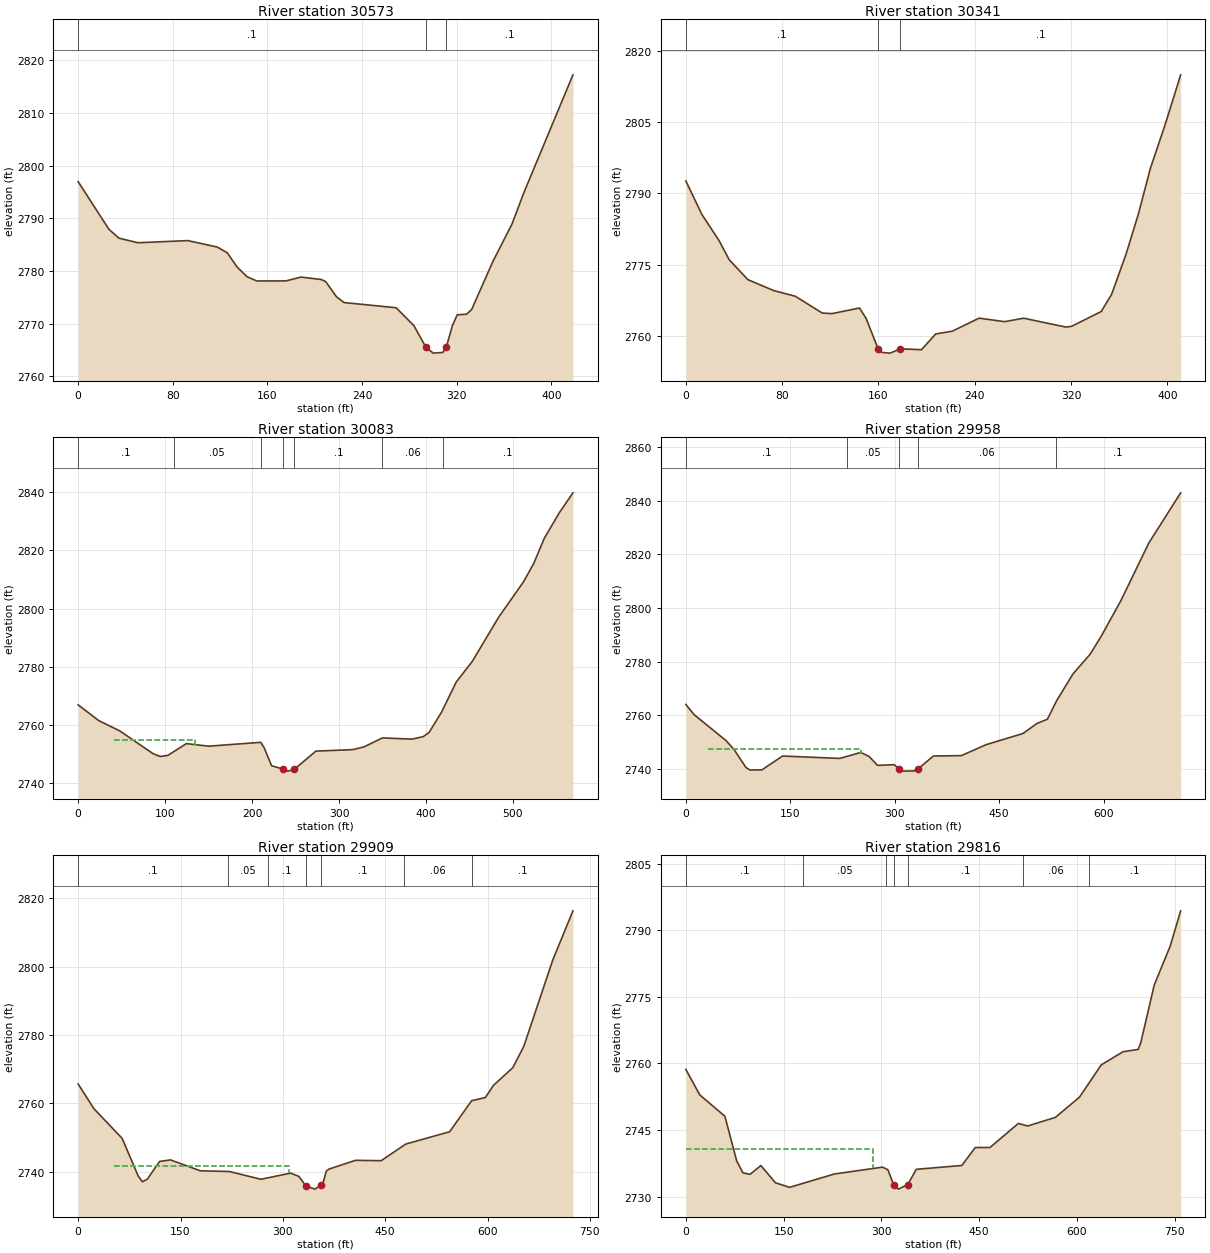
Type RM Length L Ch R = 1 ,30573   ,241.2,232.3,227.5
XS GIS Cut Line= 4
2211557.70150438464182.1754970072211483.18441084463925.034931067
2211471.11581331463860.6939707332211395.67481514 463821.25890351
#Sta/Elev= 30
       0 2796.97      26 2787.93    34.4 2786.25    50.5 2785.37    92.7 2785.78
   117.6 2784.56     126 2783.47   134.4 2780.76   142.6 2778.95     151 2778.11
   175.9 2778.13   188.4 2778.85   205.5 2778.39   209.3 2777.98   218.4 2775.11
   224.8 2774.01   268.8 2773.03   283.9 2769.61   293.8  2765.6   300.1 2764.41
   308.3 2764.54   311.3 2765.62   316.4 2769.64   320.5 2771.69   328.4  2771.8
   332.7 2772.71   350.7 2781.86   366.7 2788.89   377.1 2795.05   418.3 2817.26
#Mann= 3 ,-1,0
       0      .1       0   293.8    .045       0   311.3      .1       0
Bank Sta=293.8,311.3
XS Rating Curve= 0 ,0
Exp/Cntr(USF)=0,0
Exp/Cntr=0.3,0.1

Type RM Length L Ch R = 1 ,30341   ,265.3,257.9,251.8
XS GIS Cut Line= 2
2211802.80947709463973.2086339342211544.08844933463653.894949113
#Sta/Elev= 30
       0 2792.59    13.3 2785.56    27.5  2780.1      36 2776.05    51.5 2771.86
      73 2769.56    90.9 2768.37   113.3 2764.84   121.3 2764.72   144.2  2765.9
   149.8 2763.68   159.6 2757.35     163 2756.56   169.7 2756.42   178.2 2757.33
   195.7 2757.14   207.5 2760.45   221.4 2761.04   243.6 2763.77   264.7 2763.03
   280.6 2763.76   315.5  2761.9   320.4 2762.05     345 2765.16   353.6 2768.75
   365.6 2777.19   375.9 2785.66   385.8 2795.21   398.1 2804.43     411  2814.9
#Mann= 3 ,-1,0
       0      .1       0   159.6    .045       0   178.2      .1       0
Bank Sta=159.6,178.2
XS Rating Curve= 0 ,0
Exp/Cntr(USF)=0,0
Exp/Cntr=0.3,0.1

Type RM Length L Ch R = 1 ,30083   ,134.8,125.3,118.7
BEGIN DESCRIPTION:
structure xs 4
END DESCRIPTION:
XS GIS Cut Line= 3
2212053.21169689463713.241110682 2211637.4289229 463562.35911435
 2211511.4081646463576.075659471
#Sta/Elev= 30
       0 2766.95    23.6 2761.56    47.9 2758.01    86.2 2750.19    94.5 2749.23
   103.2 2749.62   124.5 2753.65     150 2752.77     210 2754.09   213.9 2752.24
   222.5 2746.04   235.4 2744.96   241.3 2744.21   248.7 2744.85   273.4 2751.07
     316 2751.59   328.8 2752.53     350 2755.61   384.1 2755.19   396.8 2756.03
   403.6 2757.46   418.1 2764.51   434.8 2774.76   453.3 2781.86   483.8 2797.09
     512 2809.05     524 2815.46   536.1 2824.06   553.4 2832.86   569.1 2839.69
#Mann= 7 ,-1,0
       0      .1       0     110     .05       0     210      .1       0
   235.4    .045       0   248.7      .1       0     350     .06       0
     420      .1       0
#XS Ineff= 1 ,-1
   41.58   134.2 2754.74
Permanent Ineff=
       F
Bank Sta=235.4,248.7
XS Rating Curve= 0 ,0
Exp/Cntr(USF)=0,0
Exp/Cntr=0.5,0.3

Type RM Length L Ch R = 1 ,29958   ,46.6,48.8,49
BEGIN DESCRIPTION:
structure xs 3; 20.8 ft between structure and xs
END DESCRIPTION:
XS GIS Cut Line= 3
2212124.26672253463657.4892360582211965.89881567463502.859481452
2211478.65589475463547.833381769
#Sta/Elev= 30
       0 2763.97    11.9 2760.17    57.7 2750.51    69.2 2747.17    86.3 2740.47
    92.1 2739.52   109.2 2739.58   138.9 2744.75   220.9 2743.85   251.2 2746.07
   263.2 2744.59   275.3 2741.26   299.4 2741.52     306 2739.83   311.4 2739.11
   327.5 2739.19   333.6 2739.98   355.6 2744.75   395.8  2744.9     431 2748.96
   484.2 2753.16   504.3  2756.9   519.3 2758.49   532.4 2765.32     556 2775.38
   580.6 2782.72   596.7 2789.49   624.8 2802.72   664.9 2824.21   710.7 2842.97
#Mann= 5 ,-1,0
       0      .1       0  231.34     .05       0     306    .045       0
   333.6     .06       0  531.34      .1       0
#XS Ineff= 3 ,-1
      32  251.94 2747.51  251.94     285  2736.5     354   710.7  2738.9
Permanent Ineff=
       F       F       F
Bank Sta=306,333.6
XS Rating Curve= 0 ,0
Exp/Cntr(USF)=0,0
Exp/Cntr=0.5,0.3

Type RM Length L Ch R = 1 ,29909   ,83.4,92.6,99.2
BEGIN DESCRIPTION:
structure xs 2; 12.8 ft between structure and xs
END DESCRIPTION:
XS GIS Cut Line= 3
2212166.83825993463635.1530859672211963.56167032463460.790865265
2211508.41816581463505.730656859
#Sta/Elev= 30
       0 2765.69    23.1 2758.46    64.5 2749.77    87.8 2738.88    94.1  2737.1
   101.3 2737.85   119.4 2743.04   135.3 2743.49   179.2  2740.3   221.7  2740.1
   267.8 2737.83   311.4 2739.62   323.5 2738.67   333.5 2735.95     347 2734.95
   355.4 2736.03   359.6  2737.2   363.7  2740.2   367.7 2740.81   406.6 2743.37
   444.1 2743.26   480.2 2748.12   544.5 2751.72   576.7  2760.8   596.8 2761.71
   608.8  2765.3     637 2770.43   653.1 2776.64   695.6 2801.89   725.2 2816.28
#Mann= 7 ,-1,0
       0      .1       0     220     .05       0  277.81      .1       0
   333.5    .045       0   355.4      .1       0  477.81     .06       0
  577.81      .1       0
#XS Ineff= 3 ,-1
   53.18  309.63 2741.83  309.63     329  2736.5     360   725.2  2737.4
Permanent Ineff=
       F       F       F
Bank Sta=333.5,355.4
XS Rating Curve= 0 ,0
Exp/Cntr(USF)=0,0
Exp/Cntr=0.5,0.3

Type RM Length L Ch R = 1 ,29816   ,261.4,273.2,283.3
BEGIN DESCRIPTION:
structure xs 1
END DESCRIPTION:
XS GIS Cut Line= 4
2212179.64347994463607.8491003242211964.35103617  463403.5830418
 2211908.2227972463379.2697839012211516.55186903463467.200582573
#Sta/Elev= 30
       0 2758.64    21.3 2752.91    59.9 2748.09    77.9 2738.08    87.5 2735.36
    98.5 2735.01   115.1 2736.99   137.5 2733.11   159.2 2732.08   227.9 2735.09
   301.8 2736.63     310 2736.05   318.8 2732.72   326.1 2731.68   340.6 2732.72
   353.6 2736.14   423.6 2737.01   444.1 2741.05   466.7 2741.05   510.2 2746.47
   524.6  2745.9   567.1 2747.84     604 2752.37   637.5 2759.66   670.9 2762.63
   694.2 2763.14   698.3 2764.73   718.8 2777.63   743.4 2786.44   759.4 2794.36
#Mann= 7 ,-1,0
       0      .1       0     180     .05       0  306.78      .1       0
   318.8    .045       0   340.6      .1       0  517.94     .06       0
  617.94      .1       0
#XS Ineff= 2 , 0
          287.55 2740.78
Permanent Ineff=
       F       F
Bank Sta=318.8,340.6
XS Rating Curve= 0 ,0
Exp/Cntr(USF)=0,0
Exp/Cntr=0.3,0.1

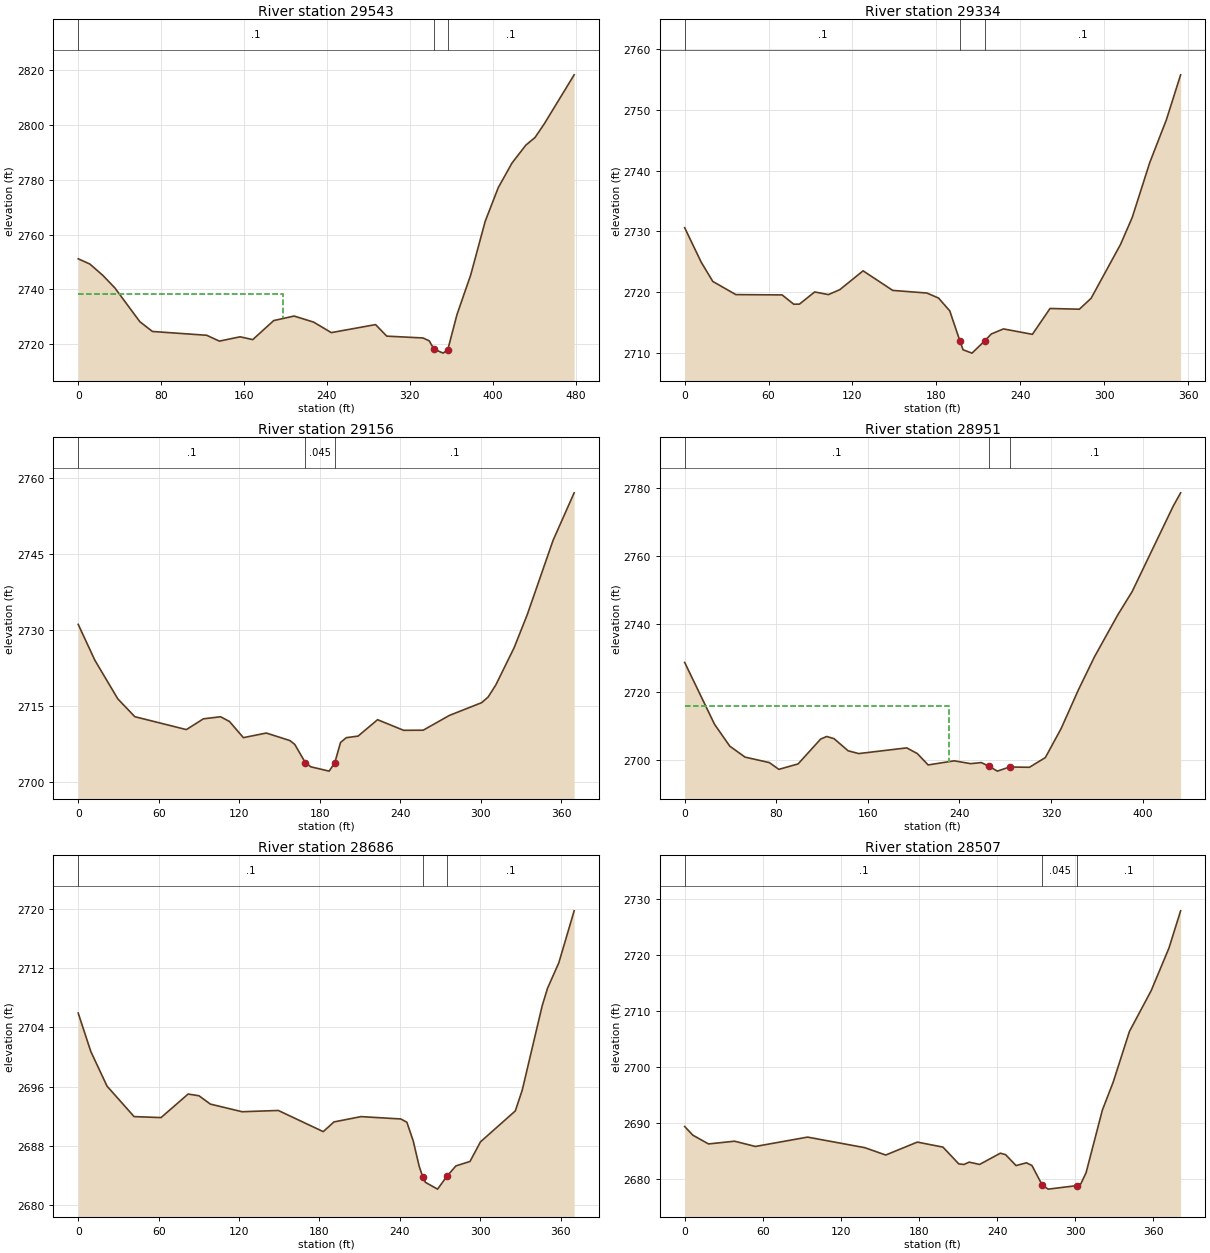
Type RM Length L Ch R = 1 ,29543   ,200.5,209.6,218.4
XS GIS Cut Line= 4
2212263.77022756463544.2467931482212238.81707151463348.435503077
2212148.88497842463267.7363036132212079.76298819463123.136156171
#Sta/Elev= 30
       0 2751.16    11.2 2749.27    23.8 2745.12    35.4 2740.55    59.5 2728.25
    71.6 2724.71     124 2723.32   136.2 2721.19   156.2 2722.76   168.4 2721.74
   188.6 2728.67   208.3 2730.32   227.1 2728.12   244.2 2724.29   286.9 2727.21
   297.7 2723.01   332.7 2722.34   338.7 2721.29   343.2  2718.3   352.1 2716.82
   356.62718.105   365.4 2730.79   378.7 2745.29   392.7 2764.85   405.3  2777.1
   418.6 2786.07   431.9 2792.55   440.8 2795.36   449.7 2800.32   478.5 2818.15
#Mann= 3 ,-1,0
       0      .1       0   343.2    .045       0   356.6      .1       0
#XS Ineff= 2 , 0
          198.03 2738.38
Permanent Ineff=
       F       F
Bank Sta=343.2,356.6
XS Rating Curve= 0 ,0
Exp/Cntr(USF)=0,0
Exp/Cntr=0.3,0.1

Type RM Length L Ch R = 1 ,29334   ,184.8,177.3,164.7
XS GIS Cut Line= 3
2212362.16651483463452.6438845022212320.87694709463293.718001128
2212378.52653224463112.199712765
#Sta/Elev= 30
       0 2730.62    11.8 2724.96    20.1 2721.79    36.6 2719.62    69.7 2719.57
      78 2718.04    82.1 2718.06      93 2720.06   102.8 2719.62     111 2720.44
   127.6 2723.53   148.8 2720.31   173.2 2719.88   181.6 2719.05   189.6 2716.94
   196.9 2711.97   199.1 2710.55   205.5    2710   214.7 2712.04   219.3 2713.15
     228 2713.98   248.7 2713.09   261.3 2717.34   282.3 2717.22   290.7 2719.02
   311.7 2727.86   320.1 2732.31   332.6 2741.31   344.5 2748.35   354.7 2755.75
#Mann= 3 ,-1,0
       0      .1       0   196.9    .045       0   214.7      .1       0
Bank Sta=196.9,214.7
XS Rating Curve= 0 ,0
Exp/Cntr(USF)=0,0
Exp/Cntr=0.3,0.1

Type RM Length L Ch R = 1 ,29156   ,207.9,205.6,202
XS GIS Cut Line= 3
2212558.79015742463436.859280056 2212488.3023561463243.494095364
2212395.90618411463108.233719864
#Sta/Elev= 30
       0 2731.07    12.4 2723.99    29.5 2716.35    42.2 2712.82    80.6 2710.27
    93.3  2712.4   106.1 2712.81   112.7 2711.88   123.1 2708.68   140.2 2709.59
   157.8  2708.1   161.4 2707.34   169.3 2703.72   173.4 2702.91     187 2702.06
   191.2  2703.7   195.5 2707.73   199.8 2708.67   208.6 2708.99   223.1 2712.23
   242.5 2710.13   257.1 2710.15   276.6 2713.07   300.7  2715.6   305.5 2716.71
   311.2 2719.09   324.9 2726.48   334.6 2732.96   353.9 2747.69   369.6 2757.08
#Mann= 3 ,-1,0
       0      .1       0   169.3    .045       0   191.2      .1       0
Bank Sta=169.3,191.2
XS Rating Curve= 0 ,0
Exp/Cntr(USF)=0,0
Exp/Cntr=0.3,0.1

Type RM Length L Ch R = 1 ,28951   ,264.8,264.3,265.7
XS GIS Cut Line= 3
2212783.75428901463417.1486050012212756.04539632463302.483399839
2212594.40470943463031.681306613
#Sta/Elev= 30
       0 2728.61    26.1 2710.41    39.4 2703.99    52.7 2700.77      74 2699.15
    82.3 2697.16    99.1 2698.76   118.8 2706.07   124.1 2706.83   130.5 2706.19
   142.8 2702.62   152.1  2701.8     194 2703.48   203.3  2701.8   212.7 2698.46
   235.5 2699.67   249.9 2698.84   259.2 2699.16   266.12698.008   273.2 2696.64
   283.82697.856   301.2 2697.77   315.1 2700.62   328.9 2709.16     344 2720.55
     358 2730.24   378.4  2742.6   390.9 2749.42   426.9 2774.63   433.3  2778.5
#Mann= 3 ,-1,0
       0      .1       0   266.1    .045       0   283.8      .1       0
#XS Ineff= 2 , 0
           230.9 2715.85
Permanent Ineff=
       F       F
Bank Sta=266.1,283.8
XS Rating Curve= 0 ,0
Exp/Cntr(USF)=0,0
Exp/Cntr=0.3,0.1

Type RM Length L Ch R = 1 ,28686   ,173.7,179.2,182.1
XS GIS Cut Line= 4
2212916.52218259463362.5553094752212944.56798895463136.809855533
2212901.70378545463058.7017513722212900.31951366463005.325037478
#Sta/Elev= 30
       0 2705.93     9.4 2700.74    21.5 2696.06    41.7 2691.94    61.8 2691.81
      82 2694.99    90.1 2694.76    98.6 2693.63   122.3  2692.6   149.3 2692.77
   182.8 2689.91   190.8 2691.22     211 2691.94   240.7 2691.62   245.2 2691.18
   249.9 2688.68   254.4 2685.22     257 2683.83     259 2683.06   268.1 2682.14
   275.22683.904   281.8 2685.28   292.3 2685.88   300.1 2688.53   326.1 2692.71
   331.3 2695.54   346.1 2706.88   350.1 2709.27   358.6 2712.75     370 2719.75
#Mann= 3 ,-1,0
       0      .1       0     257    .045       0   275.2      .1       0
Bank Sta=257,275.2
XS Rating Curve= 0 ,0
Exp/Cntr(USF)=0,0
Exp/Cntr=0.3,0.1

Type RM Length L Ch R = 1 ,28507   ,227.8,227.1,225.9
XS GIS Cut Line= 3
2213077.27780116463303.4623363832213087.83240426463042.235909711
2213054.84926958462927.454601022
#Sta/Elev= 30
       0 2689.31     6.3 2687.76    18.3  2686.2    38.3 2686.69    54.3 2685.75
    94.4 2687.42   138.4 2685.53   154.4 2684.22   178.7 2686.53   198.4 2685.63
   210.5 2682.64   214.5 2682.53   218.5 2682.95   226.5 2682.54   242.5 2684.55
   246.5 2684.28   254.5 2682.34   262.5 2682.83   266.7 2682.35   274.7 2678.82
   279.2 2678.13     3012678.747   304.2 2679.05   308.3 2681.07   320.8 2692.24
   329.1 2697.23   341.6 2706.29   358.3 2713.58   371.9 2721.15   380.9 2727.83
#Mann= 3 ,-1,0
       0      .1       0   274.7    .045       0     301      .1       0
Bank Sta=274.7,301
XS Rating Curve= 0 ,0
Exp/Cntr(USF)=0,0
Exp/Cntr=0.3,0.1

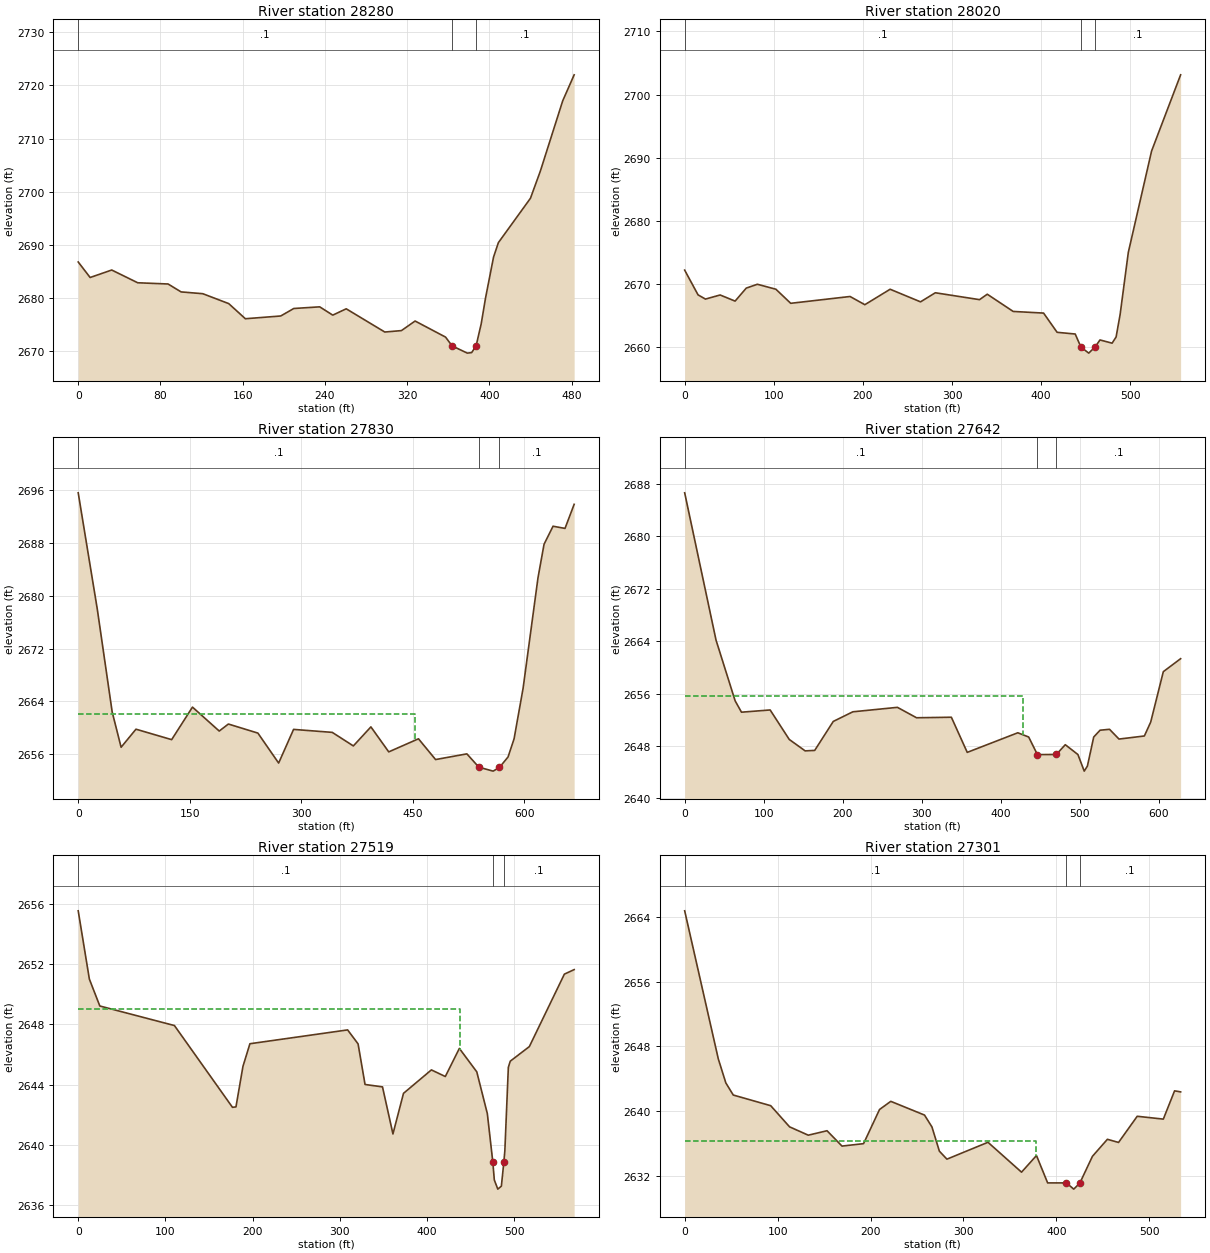
Type RM Length L Ch R = 1 ,28280   ,260.1,260.4,257.2
XS GIS Cut Line= 4
2213201.66438967463304.1647389252213307.48491194462985.356336488
2213283.67146555462917.7261487382213218.50525896462881.018847318
#Sta/Elev= 30
       0 2686.78    11.6 2683.86    32.6 2685.27    57.9 2682.87    87.4 2682.64
   100.1 2681.15   121.2 2680.81   146.4 2678.95   162.6  2676.1     197 2676.62
   209.7 2678.03   234.9 2678.34   247.6 2676.78   260.7 2677.97   298.2  2673.6
   314.4 2673.87   327.7 2675.67   357.3 2672.65   363.7 2670.99   378.5 2669.63
   382.7 2669.73     387 2670.98     392 2675.15   396.2    2680     404 2687.71
   408.7 2690.42   439.9 2698.77   449.5 2703.87   471.3 2717.12   482.4    2722
#Mann= 3 ,-1,0
       0      .1       0   363.7    .045       0     387      .1       0
Bank Sta=363.7,387
XS Rating Curve= 0 ,0
Exp/Cntr(USF)=0,0
Exp/Cntr=0.3,0.1

Type RM Length L Ch R = 1 ,28020   ,181.2,190,202.6
XS GIS Cut Line= 3
2213449.32756036463291.5884078982213557.51224211462914.261347149
2213480.99136965462769.135554554
#Sta/Elev= 30
       0 2672.15      15 2668.23    23.3 2667.56    39.8 2668.21    56.6 2667.24
    69.1  2669.3    81.6 2669.91   102.4 2669.12     119 2666.89   185.6 2667.97
   202.2 2666.67   230.6 2669.12   264.7 2667.12   281.3 2668.56   330.9 2667.47
   339.6 2668.33   368.7  2665.6   402.8 2665.34     418 2662.29   438.3 2662.02
   444.7 2659.95   453.5 2658.99   460.82660.001   466.1 2661.08   479.7 2660.57
   484.2 2661.55   488.7 2665.11   497.9 2674.96     524 2691.03   556.6 2703.12
#Mann= 3 ,-1,0
       0      .1       0   444.7    .045       0   460.8      .1       0
Bank Sta=444.7,460.8
XS Rating Curve= 0 ,0
Exp/Cntr(USF)=0,0
Exp/Cntr=0.3,0.1

Type RM Length L Ch R = 1 ,27830   ,189.1,188,184.5
XS GIS Cut Line= 3
2213690.97086906463334.8373725212213693.26274347462827.235052453
2213713.32218944462668.987278711
#Sta/Elev= 30
       0 2695.55    25.7 2677.94    45.7 2662.41    57.7 2657.08    77.7 2659.81
   125.7 2658.23   153.7 2663.15   189.7 2659.53     202 2660.59   241.7 2659.22
   269.6 2654.69   289.7 2659.78   341.7 2659.33   370.1 2657.28   393.7 2660.16
   417.7 2656.38   457.7 2658.36   480.7 2655.22   522.8 2656.08   538.9 2654.07
   558.1 2653.47   566.6 2654.03   578.2 2655.61   586.3 2658.36   598.4 2665.98
   618.5 2682.73   626.6 2687.77   638.7  2690.5   654.8 2690.17   667.1 2693.81
#Mann= 3 ,-1,0
       0      .1       0   538.9    .045       0   566.6      .1       0
#XS Ineff= 2 , 0
          453.52 2662.17
Permanent Ineff=
       F       F
Bank Sta=538.9,566.6
XS Rating Curve= 0 ,0
Exp/Cntr(USF)=0,0
Exp/Cntr=0.3,0.1

Type RM Length L Ch R = 1 ,27642   ,122.9,122.7,116
XS GIS Cut Line= 3
2213830.61259727463320.6135664172213867.55370811 463009.25277503
2213854.36045424462695.253332868
#Sta/Elev= 30
       0 2686.62    39.7 2664.15    63.9 2654.89    71.9 2653.16   108.2  2653.5
   132.4    2649   152.5 2647.26   164.6 2647.33   188.1 2651.75   212.9 2653.22
   269.3  2653.9   293.5 2652.31   337.6 2652.39   357.7 2647.03   421.7 2650.02
   435.5 2649.37   446.52646.691   470.5 2646.71   481.8  2648.2   497.8  2646.7
   505.8 2644.17   509.8 2644.94   517.8 2649.37   525.8 2650.41   537.8 2650.55
   549.8 2649.06   581.9 2649.53   589.9 2651.64   605.9 2659.34   627.8 2661.32
#Mann= 3 ,-1,0
       0      .1       0   446.5    .045       0   470.5      .1       0
#XS Ineff= 2 , 0
          428.68 2655.61
Permanent Ineff=
       F       F
Bank Sta=446.5,470.5
XS Rating Curve= 0 ,0
Exp/Cntr(USF)=0,0
Exp/Cntr=0.3,0.1

Type RM Length L Ch R = 1 ,27519   ,215.2,217.6,220.1
XS GIS Cut Line= 3
2213983.58553309463285.9678686282213963.98598873462845.631438797
2213950.90525282 462718.06976432
#Sta/Elev= 30
       0 2655.56    12.8 2651.02    24.8 2649.23   110.4 2647.93     177 2642.49
     181 2642.52     189 2645.21     197 2646.72   309.1 2647.64   321.1 2646.71
   329.1 2644.01   349.1 2643.85   361.1 2640.72   373.2 2643.42   405.2 2644.98
   421.2 2644.54   437.3 2646.41   457.3 2644.85   469.4 2642.07   475.72638.848
   477.4 2637.66   481.4 2637.05   485.5 2637.25   488.4 2638.88   489.5 2639.61
   493.5 2645.15   495.7 2645.56   517.6 2646.53   557.8 2651.35     569 2651.65
#Mann= 3 ,-1,0
       0      .1       0   475.7    .045       0   488.4      .1       0
#XS Ineff= 2 , 0
          438.42 2649.03
Permanent Ineff=
       F       F
Bank Sta=475.7,488.4
XS Rating Curve= 0 ,0
Exp/Cntr(USF)=0,0
Exp/Cntr=0.3,0.1

Type RM Length L Ch R = 1 ,27301   ,187.5,183.4,180.1
XS GIS Cut Line= 3
2214184.19180105463277.0758286382214151.20866637463026.404005064
2214176.27584873 462746.70702297
#Sta/Elev= 30
       0 2664.79    36.2 2646.45    44.3 2643.48    52.3 2641.98    92.6 2640.66
   112.9 2638.04     133 2637.01   153.2 2637.56   169.3 2635.66   192.5 2635.96
   209.7 2640.19   221.8  2641.2   258.1  2639.5   266.1 2638.03   274.1 2635.03
   282.2 2634.04   326.4 2636.13   362.5 2632.43   378.6 2634.49   390.6  2631.1
   410.82631.101   418.7 2630.33   425.2 2631.07   438.8 2634.39   454.9  2636.5
   466.9 2636.11     487 2639.35   515.1    2639   527.2  2642.5   533.7 2642.37
#Mann= 3 ,-1,0
       0      .1       0   410.8    .045       0   425.2      .1       0
#XS Ineff= 2 , 0
          378.59 2636.34
Permanent Ineff=
       F       F
Bank Sta=410.8,425.2
XS Rating Curve= 0 ,0
Exp/Cntr(USF)=0,0
Exp/Cntr=0.3,0.1