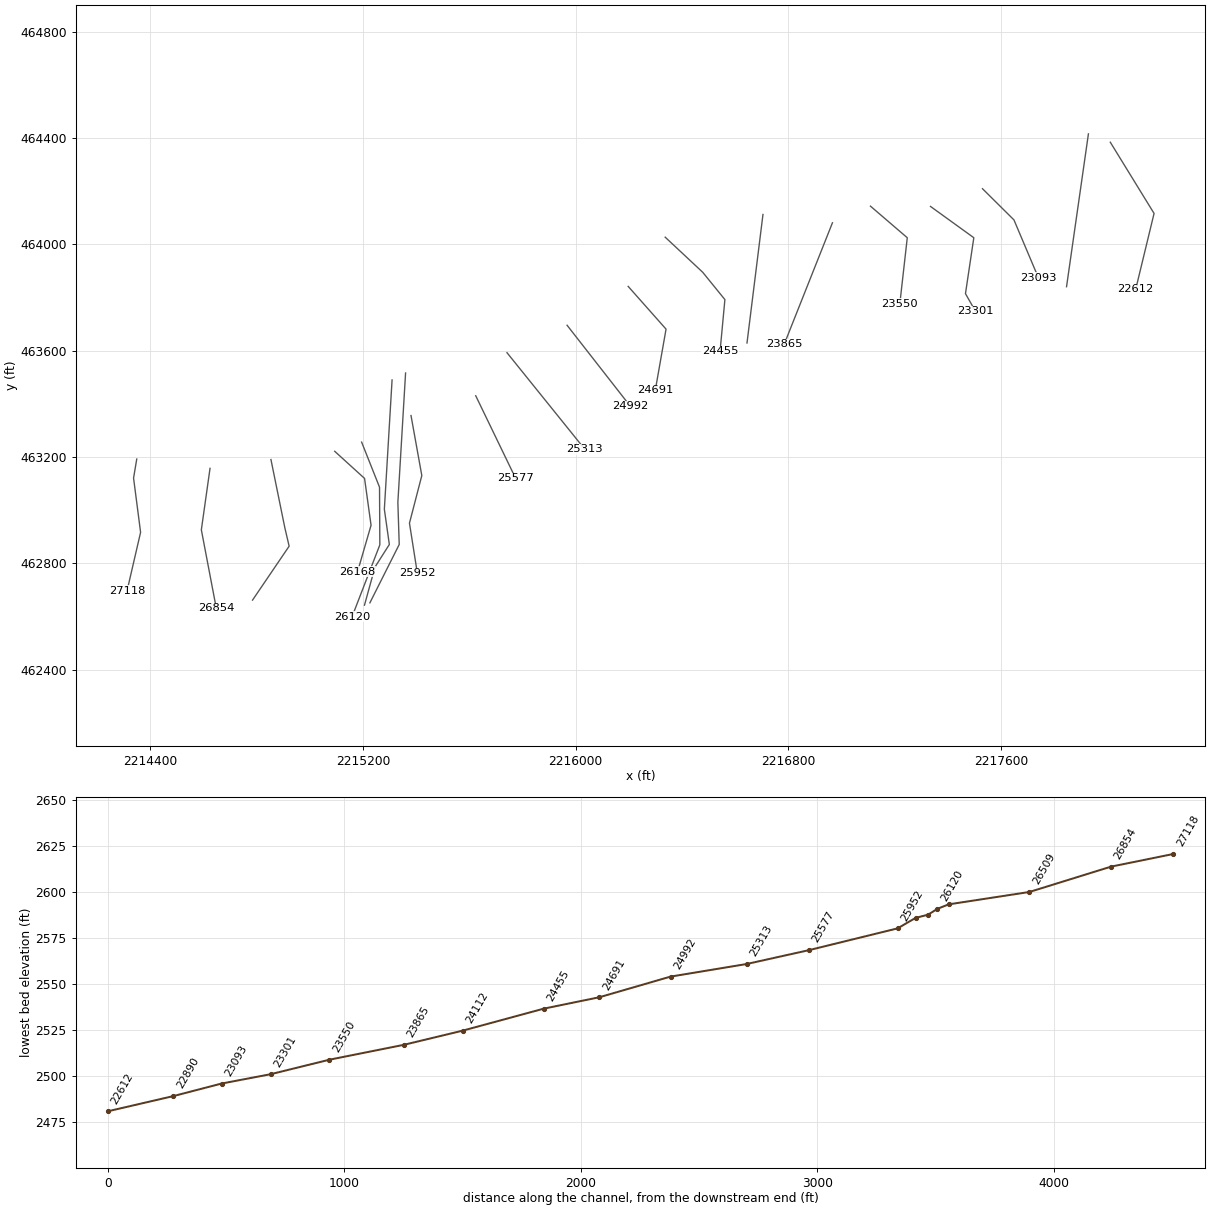
HEC-RAS study STONYCK.prj: STONYCK

--- STONYCK.g01 (geometry) --- (continued)

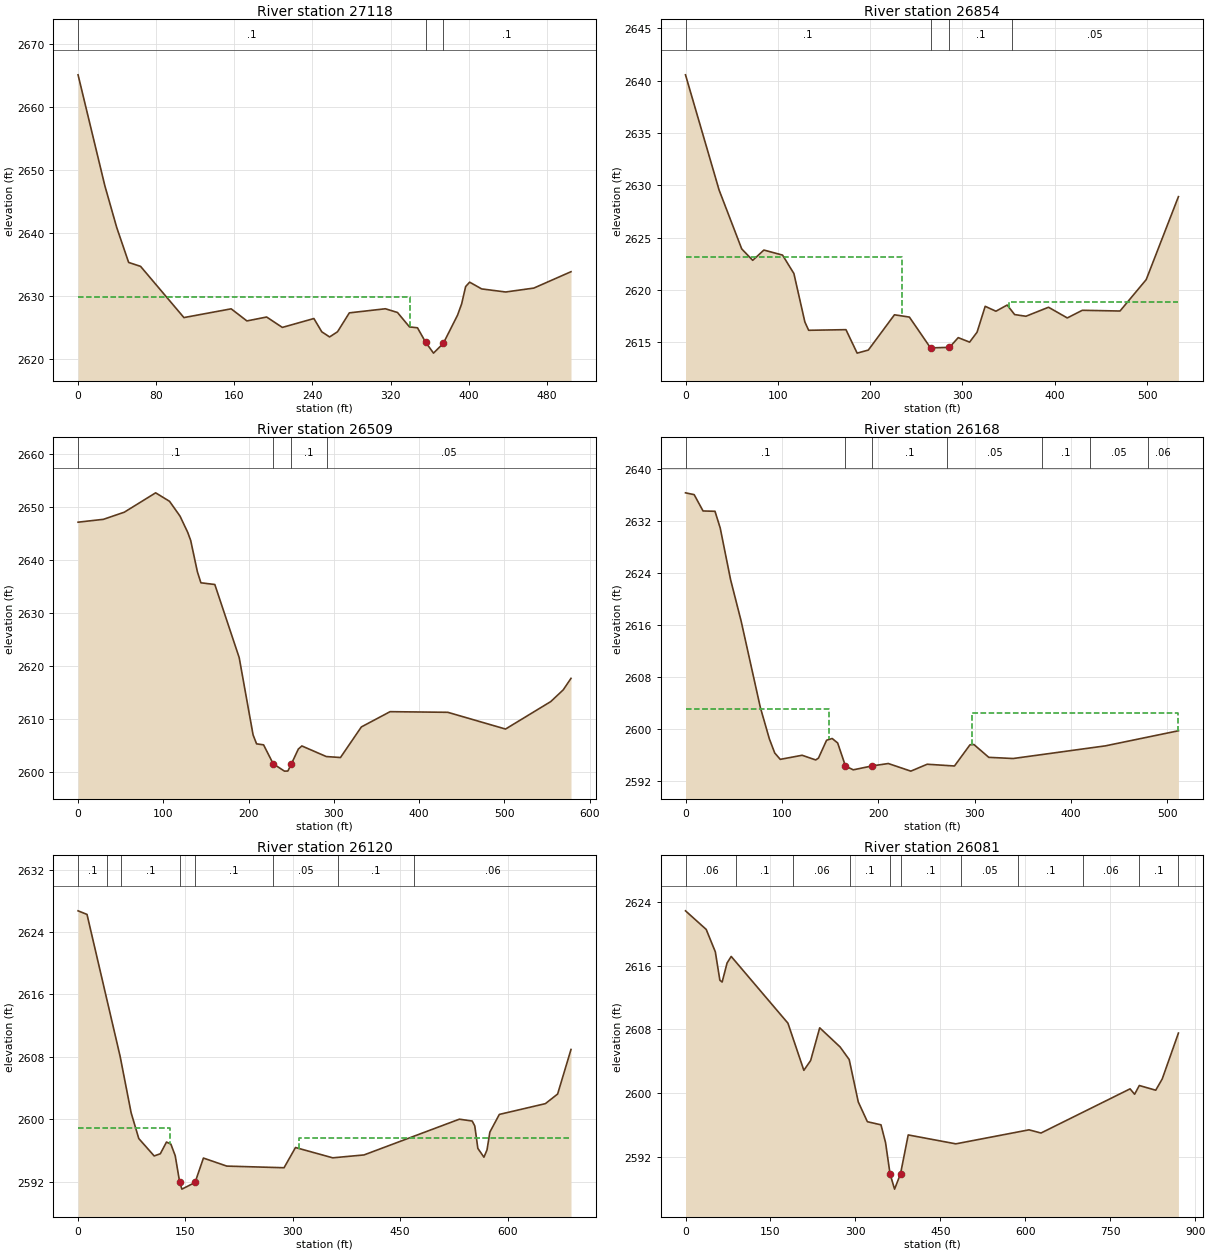
Type RM Length L Ch R = 1 ,27118   ,257.3,264.4,269.3
XS GIS Cut Line= 4
2214348.79805393463192.2744947642214336.77130764463120.733084031
2214363.22246874462916.5631842712214312.15360128462695.991530922
#Sta/Elev= 30
       0 2665.05    27.5 2647.41    39.6 2640.82    51.8 2635.28      64 2634.66
   108.4 2626.53   156.8 2627.92   172.9    2626   193.1 2626.62   209.2 2624.97
   241.5 2626.38   249.6 2624.27   257.6 2623.46   265.7 2624.28   277.8 2627.28
   314.7 2627.93   327.1 2627.34   339.4 2625.05   347.6 2624.91   355.92622.627
     364 2620.89     3742622.431   388.6 2626.91   392.8  2628.7   396.9 2631.45
     401 2632.15   413.3 2631.08   437.9 2630.59   466.7 2631.21   504.8 2633.81
#Mann= 3 ,-1,0
       0      .1       0   355.9    .045       0     374      .1       0
#XS Ineff= 2 , 0
          339.72 2629.72
Permanent Ineff=
       F       F
Bank Sta=355.9,374
XS Rating Curve= 0 ,0
Exp/Cntr(USF)=0,0
Exp/Cntr=0.3,0.1

Type RM Length L Ch R = 1 ,26854   ,343,344.6,344.2
XS GIS Cut Line= 3
2214624.43967466463157.234141398 2214591.7737674462925.959518015
2214648.00368251462630.972454629
#Sta/Elev= 30
       0 2640.55    36.4 2629.55    60.9 2623.93    72.8 2622.84    84.9 2623.82
   105.1 2623.34   117.4 2621.58   129.3 2616.95   133.4 2616.16   173.8 2616.22
   185.9 2613.98     198 2614.27   226.3 2617.64   242.5 2617.42   265.4 2614.48
   285.9 2614.53   295.4 2615.46   307.7 2615.03   315.8 2615.98   324.6 2618.45
   336.2 2617.98   348.4 2618.57   356.5 2617.66   368.7  2617.5   393.2 2618.36
   413.5 2617.34   429.8 2618.07   470.6    2618     499    2621   533.9 2628.92
#Mann= 4 ,-1,0
       0      .1       0   265.4    .045       0   285.9      .1       0
  353.57     .05       0
#XS Ineff= 2 , 0
          234.22 2623.15  350.54         2618.83
Permanent Ineff=
       F       F
Bank Sta=265.4,285.9
XS Rating Curve= 0 ,0
Exp/Cntr(USF)=0,0
Exp/Cntr=0.3,0.1

Type RM Length L Ch R = 1 ,26509   ,340.9,341.5,337.4
XS GIS Cut Line= 4
2214853.60016052463190.3639045392214905.80158696462934.033223653
2214922.03657724462864.3840288232214784.38371632462661.640062851
#Sta/Elev= 30
       0 2647.21    29.8 2647.75    54.3  2649.1      91 2652.75   107.3 2651.15
   119.6 2648.35   128.7 2645.26   132.1 2643.77     140 2637.83   144.1 2635.77
   160.4 2635.45     189 2621.65   205.3 2607.06   209.4 2605.38   217.6 2605.19
   228.9 2601.61   242.1 2600.23   246.1 2600.25   250.2 2601.59   258.4  2604.4
   262.5 2604.98   291.2 2602.98   307.8  2602.8   332.3 2608.57     366 2611.45
   433.7 2611.33   501.4 2608.17   554.5 2613.36   569.1 2615.57   578.2 2617.74
#Mann= 4 ,-1,0
       0      .1       0   228.9    .045       0   250.2      .1       0
  291.59     .05       0
Bank Sta=228.9,250.2
XS Rating Curve= 0 ,0
Exp/Cntr(USF)=0,0
Exp/Cntr=0.3,0.1

Type RM Length L Ch R = 1 ,26168   ,44.6,47.6,53.5
XS GIS Cut Line= 4
2215093.51613397463221.3966918122215205.77028989463119.347459164
2215230.21865571462943.1566522352215179.45643082462768.417455024
#Sta/Elev= 30
       0 2636.31       9 2636.03    18.2 2633.52    30.6 2633.47      36 2630.91
    46.8 2622.94    57.7  2616.6    77.6 2603.33      87 2598.47    92.6 2596.29
    98.3 2595.31     121 2595.94   135.1 2595.22     138 2595.51   146.4 2598.25
   152.2 2598.52   157.9 2597.83     166 2594.28   174.1  2593.7   193.6  2594.3
   210.4 2594.67   233.8  2593.5   250.8 2594.56   279.1 2594.29   295.2 2597.55
   299.3 2597.59   314.7 2595.62     340 2595.44   435.8 2597.39   511.5 2599.71
#Mann= 7 ,-1,0
       0      .1       0     166    .045       0   193.6      .1       0
  271.71     .05       0  369.59      .1       0  419.59     .05       0
  479.59     .06       0
#XS Ineff= 2 , 0
          149.41  2603.1  297.46         2602.39
Permanent Ineff=
       F       F
Bank Sta=166,193.6
XS Rating Curve= 0 ,0
Exp/Cntr(USF)=0,0
Exp/Cntr=0.3,0.1

Type RM Length L Ch R = 1 ,26120   ,43.4,38.9,30.2
BEGIN DESCRIPTION:
structure xs 4
END DESCRIPTION:
XS GIS Cut Line= 4
2215194.72108356463255.954433039 2215262.0925917463086.325349185
2215263.25131705462869.4053741312215159.06678011462599.819853741
#Sta/Elev= 30
       0 2626.71    12.5 2626.25    58.7 2608.09    74.1 2600.85    84.8 2597.54
   106.3 2595.31   114.9 2595.59   123.5 2597.09   129.6 2596.83   135.7 2595.34
   141.9 2591.97     145 2591.06   163.4 2591.91   175.1 2595.04   207.7 2594.01
   287.7  2593.8   303.7 2596.39   355.7 2595.07   399.4 2595.44   532.6 2600.02
   550.5 2599.78   554.1 2599.15   558.4 2596.28   566.9 2595.15   571.2 2596.09
   575.2 2598.37   588.4 2600.63   652.7 2602.01   669.8 2603.24   688.5 2608.95
#Mann= 8 ,-1,0
       0      .1       0      40     .06       0      60      .1       0
   141.9    .045       0   163.4      .1       0  272.52     .05       0
  362.52      .1       0  469.44     .06       0
#XS Ineff= 2 , 0
          128.96 2598.91  309.18         2597.64
Permanent Ineff=
       F       F
Bank Sta=141.9,163.4
XS Rating Curve= 0 ,0
Exp/Cntr(USF)=0,0
Exp/Cntr=0.5,0.3

Type RM Length L Ch R = 1 ,26081   ,53.9,53.5,54.2
BEGIN DESCRIPTION:
structure xs 3; 21.9 ft between structure and xs
END DESCRIPTION:
XS GIS Cut Line= 5
2215309.27795247463489.7606577562215280.24159047463003.401594145
2215299.00964081462870.8076613382215245.02158337462785.969285361
2215205.48668035462642.504415313
#Sta/Elev= 30
       0 2622.88    36.6 2620.54    52.7 2617.72    60.7 2614.16    64.7 2613.93
    73.4 2616.32    80.7 2617.15   180.9 2608.76     209 2602.84     221 2604.07
     237 2608.18   273.1 2605.77   289.1 2604.19   305.1 2598.87   321.2 2596.38
   345.2 2595.99   353.3 2593.75   361.2 2589.84   369.2 2587.91   379.72589.831
   393.3 2594.72   477.4  2593.6   606.6 2595.36   627.8 2594.96   785.1 2600.51
   793.1 2599.83   801.4 2600.93   830.4 2600.34   841.9 2601.76   870.5 2607.52
#Mann= 11 ,-1,0
       0     .06       0      90      .1       0     190     .06       0
     290      .1       0   361.2    .045       0   379.7      .1       0
  487.23     .05       0  587.23      .1       0  701.14     .06       0
   801.7      .1       0  870.51     .06       0
#XS Ineff= 2 , 0
             339  2595.9     401          2593.7
Permanent Ineff=
       F       F
Bank Sta=361.2,379.7
XS Rating Curve= 0 ,0
Exp/Cntr(USF)=0,0
Exp/Cntr=0.5,0.3

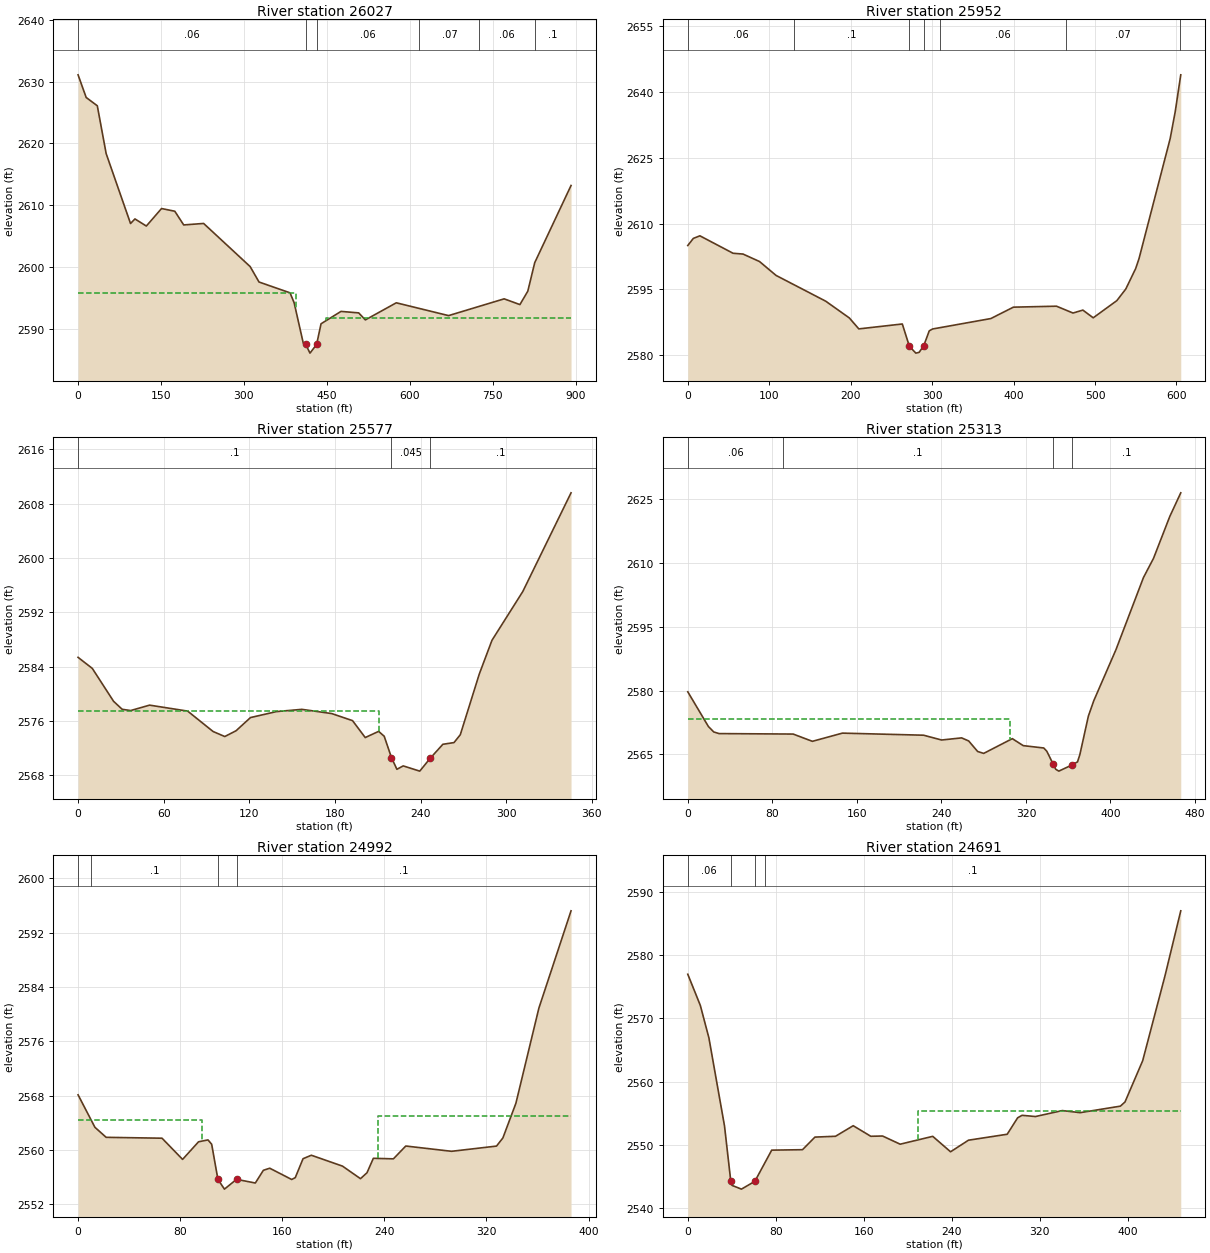
Type RM Length L Ch R = 1 ,26027   ,77.8,75.8,72
BEGIN DESCRIPTION:
structure xs 2; 17.9 ft between structure and xs
END DESCRIPTION:
XS GIS Cut Line= 4
2215360.09158598463515.8933835622215331.05522398463029.534319951
2215336.17025177462870.8076613382215225.82201176462651.289412631
#Sta/Elev= 30
       0 2631.08    14.7 2627.42    34.8 2626.08    50.8 2618.36    94.9 2607.06
   102.9  2607.8   123.5 2606.65     151 2609.48     175 2609.04   191.1 2606.83
   227.1 2607.07   311.3  2600.1   327.3 2597.61   383.4 2595.86   390.8 2594.27
   407.4 2587.72   411.4  2587.6   419.5 2586.12   431.5 2587.52   439.5 2590.86
   475.6 2592.86   507.6 2592.62   519.7 2591.49   575.6 2594.25   670.2 2592.18
   770.7 2594.89   799.2 2593.96   813.5 2596.13     826 2600.73   891.7  2613.2
#Mann= 6 ,-1,0
       0     .06       0   411.4    .045       0   431.5     .06       0
  617.23     .07       0  726.03     .06       0  826.03      .1       0
#XS Ineff= 2 , 0
             394  2595.9     449          2591.8
Permanent Ineff=
       F       F
Bank Sta=411.4,431.5
XS Rating Curve= 0 ,0
Exp/Cntr(USF)=0,0
Exp/Cntr=0.5,0.3

Type RM Length L Ch R = 1 ,25952   ,365.3,374.4,384.5
BEGIN DESCRIPTION:
structure xs 1
END DESCRIPTION:
XS GIS Cut Line= 4
2215380.53913704463355.8925097032215421.16641359463130.142090544
2215374.70338151462951.1023687882215404.36440323462762.494415158
#Sta/Elev= 30
       0 2605.01     6.8 2606.63    14.9 2607.22    55.6 2603.24    67.8 2603.06
    88.1 2601.35   108.4 2598.18   169.4  2592.3   198.4 2588.47     210 2585.98
   263.4  2587.1   272.12581.999     280 2580.45   284.1 2580.63   289.82582.189
   296.5 2585.54   300.6 2585.96   372.1 2588.34   399.8 2590.94   452.7 2591.16
     473  2589.6   485.1 2590.27   497.8 2588.51   526.8 2592.43   537.8 2595.08
   549.9 2599.74     554 2601.99   592.3 2629.41   598.5 2635.56   605.3 2643.96
#Mann= 7 ,-1,0
       0     .06       0     130      .1       0   272.1    .045       0
   289.8      .1       0  309.38     .06       0  464.35     .07       0
  604.35      .1       0
Bank Sta=272.1,289.8
XS Rating Curve= 0 ,0
Exp/Cntr(USF)=0,0
Exp/Cntr=0.3,0.1

Type RM Length L Ch R = 1 ,25577   ,261.9,263.9,267
XS GIS Cut Line= 2
2215624.01643674463430.3211260712215774.27961012 463119.34168898
#Sta/Elev= 30
       0 2585.37      10 2583.74    24.9  2578.9    30.9 2577.73    36.8 2577.54
    50.1 2578.34    76.8 2577.46    94.6 2574.46   102.8 2573.72   110.7 2574.57
   120.8 2576.51     139 2577.39   156.8 2577.72   177.7  2577.1   192.3 2576.06
   201.2 2573.57   210.6 2574.48   214.5 2573.76   219.6 2570.61   223.4  2568.9
   227.8  2569.4   239.4 2568.63   246.6 2570.49   255.6 2572.58   263.4 2572.83
   267.8 2573.98   281.1 2582.91     290 2587.88   311.6 2595.06   345.4 2609.58
#Mann= 3 ,-1,0
       0      .1       0   219.6    .045       0   246.6      .1       0
#XS Ineff= 2 , 0
          211.18 2577.41
Permanent Ineff=
       F       F
Bank Sta=219.6,246.6
XS Rating Curve= 0 ,0
Exp/Cntr(USF)=0,0
Exp/Cntr=0.3,0.1

Type RM Length L Ch R = 1 ,25313   ,320.6,321.7,322.4
XS GIS Cut Line= 2
2215741.61370287463592.3440260682216034.30023189463229.099137365
#Sta/Elev= 30
       0 2579.74    19.5 2571.58    24.6 2570.29    29.6 2569.91    99.7  2569.8
   117.9 2568.09   146.3 2570.02   223.1 2569.53   240.2  2568.4   259.1  2568.9
   265.8 2568.18   274.3  2565.7     280 2565.25   307.1 2568.72   317.4 2567.08
   336.9 2566.52   339.8 2565.73   345.92562.652   348.2 2561.52   351.1 2561.08
   363.6 2562.53   368.8 2563.26     371 2564.95   379.1 2574.04   384.2 2577.65
   405.2 2589.67   431.2 2606.62   440.7 2611.13   456.1 2620.98   466.5 2626.55
#Mann= 4 ,-1,0
       0     .06       0      90      .1       0   345.9    .045       0
   363.6      .1       0
#XS Ineff= 2 , 0
          304.51  2573.3
Permanent Ineff=
       F       F
Bank Sta=345.9,363.6
XS Rating Curve= 0 ,0
Exp/Cntr(USF)=0,0
Exp/Cntr=0.3,0.1

Type RM Length L Ch R = 1 ,24992   ,299.8,300.8,300
XS GIS Cut Line= 2
2215967.66178109463695.5682930022216205.46958592463391.122037362
#Sta/Elev= 30
       0 2568.13    13.2 2563.35      22 2561.87    65.8 2561.74    81.9 2558.62
    94.4 2561.21   101.8 2561.49   104.7 2560.85   109.6 2555.67   114.7 2554.24
   124.22555.681   138.9 2555.14   145.2 2557.01   150.2 2557.32   167.4 2555.66
   170.2 2555.93   176.3 2558.72   182.8 2559.23   207.2 2557.63   221.3 2555.78
   226.4 2556.65   231.4 2558.78   247.1  2558.7   256.8 2560.59   292.7 2559.81
   327.9 2560.58   332.9 2561.78   343.1 2566.89   361.1  2580.9   386.3 2595.23
#Mann= 4 ,-1,0
       0     .06       0      10      .1       0   109.6    .045       0
   124.2      .1       0
#XS Ineff= 2 , 0
           97.13 2564.36  235.04         2565.07
Permanent Ineff=
       F       F
Bank Sta=109.6,124.2
XS Rating Curve= 0 ,0
Exp/Cntr(USF)=0,0
Exp/Cntr=0.3,0.1

Type RM Length L Ch R = 1 ,24691   ,234,235.4,237.1
XS GIS Cut Line= 3
2216197.55528991463841.7273217992216339.97864555463681.011058092
2216299.47292055463451.043070999
#Sta/Elev= 30
       0 2576.98    11.4 2572.06    19.2 2566.93    33.4    2553    39.1 2544.27
    40.1 2543.63    48.8 2543.03      612544.267    76.3 2549.19   104.3 2549.26
   115.6 2551.25   134.3 2551.38   150.4 2553.05   166.4 2551.38   177.1 2551.42
   193.1 2550.13   222.7 2551.37   238.9 2548.93   255.2 2550.76   290.4  2551.7
   299.9  2554.3   303.9 2554.69   316.1  2554.5   340.5 2555.44   356.7 2555.11
   393.3 2556.14   397.5  2556.8   413.6 2563.33   433.9 2576.76   448.2    2587
#Mann= 4 ,-1,0
       0     .06       0    39.1    .045       0      61     .06       0
      70      .1       0
#XS Ineff= 2 , 0
                          209.58         2555.39
Permanent Ineff=
       F       F
Bank Sta=39.1,61
XS Rating Curve= 0 ,0
Exp/Cntr(USF)=0,0
Exp/Cntr=0.3,0.1

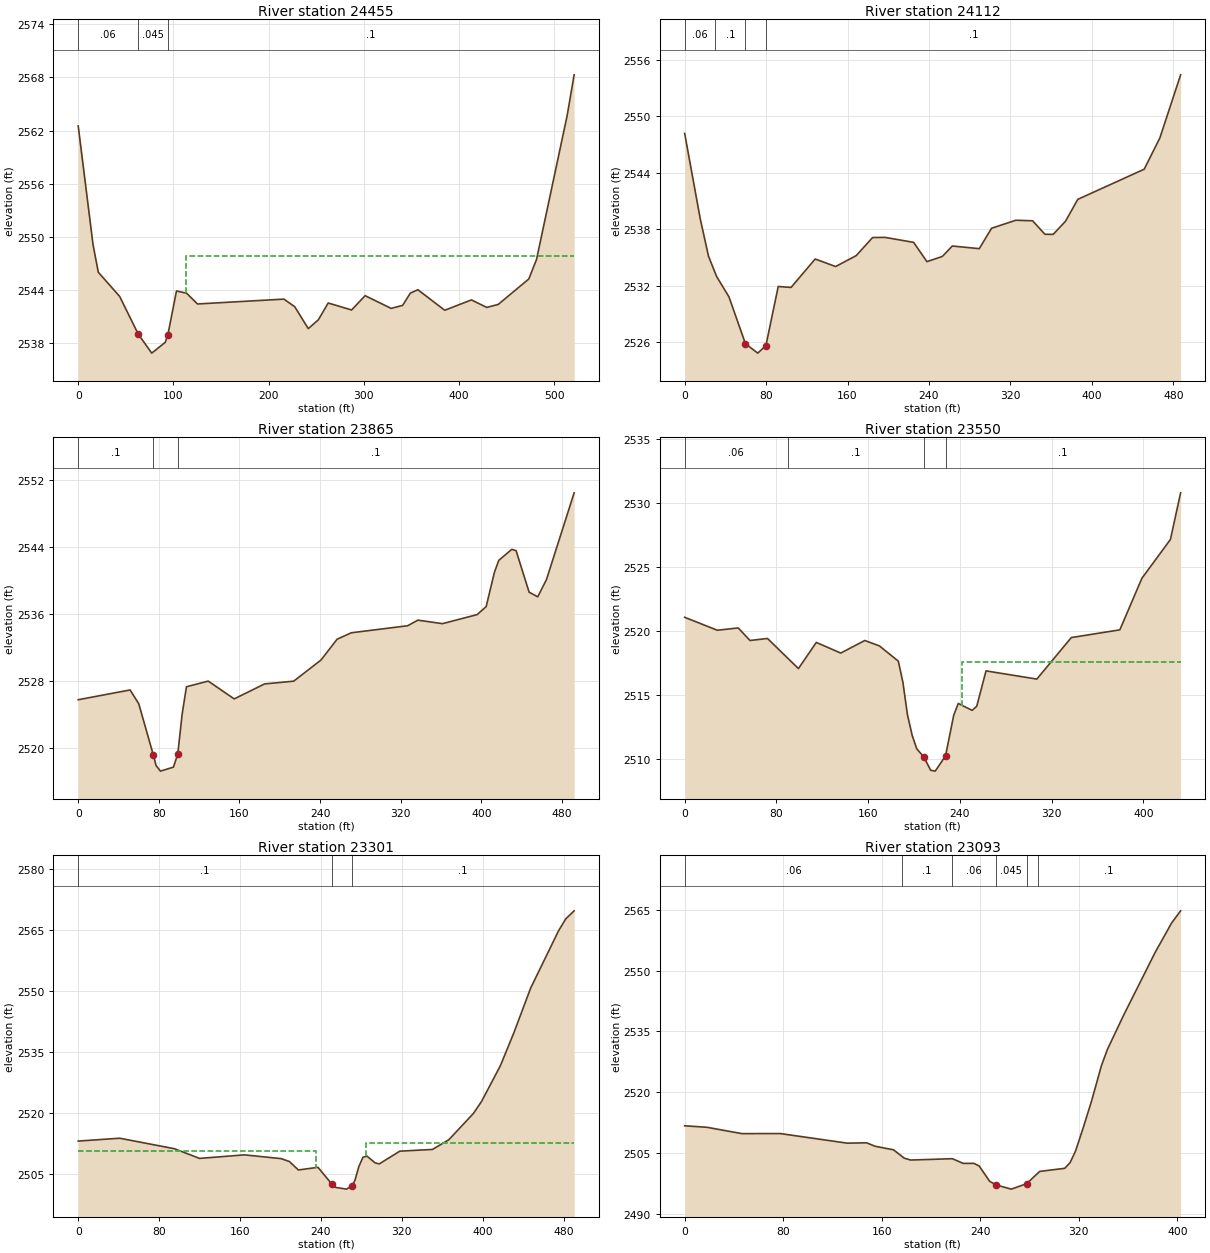
Type RM Length L Ch R = 1 ,24455   ,359.3,343.3,324.1
XS GIS Cut Line= 4
2216336.76693355464026.915576586 2216477.8836529463894.945311265
2216561.35422678463792.1559002062216543.19456124463597.864564395
#Sta/Elev= 30
       0 2562.52    15.6 2549.07    21.1 2545.97    43.5 2543.24    63.1 2538.96
    77.2 2536.82    91.4 2538.04    94.2 2538.92   103.2 2543.85   113.8  2543.6
   125.3 2542.38     216 2542.93   227.4 2542.07   241.6 2539.59   252.2 2540.59
   262.5 2542.49   287.1  2541.7   301.3 2543.32   328.6 2541.88   340.7 2542.22
   348.7  2543.6   356.7 2543.99   384.9 2541.67     413 2542.84     429 2541.99
   441.1 2542.33   473.2 2545.21   481.3 2547.42   513.4 2563.66   520.8  2568.3
#Mann= 3 ,-1,0
       0     .06       0    63.1    .045       0    94.2      .1       0
#XS Ineff= 2 , 0
                           112.9          2547.8
Permanent Ineff=
       F       F
Bank Sta=63.1,94.2
XS Rating Curve= 0 ,0
Exp/Cntr(USF)=0,0
Exp/Cntr=0.3,0.1

Type RM Length L Ch R = 1 ,24112   ,251.2,247.1,242
XS GIS Cut Line= 2
2216704.60464882464112.3852696072216644.49937946463628.929842196
#Sta/Elev= 30
       0 2548.19    15.3 2539.12    23.4 2535.15    31.4 2532.99    43.5 2530.83
    59.7 2525.85    71.8 2524.85    79.8 2525.65    91.9 2531.93   104.5 2531.83
   128.2 2534.85   148.3 2534.05   168.5 2535.21   184.6 2537.13   196.7 2537.15
   224.9 2536.62     238 2534.57   253.1 2535.12   262.9 2536.23   289.4 2535.95
   301.5 2538.12   325.4 2538.97   341.8 2538.91   353.9 2537.48     362 2537.47
   374.1 2538.86   386.2 2541.19   451.4 2544.39   466.8 2547.71   487.2 2554.42
#Mann= 4 ,-1,0
       0     .06       0      30      .1       0    59.7    .045       0
    79.8      .1       0
Bank Sta=59.7,79.8
XS Rating Curve= 0 ,0
Exp/Cntr(USF)=0,0
Exp/Cntr=0.3,0.1

Type RM Length L Ch R = 1 ,23865   ,310.4,315.4,321.2
XS GIS Cut Line= 2
2216965.93190688 464081.025998642216784.30946253463623.703297035
#Sta/Elev= 30
       0 2525.74    51.5 2526.91    60.1 2525.25   74.492519.151    77.3 2517.86
    81.6  2517.2    94.5 2517.68    98.8 2519.25   103.1 2523.99   107.4 2527.29
     129 2527.97   154.8 2525.84   184.9 2527.63   213.8 2527.96   240.9 2530.49
   256.9 2532.98     271 2533.75   326.9 2534.59     337 2535.26   361.4 2534.84
   395.8 2535.92   404.8 2536.88     413 2540.99   417.3 2542.41   430.2 2543.73
   434.5 2543.57   447.4 2538.61     456 2538.05   464.7 2540.14   492.1 2550.49
#Mann= 3 ,-1,0
       0      .1       0   74.49    .045       0    98.8      .1       0
Bank Sta=74.49,98.8
XS Rating Curve= 0 ,0
Exp/Cntr(USF)=0,0
Exp/Cntr=0.3,0.1

Type RM Length L Ch R = 1 ,23550   ,248.5,248.3,247.5
XS GIS Cut Line= 3
2217108.87739438464143.7194531582217247.47267721464024.883595093
 2217219.4193472   463776.579743
#Sta/Elev= 30
       0 2521.09    28.5 2520.08    46.7 2520.26      57 2519.28    72.2 2519.44
    99.2 2517.09   114.8 2519.13   136.1  2518.3   157.1 2519.28   169.8 2518.86
   186.3 2517.67   190.3 2516.03   194.3 2513.48   198.4 2511.88   202.4 2510.83
   208.62510.191   214.5 2509.16   218.5 2509.09   227.52510.279   234.6 2513.44
   238.6 2514.37   250.7 2513.83   254.7 2514.15   262.8 2516.91   307.1 2516.27
   337.2 2519.51   379.5 2520.11   398.7 2524.13   423.6 2527.16   432.5  2530.8
#Mann= 4 ,-1,0
       0     .06       0      90      .1       0   208.6    .045       0
   227.5      .1       0
#XS Ineff= 2 , 0
                          242.25         2517.58
Permanent Ineff=
       F       F
Bank Sta=208.6,227.5
XS Rating Curve= 0 ,0
Exp/Cntr(USF)=0,0
Exp/Cntr=0.3,0.1

Type RM Length L Ch R = 1 ,23301   ,200.6,208.1,217.5
XS GIS Cut Line= 4
2217334.89032409464142.5784983492217497.79962567464024.883595093
2217466.37360606463814.4721954192217504.26605848463747.833744614
#Sta/Elev= 30
       0 2513.03    41.1 2513.73    95.3 2511.14     120 2508.77   164.4 2509.64
   200.5 2508.72   208.8 2508.01   217.7 2505.93   237.1 2506.58   251.12502.364
   254.9 2501.63   265.4 2501.22   270.72502.078   273.5 2503.29   277.5 2506.77
   281.6 2509.06   285.6 2509.32   293.6 2507.67   297.7 2507.42     318 2510.55
   350.3 2510.97   366.5 2513.36   390.8 2519.82   398.9  2522.8   417.4 2531.52
   430.7 2539.58   447.4 2550.63     475 2564.71   482.1 2567.63   490.4 2569.61
#Mann= 3 ,-1,0
       0      .1       0   251.1    .045       0   270.7      .1       0
#XS Ineff= 2 , 0
          235.21  2510.7  284.79         2512.46
Permanent Ineff=
       F       F
Bank Sta=251.1,270.7
XS Rating Curve= 0 ,0
Exp/Cntr(USF)=0,0
Exp/Cntr=0.3,0.1

Type RM Length L Ch R = 1 ,23093   ,217,203.3,196.2
XS GIS Cut Line= 3
2217530.45180961464209.2332638482217648.82891949464091.876646302
2217740.67322887463874.511780761
#Sta/Elev= 30
       0 2511.74    18.2 2511.36    46.5  2509.8    77.6 2509.82     132 2507.45
   147.8 2507.54   154.5  2506.7   169.6 2505.81   178.3 2503.75   183.5 2503.29
   217.4 2503.62   226.1 2502.47   234.8 2502.47   239.1 2501.84   247.6 2498.06
   252.92497.152   265.2 2496.12   277.62497.452   288.3 2500.49   308.6 2501.25
   312.9 2502.63   317.3 2505.44   323.4 2511.05   330.3 2517.74   338.4 2526.56
   343.3 2530.59   356.3 2538.92   381.9 2554.41   395.4 2561.74   402.7 2564.73
#Mann= 6 ,-1,0
       0     .06       0  176.69      .1       0  216.69     .06       0
   252.9    .045       0   277.6     .06       0  286.69      .1       0
Bank Sta=252.9,277.6
XS Rating Curve= 0 ,0
Exp/Cntr(USF)=0,0
Exp/Cntr=0.3,0.1

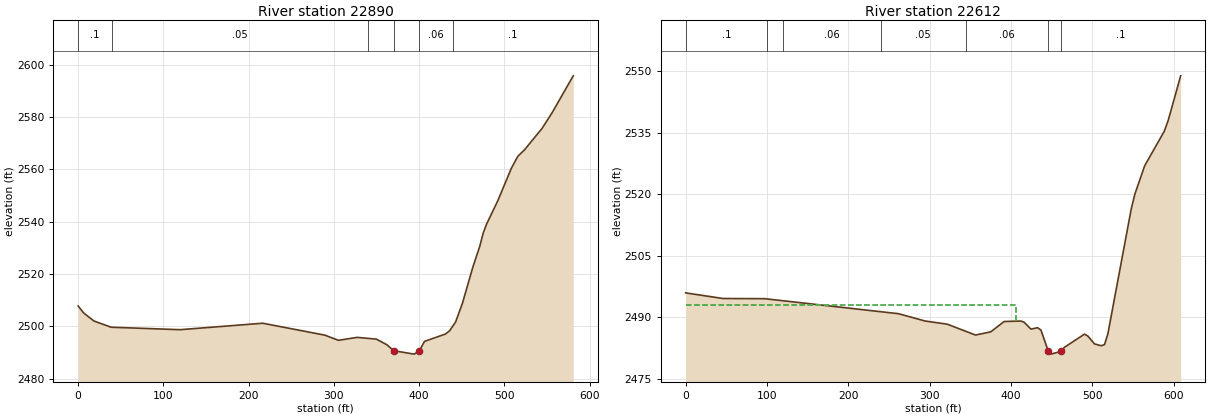
Type RM Length L Ch R = 1 ,22890   ,279.8,278.2,276.7
XS GIS Cut Line= 2
2217928.92285283464415.5248889572217846.60476654463840.604921225
#Sta/Elev= 30
       0 2507.71     6.4 2505.08    18.5 2501.99    38.7 2499.61   119.6 2498.67
   216.5 2501.14   289.3 2496.59   305.4 2494.61   327.3 2495.73   349.9 2495.06
     362 2492.95   370.3 2490.63   394.3 2489.33   400.22490.609   406.4 2494.22
   430.7 2496.98   435.8 2498.25   442.8 2501.61   450.9 2508.84     463 2522.55
   471.1 2530.47   475.1 2535.49   479.2 2539.03   492.4 2548.01   508.2 2560.35
   515.9 2564.97   523.6 2567.39   544.2 2575.57     556 2581.56   580.8 2595.68
#Mann= 6 ,-1,0
       0      .1       0      40     .05       0     340     .06       0
   370.3    .045       0   400.2     .06       0     440      .1       0
Bank Sta=370.3,400.2
XS Rating Curve= 0 ,0
Exp/Cntr(USF)=0,0
Exp/Cntr=0.3,0.1

Type RM Length L Ch R = 1 ,22612   ,424.6,419.7,414.8
XS GIS Cut Line= 3
2218011.24093912464384.165617989 2218175.8771117464116.305178478
2218106.62538831463830.151830902
#Sta/Elev= 30
       0 2495.95    45.8 2494.58    97.4 2494.53   261.7 2490.88   294.6 2489.09
   321.7 2488.33   356.5 2485.68   375.2 2486.45   391.7 2488.97   412.3 2489.09
   416.4 2488.79   424.6 2487.12   432.9 2487.47     437 2486.89     446 2481.76
   449.3 2481.03   461.7 2481.71   465.8 2482.68   490.5  2485.9   494.6 2485.44
   502.8 2483.53   511.1 2483.07   515.2 2483.36   519.3 2485.98   548.1 2516.45
   552.5 2520.01   564.6 2526.93   588.5 2535.25   593.4 2537.89   608.8 2548.81
#Mann= 7 ,-1,0
       0      .1       0     100     .05       0     120     .06       0
     240     .05       0  344.41     .06       0     446    .045       0
   461.7      .1       0
#XS Ineff= 2 , 0
           405.8 2492.99
Permanent Ineff=
       F       F
Bank Sta=446,461.7
XS Rating Curve= 0 ,0
Exp/Cntr(USF)=0,0
Exp/Cntr=0.3,0.1