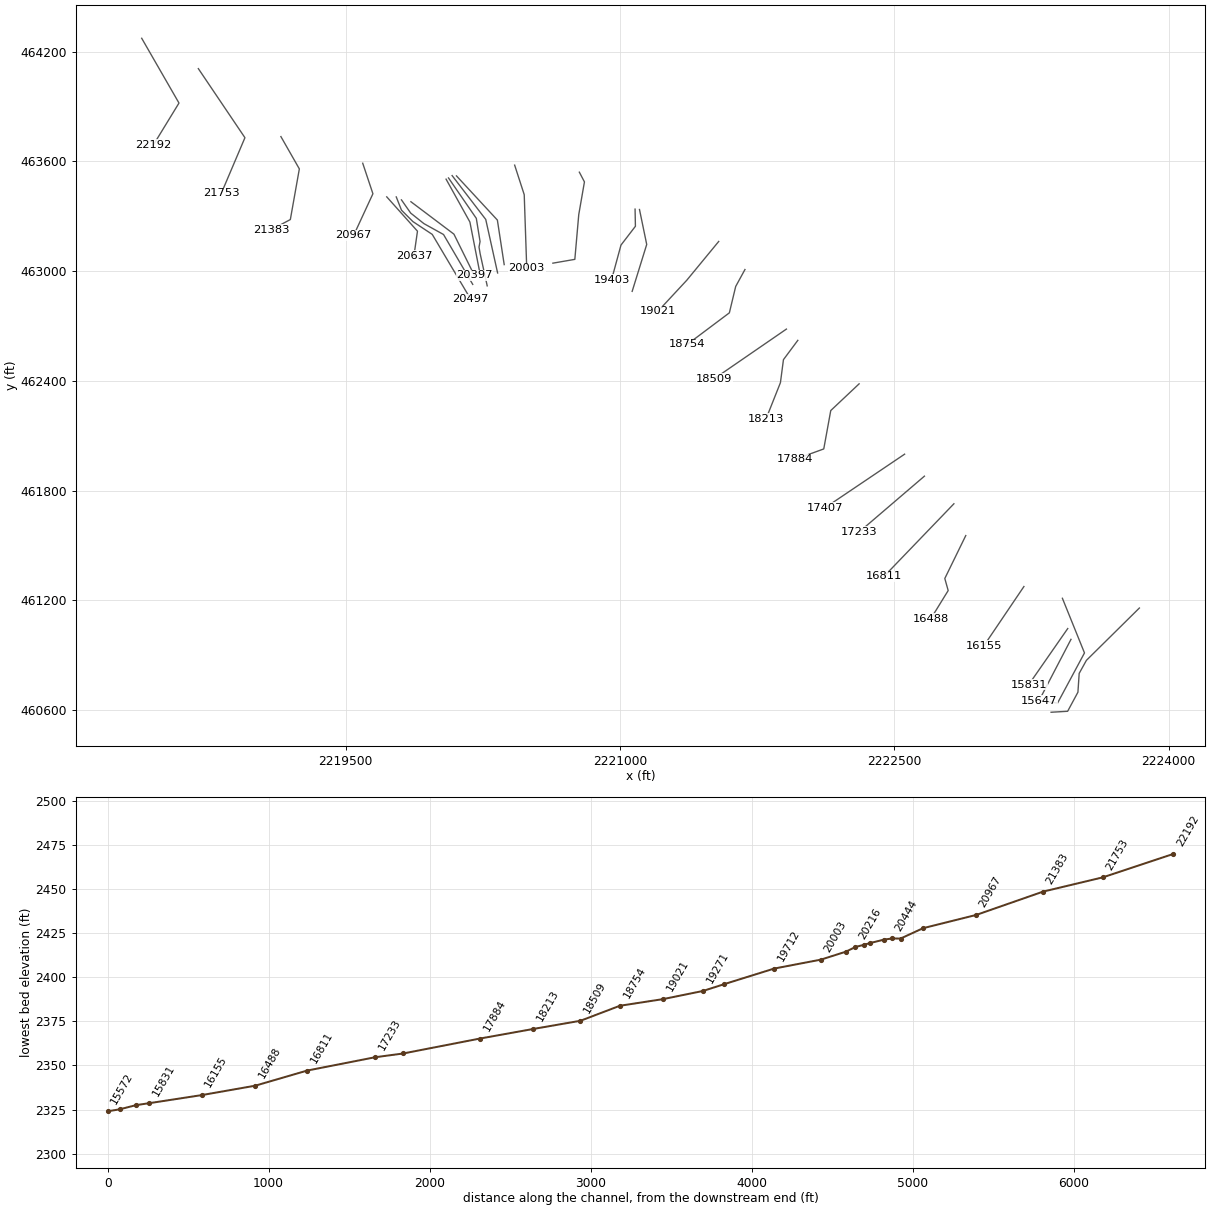
HEC-RAS study STONYCK.prj: STONYCK

--- STONYCK.g01 (geometry) --- (continued)

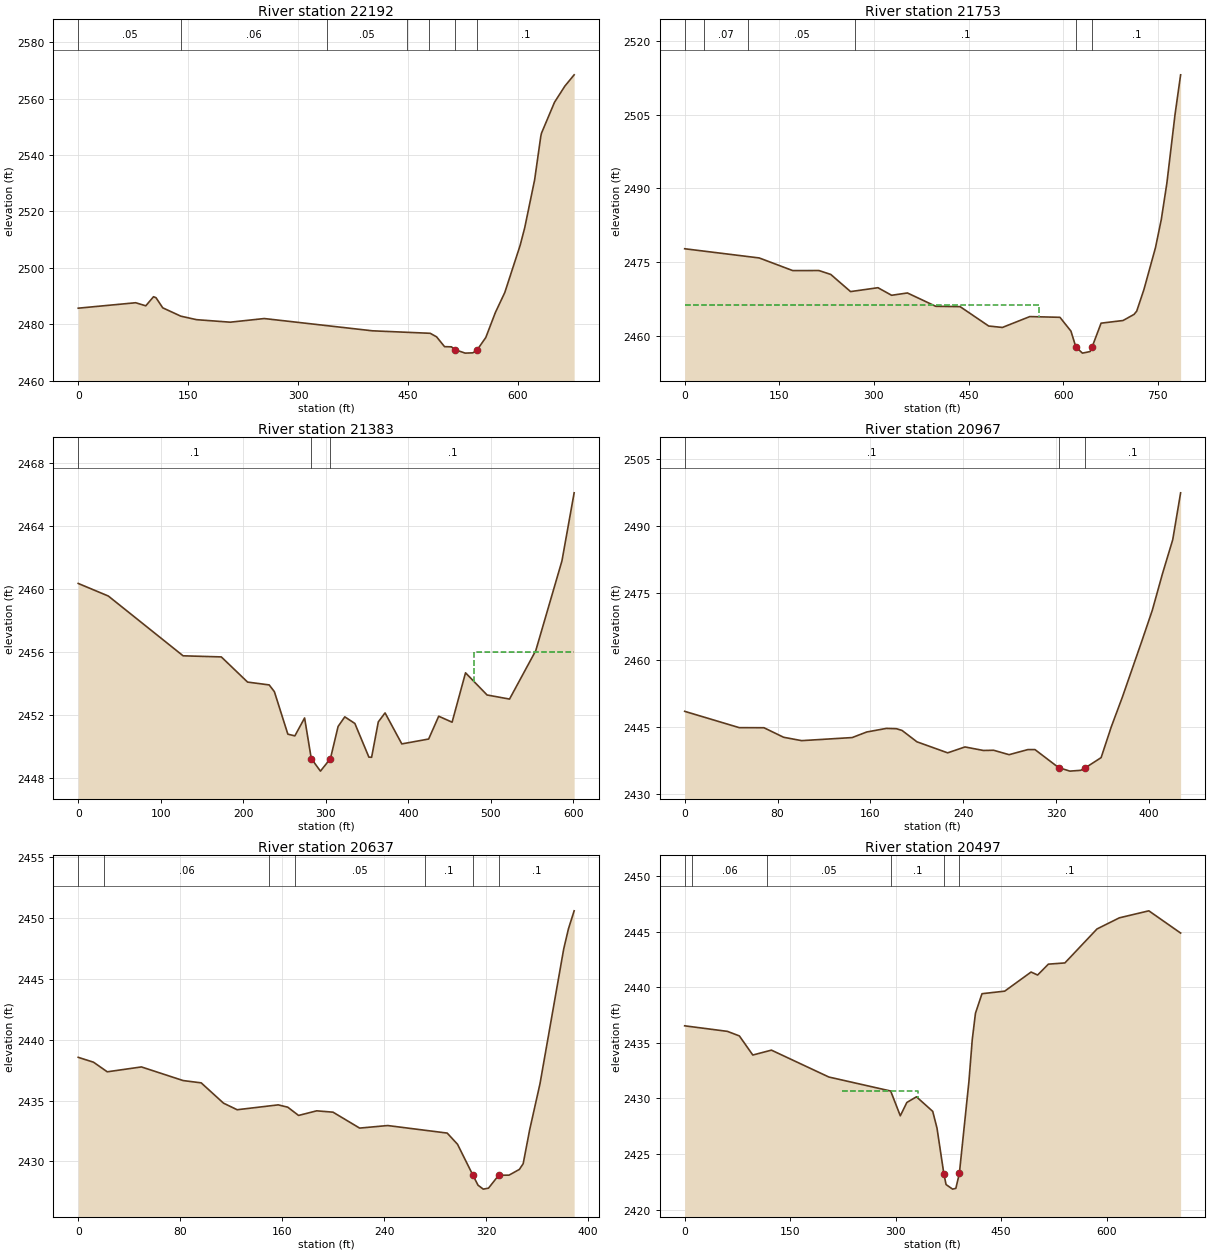
Type RM Length L Ch R = 1 ,22192   ,435.4,439,441.6
XS GIS Cut Line= 3
2218384.93891814464273.1015333142218588.77417943463919.003098643
2218448.96409637 463690.34174784
#Sta/Elev= 30
       0  2485.7    78.4 2487.63    92.2 2486.54   102.7 2489.76   106.1 2489.42
   115.3 2485.83     140 2482.87   161.4 2481.63   207.4 2480.74   253.8 2482.03
   401.5 2477.68   480.2  2476.8   488.9 2475.55   499.8 2472.06   509.2    2472
   513.9 2471.03   527.9 2469.77   538.4 2469.87   544.2 2470.88   556.1 2475.33
   569.1 2484.15     582 2491.27   602.9 2507.96   609.1 2514.14   622.7 2531.22
   631.1 2546.64   632.1 2547.77   649.8 2558.69   663.9 2564.41   676.6 2568.42
#Mann= 7 ,-1,0
       0     .05       0     140     .06       0     340     .05       0
  448.58     .07       0  478.58      .1       0   513.9    .045       0
   544.2      .1       0
Bank Sta=513.9,544.2
XS Rating Curve= 0 ,0
Exp/Cntr(USF)=0,0
Exp/Cntr=0.3,0.1

Type RM Length L Ch R = 1 ,21753   ,365.6,370.4,373.8
XS GIS Cut Line= 3
2218694.61171894464107.1587244462218949.40579555463729.540836549
2218820.04880281 463425.09458091
#Sta/Elev= 30
       0 2477.71   118.2 2475.84   171.3 2473.27   212.9 2473.28   231.6 2472.49
     263    2469   306.4 2469.79   328.1 2468.25   353.2 2468.72   398.1 2466.01
   436.7 2465.94     482    2462   503.7 2461.71   547.2 2463.92     595 2463.77
   612.4 2460.97   620.2 2457.74   630.6 2456.49   642.8 2456.81  646.012457.746
   660.2 2462.58     695 2463.12   712.4 2464.36   716.7 2465.03   728.2 2469.45
   746.5 2477.96   755.7 2483.68   764.5 2491.03   777.5 2505.06   786.3 2513.07
#Mann= 6 ,-1,0
       0     .06       0      30     .07       0     100     .05       0
     270      .1       0   620.2    .045       0  646.01      .1       0
#XS Ineff= 2 , 0
          561.46 2466.28
Permanent Ineff=
       F       F
Bank Sta=620.2,646.01
XS Rating Curve= 0 ,0
Exp/Cntr(USF)=0,0
Exp/Cntr=0.3,0.1

Type RM Length L Ch R = 1 ,21383   ,419.7,415.7,411.9
XS GIS Cut Line= 4
2219146.10640599463735.611756831 2219246.9231702463558.934598728
2219197.70303905463282.0671521562219095.13657864463227.318100572
#Sta/Elev= 30
       0 2460.36    36.5 2459.56   127.1 2455.76   173.4 2455.69   205.2 2454.09
   231.4 2453.91   237.7 2453.48     254 2450.78   262.5 2450.67   274.3 2451.81
282.38422449.227   293.5 2448.43305.58422449.225   314.9 2451.27     323 2451.88
   335.2 2451.46   352.2 2449.32   355.5 2449.31   363.6 2451.56   371.8 2452.13
   392.1 2450.16   424.6 2450.47   436.8 2451.92     453 2451.54   469.3 2454.68
   495.4 2453.27   522.6 2453.01   554.4 2456.09   586.1 2461.79   600.9 2466.12
#Mann= 3 ,-1,0
       0      .1       0282.3842    .045       0305.5842      .1       0
#XS Ineff= 2 , 0
                             480         2456.03
Permanent Ineff=
       F       F
Bank Sta=282.3842,305.5842
XS Rating Curve= 0 ,0
Exp/Cntr(USF)=0,0
Exp/Cntr=0.3,0.1

Type RM Length L Ch R = 1 ,20967   ,324.2,330.1,333.1
XS GIS Cut Line= 3
2219593.49562212463590.008951499 2219649.2326304463423.105416109
2219543.67512019463194.978109272
#Sta/Elev= 30
       0  2448.6      47 2444.95    68.3 2444.93    85.2  2442.8   100.8 2442.04
   144.3 2442.73   156.9 2443.98   173.8 2444.78   182.5 2444.71   187.3 2444.32
   200.1 2441.78   226.6 2439.31   241.5 2440.63   257.4 2439.84   266.2 2439.89
   279.5  2438.9   295.7 2440.04   301.8 2440.04322.17382436.013   331.9 2435.22
   341.2  2435.4344.97372435.919   358.8 2438.24   367.6 2445.16   377.1 2451.77
   394.1 2464.48   402.9 2471.21   411.7 2479.42   420.5 2486.99   427.3 2497.49
#Mann= 3 ,-1,0
       0      .1       0322.1738    .045       0344.9737      .1       0
Bank Sta=322.1738,344.9737
XS Rating Curve= 0 ,0
Exp/Cntr(USF)=0,0
Exp/Cntr=0.3,0.1

Type RM Length L Ch R = 1 ,20637   ,126.8,140.1,148.4
BEGIN DESCRIPTION:
structure xs 4
END DESCRIPTION:
XS GIS Cut Line= 3
2219724.88742353463406.1002903272219892.90385469463218.452430899
2219873.39996126463082.626320433
#Sta/Elev= 30
       0 2438.56      12 2438.16    22.8 2437.37    49.6 2437.77    82.3 2436.65
    96.5 2436.46     114 2434.79   124.7 2434.25   156.9 2434.65   164.4 2434.46
   172.9 2433.78   187.1 2434.16   199.9 2434.05   220.8 2432.74   242.8 2432.95
   289.5 2432.33   297.6 2431.41   309.7 2428.86   313.7 2428.04   317.8 2427.72
   321.9  2427.8   329.9 2428.86     338 2428.87   346.1 2429.34   349.1 2429.81
   354.2  2432.6   362.3 2436.39   380.9 2447.47   384.6 2449.12   389.1 2450.61
#Mann= 7 ,-1,0
       0      .1       0      20     .06       0     150      .1       0
     170     .05       0  271.88      .1       0   309.7    .045       0
   329.9      .1       0
Bank Sta=309.7,329.9
XS Rating Curve= 0 ,0
Exp/Cntr(USF)=0,0
Exp/Cntr=0.5,0.3

Type RM Length L Ch R = 1 ,20497   ,53.1,52.7,53.6
BEGIN DESCRIPTION:
structure xs 3; 16.3 ft between structure and xs
END DESCRIPTION:
XS GIS Cut Line= 5
2219776.87560831463405.786203299  2219805.394491463333.441069249
2219867.79627168463271.0392885722219973.66895575 463200.92492826
2220184.16619525 462846.28368375
#Sta/Elev= 30
       0 2436.54    60.8 2436.04    77.8 2435.63    96.9 2433.91   123.4 2434.35
   205.1 2431.93     293 2430.67   306.7 2428.44     316 2429.64   329.7 2430.15
   352.8 2428.84   358.9 2427.33   368.6 2423.24   371.8 2422.25   381.1 2421.84
   385.7 2421.91   390.72423.255   404.3 2431.53     409 2435.27   413.6 2437.67
   422.9 2439.43   455.2 2439.66   492.7 2441.38     502 2441.11   517.3 2442.09
   540.8  2442.2   586.5 2445.26   618.3 2446.26   660.2 2446.89   705.4 2444.89
#Mann= 6 ,-1,0
       0      .1       0      10     .06       0  117.76     .05       0
     293      .1       0   368.6    .045       0   390.7      .1       0
#XS Ineff= 4 ,-1
       0   223.1  2424.5   223.1  332.17 2430.64  332.17     352  2424.5
     407   705.4  2424.5
Permanent Ineff=
       F       F       F       F
Bank Sta=368.6,390.7
XS Rating Curve= 0 ,0
Exp/Cntr(USF)=0,0
Exp/Cntr=0.5,0.3

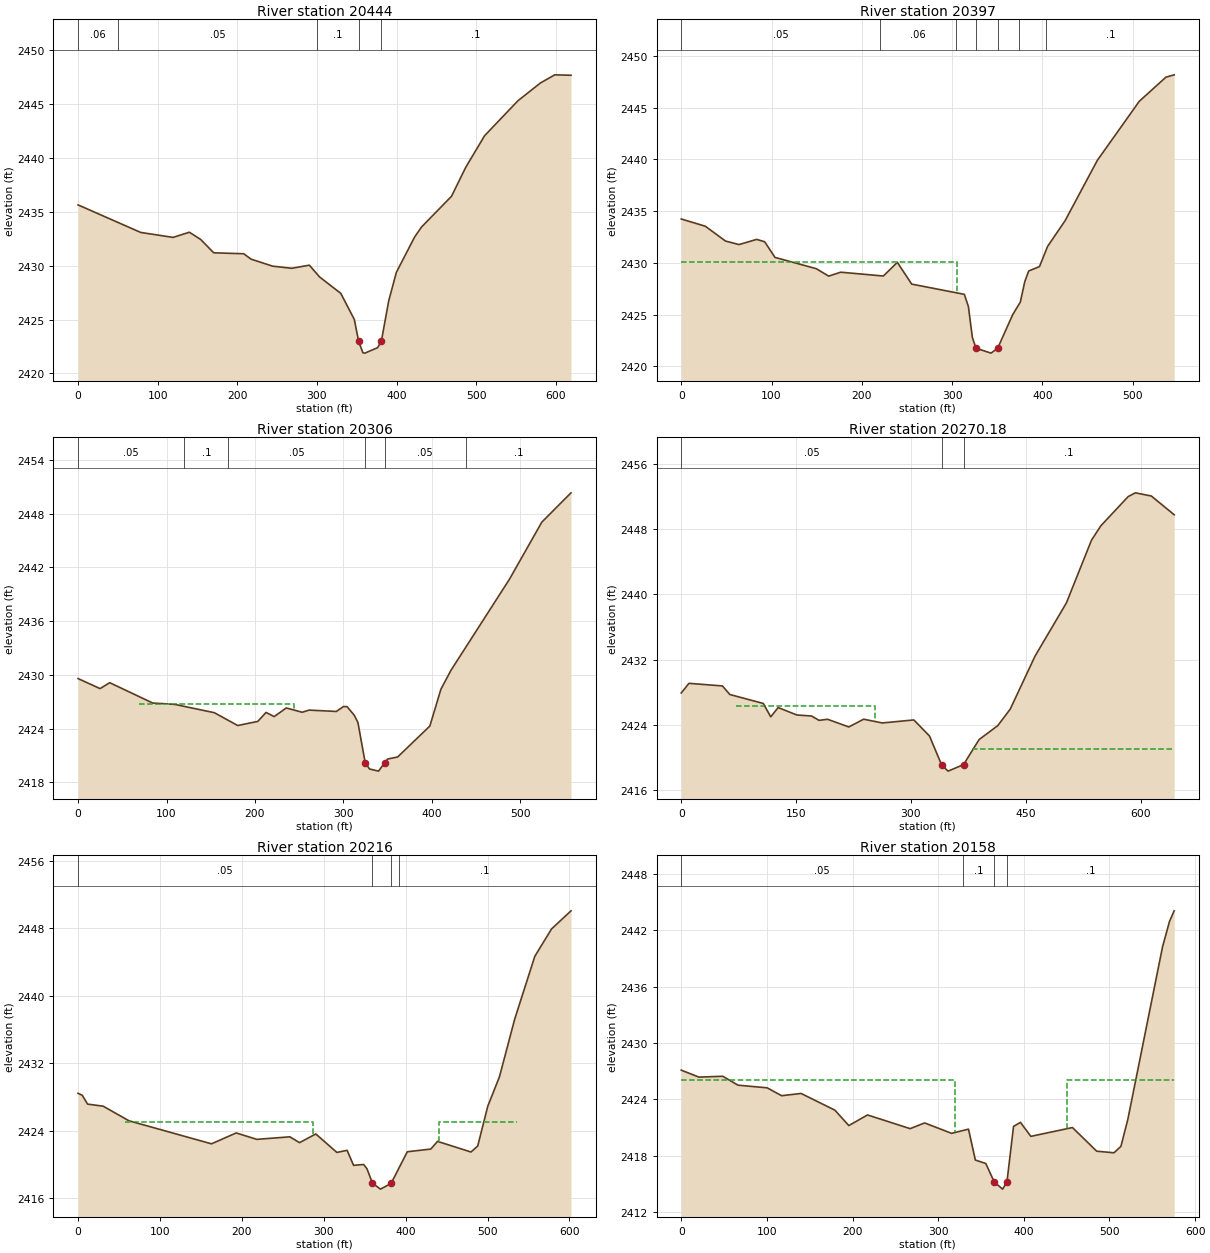
Type RM Length L Ch R = 1 ,20444   ,49.2,47.5,46.1
BEGIN DESCRIPTION:
structure xs 2; 23.6 ft between structure and xs
END DESCRIPTION:
XS GIS Cut Line= 5
2219805.29283414463389.6290560842219855.87683043463317.314766377
2219928.09462155463259.8209909222220035.36959282463200.223784657
  2220195.054831462927.585497369
#Sta/Elev= 30
       0 2435.66    78.7  2433.1   119.3 2432.64   139.8 2433.12     154 2432.45
   170.4 2431.21   208.1 2431.12   217.3 2430.62   244.3 2429.97   268.4 2429.77
   290.5 2430.06   303.3 2428.97     330 2427.44     347 2425.02   352.4    2423
   357.8 2421.92   360.3 2421.89   376.3  2422.4     381 2423.01   390.2 2426.74
   399.8 2429.39   422.7 2432.67   431.5 2433.61   469.1 2436.46   486.9 2439.14
   510.6 2442.08   552.5 2445.33   580.9 2446.99   598.8 2447.74   619.2  2447.7
#Mann= 5 ,-1,0
       0     .06       0      50     .05       0  300.56      .1       0
   352.4    .045       0     381      .1       0
#XS Ineff= 2 , 0
             344  2424.5     389          2424.5
Permanent Ineff=
       F       F
Bank Sta=352.4,381
XS Rating Curve= 0 ,0
Exp/Cntr(USF)=0,0
Exp/Cntr=0.5,0.3

Type RM Length L Ch R = 1 ,20397   ,95,90.8,86.4
BEGIN DESCRIPTION:
structure xs 1
END DESCRIPTION:
XS GIS Cut Line= 3
 2219857.0686819463379.4552936422220092.16222468463202.327215467
2220203.77663424462976.918333337
#Sta/Elev= 30
       0 2434.25    26.7 2433.55      49 2432.12      64 2431.78    83.5 2432.28
    92.4 2432.05   103.8 2430.54   149.5 2429.45   163.3 2428.73   176.6 2429.11
   223.8 2428.74   239.3 2430.06   255.2 2427.96   313.5 2426.97     318 2425.79
   322.4  2422.8   326.42421.767     343 2421.29   350.42421.759     367    2425
   375.5 2426.22   380.4 2428.19   384.8 2429.23   396.7 2429.65   405.7  2431.6
   425.1 2434.09   460.8 2439.92   507.2 2445.62   536.7 2447.95   545.9 2448.18
#Mann= 7 ,-1,0
       0     .05       0     220     .06       0  304.35      .1       0
   326.4    .045       0   350.4      .1       0  374.35     .05       0
  404.35      .1       0
#XS Ineff= 2 , 0
          305.58 2430.05
Permanent Ineff=
       F       F
Bank Sta=326.4,350.4
XS Rating Curve= 0 ,0
Exp/Cntr(USF)=0,0
Exp/Cntr=0.3,0.1

Type RM Length L Ch R = 1 ,20306   ,36.2,35.6,36
BEGIN DESCRIPTION:
structure xs 4
END DESCRIPTION:
XS GIS Cut Line= 3
2220049.29302564463502.9439710862220179.50911831463268.657170052
2220235.13590521462984.758151079
#Sta/Elev= 30
       0 2429.58    24.9 2428.46    35.8 2429.12    84.4 2426.85   109.3  2426.7
   154.1 2425.77   180.5 2424.34   203.2  2424.8   212.5  2425.8   221.7 2425.34
   235.4  2426.3   253.4 2425.82   261.2 2426.06     292 2425.91   300.1 2426.46
   304.2 2426.44   312.3 2425.48   316.4 2424.68   324.6  2420.2   329.5 2419.49
   339.7 2419.25   346.6 2420.17     350  2420.6   361.3 2420.83   397.7 2424.28
   410.2 2428.39   421.5 2430.49   487.6 2440.65   524.3 2447.04   557.3 2450.31
#Mann= 6 ,-1,0
       0     .05       0     120      .1       0     170     .05       0
   324.6    .045       0   346.6     .05       0  438.04      .1       0
#XS Ineff= 1 ,-1
   68.62  244.39 2426.75
Permanent Ineff=
       F
Bank Sta=324.6,346.6
XS Rating Curve= 0 ,0
Exp/Cntr(USF)=0,0
Exp/Cntr=0.5,0.3

Type RM Length L Ch R = 1 ,20270.18,53,53.8,55.3
BEGIN DESCRIPTION:
structure xs 3; 12.1 ft between structure and xs
END DESCRIPTION:
XS GIS Cut Line= 6
2220062.61467507463509.4973724182220214.61604646  463288.5345912
2220235.11371962463161.9242048612220229.43445644 463131.82410998
2220235.68164594463094.9088992762220274.17891747462919.600497817
#Sta/Elev= 30
       0 2427.92    10.1  2429.1    53.8 2428.78    63.5 2427.73   107.2 2426.63
   116.9 2424.99   126.6 2426.13   150.9 2425.22   170.3 2425.09     180 2424.56
   191.2 2424.69   218.9 2423.75   238.3  2424.7   262.6 2424.24   303.9 2424.61
   324.3 2422.64   340.32419.068   348.6 2418.33   368.8 2419.13   389.1  2422.2
   413.5 2423.91   429.8 2425.94   462.2 2432.44   503.2 2438.97   535.9 2446.65
   548.2 2448.43   583.9 2452.01   593.3 2452.47   614.1 2452.08     644 2449.78
#Mann= 3 ,-1,0
       0     .05       0   340.3    .045       0   368.8      .1       0
#XS Ineff= 4 ,-1
       0   71.77  2420.5   71.77  252.79 2426.31  252.79     328  2420.5
     381     644    2421
Permanent Ineff=
       F       F       F       F
Bank Sta=340.3,368.8
XS Rating Curve= 0 ,0
Exp/Cntr(USF)=0,0
Exp/Cntr=0.5,0.3

Type RM Length L Ch R = 1 ,20216   ,59.5,58.8,58.9
BEGIN DESCRIPTION:
structure xs 2; 25.2 ft between structure and xs
END DESCRIPTION:
XS GIS Cut Line= 3
2220082.32474667463522.4103954692220266.21842347463282.622175924
2220331.08708238462990.053178417
#Sta/Elev= 30
       0 2428.42     5.1 2428.19    11.6 2427.14    30.7 2426.89    62.2 2425.16
   162.9 2422.43   193.1 2423.72   218.3 2422.96   258.6 2423.26   270.4 2422.57
   290.3  2423.6     316 2421.41   328.5 2421.66   336.4 2419.88   348.7 2419.98
   352.8 2419.47   359.4 2417.78   369.2 2417.06   382.2 2417.73     402 2421.49
   430.7 2421.81   438.9 2422.72   479.8 2421.46     488 2422.18   500.3  2426.9
   514.5 2430.37   533.1  2437.2   557.7 2444.66   578.2 2447.91   601.9 2450.05
#Mann= 4 ,-1,0
       0     .05       0   359.4    .045       0   382.2     .05       0
  392.18      .1       0
#XS Ineff= 6 ,-1
       0   56.79  2420.5   56.79   287.1    2425   287.1     333  2420.5
   407.5   441.3  2420.7   441.3  535.55    2425  535.55   601.9  2420.7
Permanent Ineff=
       F       F       F       F       F       F
Bank Sta=359.4,382.2
XS Rating Curve= 0 ,0
Exp/Cntr(USF)=0,0
Exp/Cntr=0.5,0.3

Type RM Length L Ch R = 1 ,20158   ,156.3,154.6,152.8
BEGIN DESCRIPTION:
structure xs 1
END DESCRIPTION:
XS GIS Cut Line= 3
2220106.10557154463520.7926228122220329.79842442463279.240924003
2220367.10617053  463035.7169664
#Sta/Elev= 30
       0  2427.1    20.7 2426.36    48.5 2426.45    66.3  2425.5   100.3 2425.22
   117.2 2424.38   139.9 2424.62   179.4 2422.84   195.7  2421.2   217.5 2422.33
   267.3 2420.87   284.2 2421.48   315.7 2420.37   335.4 2420.82   343.4 2417.53
   355.6 2417.16   365.5 2415.19   375.2 2414.43   380.32415.185     388 2421.11
   396.1 2421.54   408.2 2420.05   456.8 2420.99   485.1 2418.47   505.3  2418.3
   513.4 2418.99   521.5 2421.88     562 2440.24   570.1 2442.94   575.6 2444.07
#Mann= 4 ,-1,0
       0     .05       0  329.22      .1       0   365.5    .045       0
   380.3      .1       0
#XS Ineff= 2 , 0
             320 2426.05     450            2426
Permanent Ineff=
       F       F
Bank Sta=365.5,380.3
XS Rating Curve= 0 ,0
Exp/Cntr(USF)=0,0
Exp/Cntr=0.3,0.1

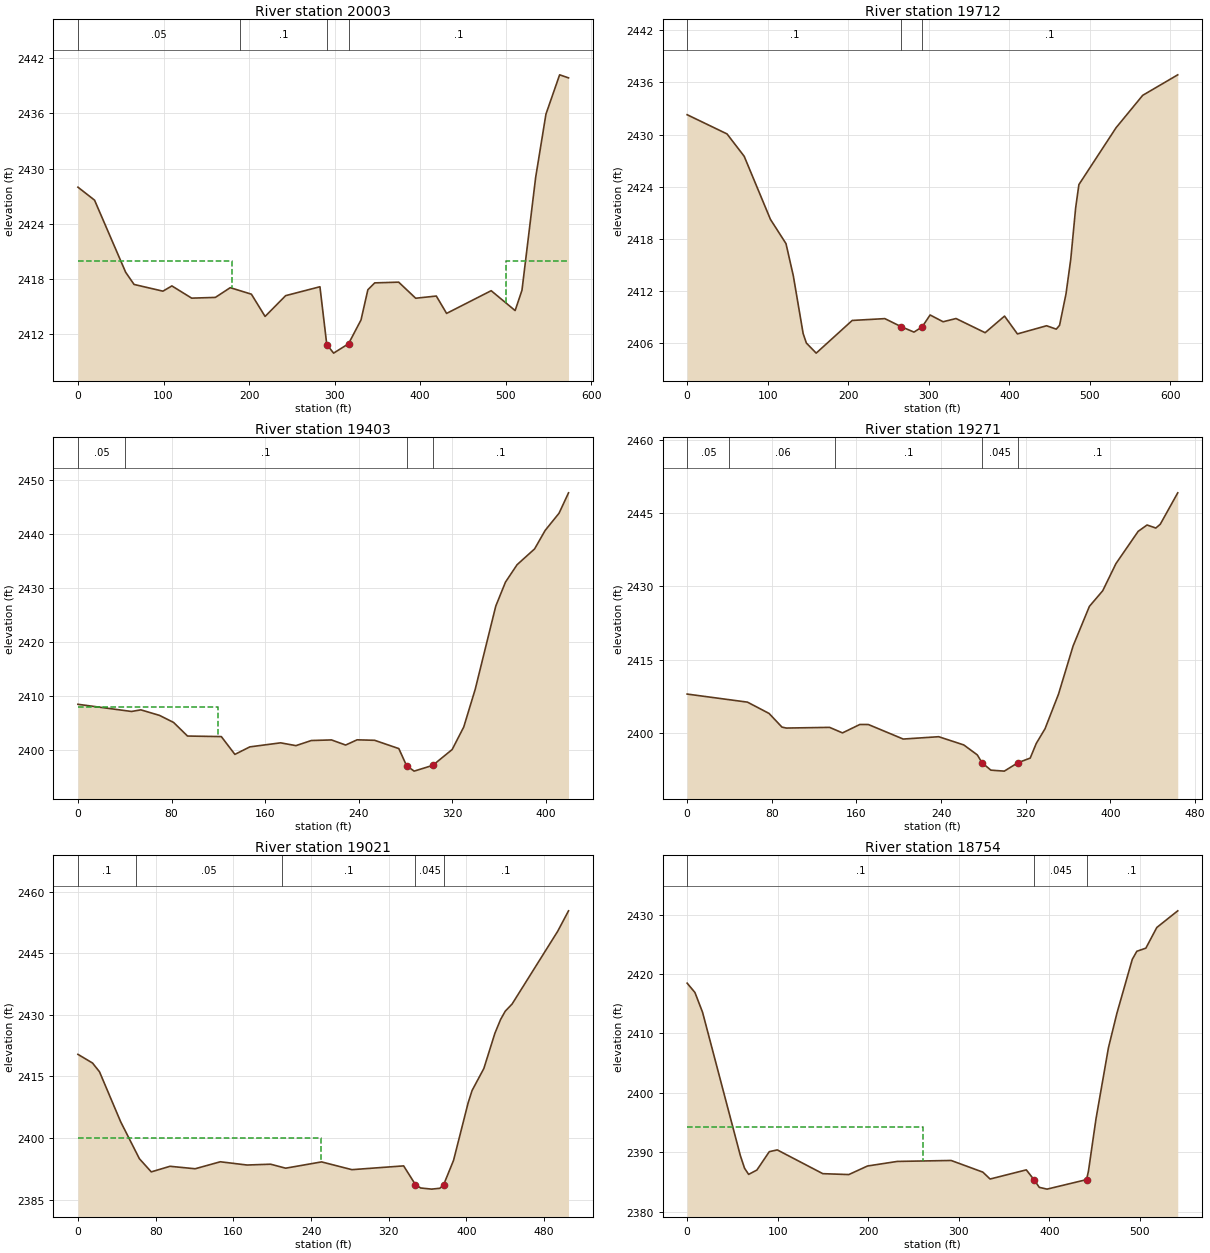
Type RM Length L Ch R = 1 ,20003   ,293,290.9,289.1
XS GIS Cut Line= 3
 2220424.2810778463579.6056122632220476.63233414463417.959627749
2220490.40898055463014.763109555
#Sta/Elev= 30
       0 2427.98    19.4 2426.57    55.8 2418.72    65.6  2417.4    99.3 2416.67
   109.8 2417.24   132.9 2415.91   160.6 2415.99     178 2417.05   202.7 2416.34
   218.7 2413.92   242.7 2416.18   282.8 2417.15   290.8 2410.86   298.8 2409.93
   316.2 2410.95   330.8 2413.54   338.8 2416.82   346.8 2417.57   374.8 2417.65
   394.7  2415.9   418.8 2416.14   430.8 2414.25   482.9 2416.72   510.9 2414.56
   518.9 2416.77   534.9 2429.05   546.9 2435.92   562.9  2440.2   573.3 2439.87
#Mann= 4 ,-1,0
       0     .05       0  189.91      .1       0   290.8    .045       0
   316.2      .1       0
#XS Ineff= 2 , 0
             180    2420     500            2420
Permanent Ineff=
       F       F
Bank Sta=290.8,316.2
XS Rating Curve= 0 ,0
Exp/Cntr(USF)=0,0
Exp/Cntr=0.3,0.1

Type RM Length L Ch R = 1 ,19712   ,311.2,309.4,304
XS GIS Cut Line= 5
2220778.04687519463541.037616537  2220805.916864 463487.89727188
 2220774.7766931463308.803951073 2220753.3679649463064.392729256
2220633.29934928463043.638999775
#Sta/Elev= 30
       0 2432.29    49.5 2430.08    70.8 2427.51   103.4 2420.25   122.7 2417.46
   131.8 2413.75     144 2407.11     148 2406.02   160.2 2404.86   204.9 2408.62
   245.4 2408.83   265.92407.896   281.6 2407.28   291.7 2407.88   301.6 2409.25
   317.7 2408.47   333.8 2408.84   369.9 2407.21     394 2409.12     410 2407.07
   446.2 2408.01   458.2 2407.62   462.3 2408.06   470.3 2411.68   476.2 2415.66
   482.3 2421.59   486.3 2424.25   532.5  2430.8   565.5 2434.52     609 2436.88
#Mann= 3 ,-1,0
       0      .1       0   265.9    .045       0   291.7      .1       0
Bank Sta=265.9,291.7
XS Rating Curve= 0 ,0
Exp/Cntr(USF)=0,0
Exp/Cntr=0.3,0.1

Type RM Length L Ch R = 1 ,19403   ,132.2,131.6,131.2
XS GIS Cut Line= 4
2221082.80477607463338.9735216792221084.64166226463245.292326108
2221005.65555619463142.4266995982220954.22274294462953.227422268
#Sta/Elev= 30
       0 2408.47    45.8 2407.14    53.8 2407.44    69.8 2406.41    81.8  2405.1
    93.7 2402.58   122.6 2402.48   134.2 2399.18     147 2400.57   173.3 2401.32
   186.4  2400.8   199.6 2401.75   216.8 2401.86   228.9 2400.91   238.7 2401.88
   253.7 2401.79   274.4 2400.25     281 2397.09   287.5 2396.07   303.4 2397.14
     320 2400.08   329.9 2404.26   339.7 2411.25   357.3  2426.7   365.6 2431.15
   375.5 2434.37   390.5 2437.31   399.5 2440.73   411.4 2443.93   419.5 2447.71
#Mann= 4 ,-1,0
       0     .05       0      40      .1       0     281    .045       0
   303.4      .1       0
#XS Ineff= 2 , 0
             120    2408
Permanent Ineff=
       F       F
Bank Sta=281,303.4
XS Rating Curve= 0 ,0
Exp/Cntr(USF)=0,0
Exp/Cntr=0.3,0.1

Type RM Length L Ch R = 1 ,19271   ,259,249.6,244.7
XS GIS Cut Line= 3
2221106.92844118463336.9539025982221146.41835102463145.875263865
2221066.85414547462889.449836468
#Sta/Elev= 30
       0 2407.97      57 2406.32    77.4 2404.01    89.6 2401.21    93.7 2401.02
   134.6 2401.16   146.8 2400.03   163.2 2401.75   171.3 2401.74   204.2 2398.77
   237.7 2399.25   261.4 2397.57   274.2 2395.53  278.652393.932     287 2392.41
   299.7 2392.21   312.5 2393.92   324.2 2394.88   329.9 2397.87   338.2 2400.88
   350.9 2407.94   364.7  2417.8   380.1  2425.9   392.7  2429.1   405.2 2434.65
   426.2 2441.25   434.6 2442.55   442.9 2441.93   447.1 2442.71   463.6 2449.13
#Mann= 5 ,-1,0
       0     .05       0      40     .06       0     140      .1       0
  278.65    .045       0   312.5      .1       0
Bank Sta=278.65,312.5
XS Rating Curve= 0 ,0
Exp/Cntr(USF)=0,0
Exp/Cntr=0.3,0.1

Type RM Length L Ch R = 1 ,19021   ,271.6,267.9,262.3
XS GIS Cut Line= 3
2221540.14831744463162.3420581322221365.68524898462950.472092987
2221208.63147993462781.478563721
#Sta/Elev= 30
       0 2420.38      15 2418.27    22.2 2416.14      44 2403.96    63.3 2394.96
    75.5 2391.76    94.8 2393.12   120.7 2392.52   146.6 2394.22   174.1 2393.43
   198.4 2393.63   213.9 2392.66   250.9 2394.19   282.1  2392.3   335.4 2393.22
   347.5 2388.68   352.9 2387.84   364.2 2387.56   372.7 2387.77   376.6 2388.64
   386.8 2394.57   401.8 2408.56   405.9 2411.59     418 2416.94   429.4 2425.53
   435.3  2428.9     440 2430.88   447.1 2432.64   494.1 2450.37   505.2 2455.33
#Mann= 5 ,-1,0
       0      .1       0      60     .05       0     210      .1       0
   347.5    .045       0   376.6      .1       0
#XS Ineff= 2 , 0
             250    2400
Permanent Ineff=
       F       F
Bank Sta=347.5,376.6
XS Rating Curve= 0 ,0
Exp/Cntr(USF)=0,0
Exp/Cntr=0.3,0.1

Type RM Length L Ch R = 1 ,18754   ,245.6,244.8,242.3
XS GIS Cut Line= 4
2221683.60593378463008.7658919862221633.02472887462916.349601621
2221598.35091799462772.042906796 2221367.9895689 462599.30044544
#Sta/Elev= 30
       0 2418.45     8.6 2416.88      17 2413.56    58.8 2389.41    63.4 2387.31
    67.9 2386.28      77 2387.01    90.7  2390.1    99.5  2390.4   149.8  2386.4
   178.5 2386.25   199.1 2387.69     232 2388.46   291.5 2388.62   326.5 2386.66
   334.5  2385.5   374.5 2387.04   383.42385.309   388.8  2384.1   397.4  2383.8
     4412385.399   443.1 2386.81   451.5 2395.68   465.2 2407.59   474.5 2413.37
   491.5 2422.45   496.5 2423.81   506.5 2424.34   518.6 2427.82   541.7 2430.62
#Mann= 3 ,-1,0
       0      .1       0   383.4    .045       0     441      .1       0
#XS Ineff= 2 , 0
          260.96 2394.21
Permanent Ineff=
       F       F
Bank Sta=383.4,441
XS Rating Curve= 0 ,0
Exp/Cntr(USF)=0,0
Exp/Cntr=0.3,0.1

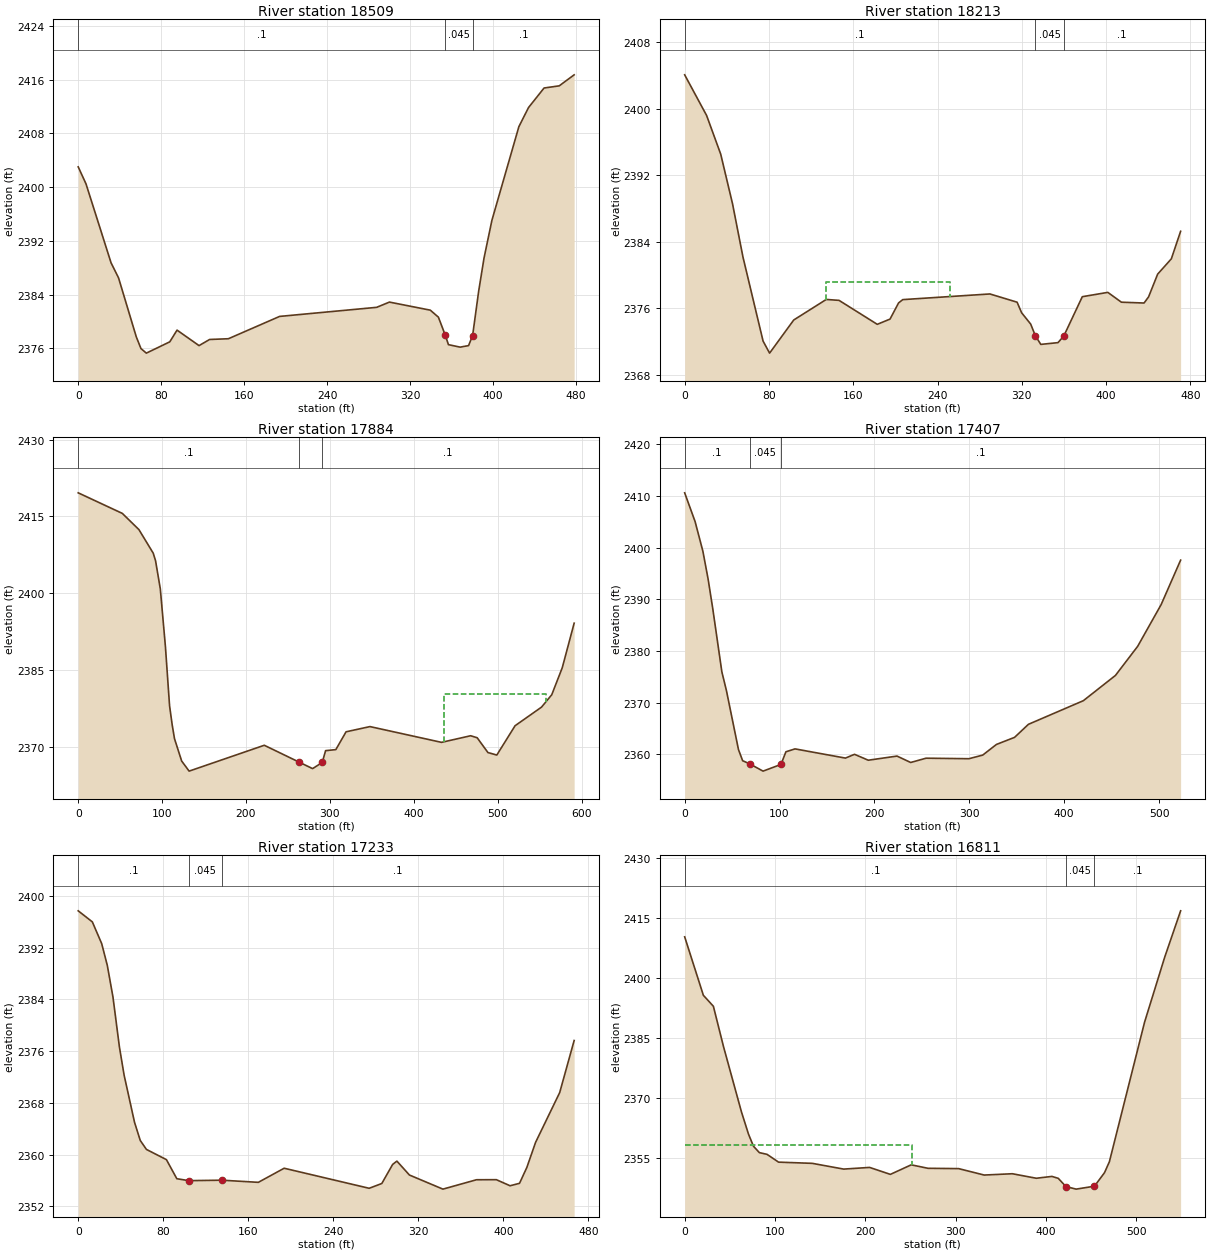
Type RM Length L Ch R = 1 ,18509   ,284.2,295.4,311.4
XS GIS Cut Line= 2
2221910.32200362462683.2051526812221516.30991636    462412.26444
#Sta/Elev= 30
       0 2403.01     7.5 2400.49    31.7 2388.73    38.9  2386.5      56 2377.73
    60.5 2375.99    65.7 2375.31    88.3 2376.99    95.3 2378.73   116.5 2376.43
   126.7 2377.34   144.8 2377.45   194.2 2380.77   287.8 2382.12   300.1  2382.9
   339.5  2381.7   347.3 2380.66   353.9 2377.99     357 2376.57   368.3  2376.2
   376.4 2376.43   380.32377.927   386.1 2384.49   391.3 2389.45   398.9 2395.06
   424.9 2408.99   434.2 2411.83   449.2 2414.74   463.8 2415.06   478.2  2416.7
#Mann= 3 ,-1,0
       0      .1       0   353.9    .045       0   380.3      .1       0
Bank Sta=353.9,380.3
XS Rating Curve= 0 ,0
Exp/Cntr(USF)=0,0
Exp/Cntr=0.3,0.1

Type RM Length L Ch R = 1 ,18213   ,323.7,329,331.1
XS GIS Cut Line= 4
2221972.61095675462621.5879043322221894.12787514 462516.08530513
2221877.57772211462390.238638992 2221799.1795447462192.936559157
#Sta/Elev= 30
       0 2404.07    20.8 2399.19    34.2 2394.54    45.4 2388.59    55.3 2382.19
    74.4 2372.08    80.6 2370.63   103.5 2374.61   134.4 2377.08   146.5 2376.97
   182.8 2374.09   194.9 2374.72     203 2376.66     207 2377.06   289.7 2377.74
   315.5 2376.75   319.8 2375.48   328.4 2374.12   332.8 2372.73     338 2371.68
   354.3 2371.89   359.82372.679   377.4 2377.41   401.6 2377.93   414.5 2376.75
     436 2376.65   440.3 2377.39   448.9 2380.12   461.9 2381.96   470.7 2385.27
#Mann= 3 ,-1,0
       0      .1       0   332.8    .045       0   359.8      .1       0
#XS Ineff= 1 ,-1
  134.08  251.83 2379.13
Permanent Ineff=
       F
Bank Sta=332.8,359.8
XS Rating Curve= 0 ,0
Exp/Cntr(USF)=0,0
Exp/Cntr=0.3,0.1

Type RM Length L Ch R = 1 ,17884   ,492.8,477.4,460.9
XS GIS Cut Line= 4
2222307.85068161462383.8376633182222152.79098039462237.760252172
2222114.55586443462027.9527393942221959.62366242461971.579224189
#Sta/Elev= 30
       0  2419.6    52.6 2415.58    72.4 2412.41    89.4 2407.82    92.2 2406.34
    97.9 2400.81     104 2389.49   108.9 2378.02     112 2374.31   114.8 2371.57
   123.3 2367.22   132.2 2365.24   221.8 2370.29   263.7 2366.97   279.4 2365.73
   290.9 2366.93   294.9 2369.24   307.1 2369.44   319.3 2372.92   347.8 2373.94
   433.1 2370.86   467.8 2372.15   475.6 2371.76   488.4 2368.87     499 2368.38
   520.8 2374.11   552.3 2377.74   564.5 2380.16     577 2385.42   591.2 2394.14
#Mann= 3 ,-1,0
       0      .1       0   263.7    .045       0   290.9      .1       0
#XS Ineff= 1 ,-1
  436.39   557.8 2380.31
Permanent Ineff=
       F
Bank Sta=263.7,290.9
XS Rating Curve= 0 ,0
Exp/Cntr(USF)=0,0
Exp/Cntr=0.3,0.1

Type RM Length L Ch R = 1 ,17407   ,172.7,174.4,176.4
XS GIS Cut Line= 2
2222556.66582118461999.3259844482222123.15408133461707.286258671
#Sta/Elev= 30
       0 2410.59      11 2405.02    19.2 2399.29    24.7 2393.91    29.5 2388.32
    39.2 2375.96      44 2372.36    56.7 2360.95    61.1 2358.79    68.42358.201
    82.6 2356.78   101.52358.078   106.7 2360.52   116.3 2361.08   169.4  2359.3
     179 2360.03   193.5 2358.89   223.8 2359.69   238.2 2358.45   254.4 2359.28
   299.6 2359.18   314.1 2359.88   328.6 2361.94   347.7 2363.31   362.3 2365.83
   420.2  2370.4     454 2375.28   477.4  2380.9   502.2 2388.99   522.7 2397.57
#Mann= 3 ,-1,0
       0      .1       0    68.4    .045       0   101.5      .1       0
Bank Sta=68.4,101.5
XS Rating Curve= 0 ,0
Exp/Cntr(USF)=0,0
Exp/Cntr=0.3,0.1

Type RM Length L Ch R = 1 ,17233   ,423.4,422,415.5
XS GIS Cut Line= 2
2222664.99235311461879.1373860642222310.38147458 461575.77563217
#Sta/Elev= 30
       0 2397.68    13.3 2395.97    22.1 2392.61    27.4 2389.23    32.7 2384.36
    38.8  2376.6    43.2 2372.27      53 2364.98    58.4 2362.17    64.2 2360.79
      83 2359.21    92.8 2356.26   104.1 2355.96   135.3 2356.03   169.5  2355.7
   193.8 2357.88   273.8 2354.78   285.7 2355.52   295.9 2358.47   299.9 2358.98
   311.7 2356.83   343.2 2354.65   374.8  2356.1   393.5 2356.11   406.4 2355.17
   415.3 2355.55   422.2 2358.01   430.4 2361.88   453.1 2369.58   466.7 2377.63
#Mann= 3 ,-1,0
       0      .1       0   104.1    .045       0   135.3      .1       0
Bank Sta=104.1,135.3
XS Rating Curve= 0 ,0
Exp/Cntr(USF)=0,0
Exp/Cntr=0.3,0.1

Type RM Length L Ch R = 1 ,16811   ,319.4,322.6,325.9
XS GIS Cut Line= 2
2222826.17243885461728.1107420172222445.34990131461332.432223119
#Sta/Elev= 30
       0 2410.21    20.7 2395.59    31.8 2392.84    42.9 2382.84    62.9  2366.4
    70.7 2360.84    76.2 2357.83    82.7 2356.23    91.2  2355.8     104 2353.85
   141.3 2353.55   176.1 2352.11   204.8 2352.53   227.8 2350.79   250.9 2353.18
   269.4 2352.31   303.4 2352.23   331.7 2350.62   362.8 2350.95   389.4 2349.82
   406.7 2350.28   413.7  2349.8   422.2 2347.74   433.5  2347.1   453.8 2347.83
   464.9 2351.21   470.3 2353.93   509.3 2388.88   531.5 2405.07   549.2 2416.72
#Mann= 3 ,-1,0
       0      .1       0   422.2    .045       0   453.8      .1       0
#XS Ineff= 2 , 0
          251.49 2358.08
Permanent Ineff=
       F       F
Bank Sta=422.2,453.8
XS Rating Curve= 0 ,0
Exp/Cntr(USF)=0,0
Exp/Cntr=0.3,0.1

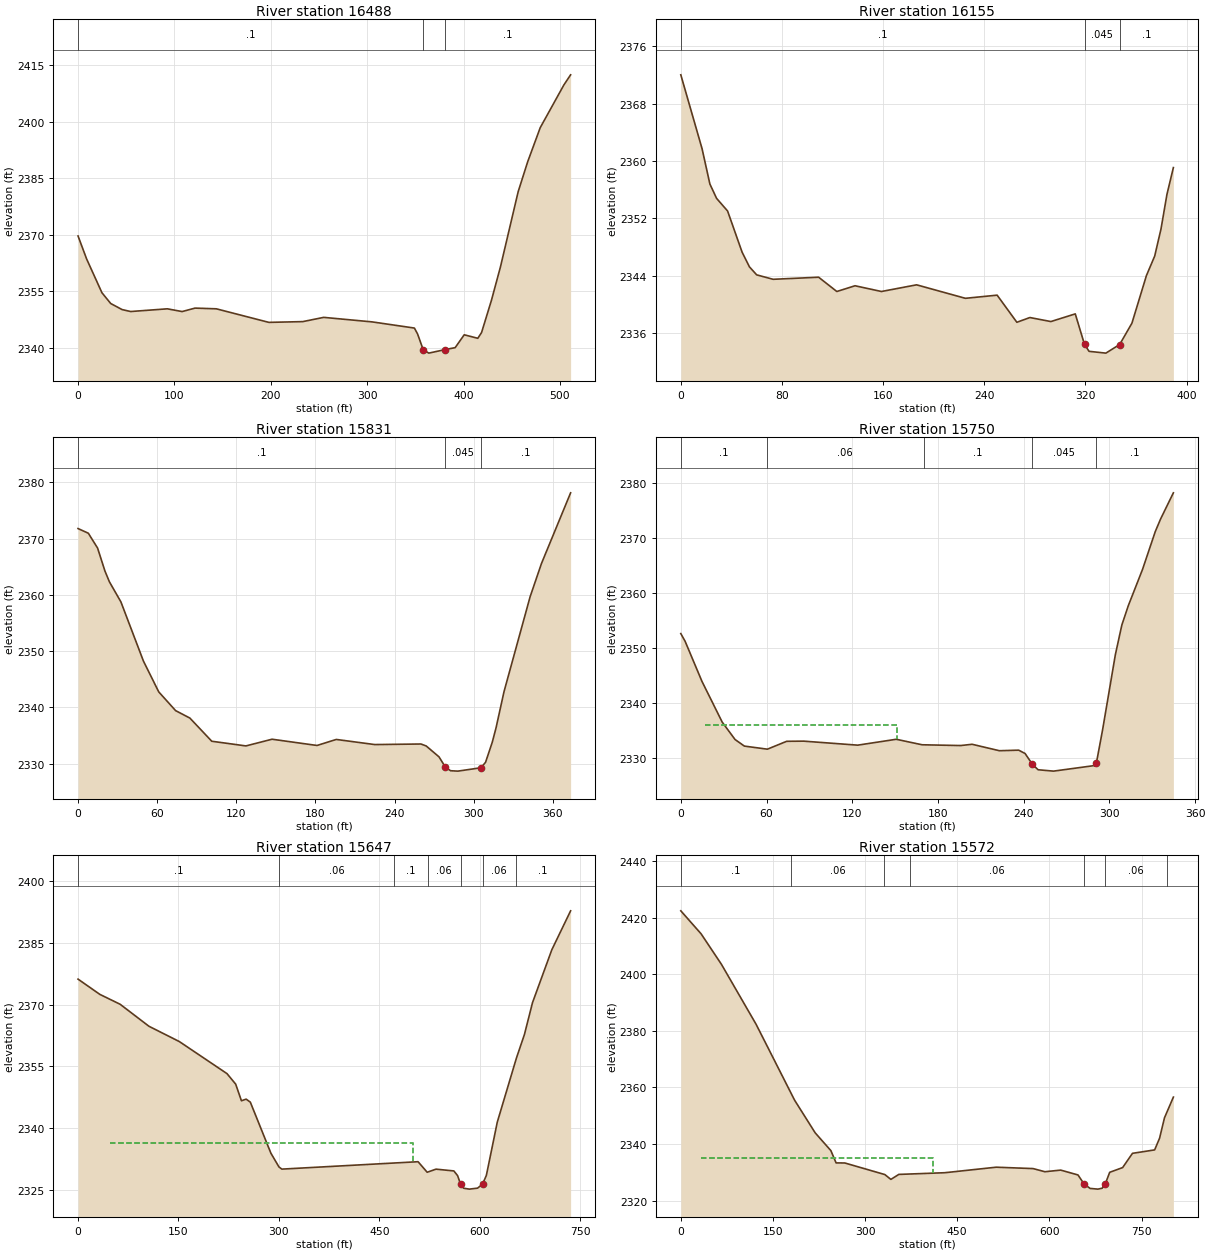
Type RM Length L Ch R = 1 ,16488   ,333.5,332.9,332.8
XS GIS Cut Line= 4
 2222891.0706759461554.2451951392222776.44925841461319.638193589
2222794.91981383461253.6719242282222699.61690697461099.167782304
#Sta/Elev= 30
       0 2369.66     8.9 2363.56    24.8 2354.58    33.9 2351.72    45.7 2350.11
    54.6 2349.59    92.7 2350.31     108 2349.58   121.4  2350.5   143.5 2350.31
     198 2346.71   233.2 2346.91   254.9 2348.04   305.1 2346.84     349  2345.2
   352.3 2343.63   358.1 2339.48   363.9 2338.54   380.5 2339.46   391.3    2340
   400.7 2343.41   414.8 2342.48   418.7 2344.01   428.9 2352.53   438.3 2361.45
   456.7 2381.45   466.5 2389.34   479.6 2398.45   504.1 2409.78   511.1 2412.47
#Mann= 3 ,-1,0
       0      .1       0   358.1    .045       0   380.5      .1       0
Bank Sta=358.1,380.5
XS Rating Curve= 0 ,0
Exp/Cntr(USF)=0,0
Exp/Cntr=0.3,0.1

Type RM Length L Ch R = 1 ,16155   ,324,323.9,324.4
XS GIS Cut Line= 2
2223209.04010193461275.6778833672222990.83184145460952.938719663
#Sta/Elev= 30
       0    2372    16.8 2361.71      23 2356.78    28.3 2354.78      37 2353.02
    48.5 2347.27    54.3 2345.23      60 2344.12      73  2343.5     109 2343.79
   123.4  2341.8   137.8  2342.6   158.7  2341.8   186.5 2342.73   225.1 2340.85
   250.2 2341.29   265.8 2337.51   276.1 2338.17   292.7 2337.61     312 2338.68
   319.3 2334.42   322.9 2333.46   336.2 2333.21   347.1 2334.41   356.8 2337.38
   368.3 2344.03   374.8 2346.73   379.8 2350.51   384.5 2355.33   389.6 2359.07
#Mann= 3 ,-1,0
       0      .1       0   319.3    .045       0   347.1      .1       0
Bank Sta=319.3,347.1
XS Rating Curve= 0 ,0
Exp/Cntr(USF)=0,0
Exp/Cntr=0.3,0.1

Type RM Length L Ch R = 1 ,15831   ,78.9,81.4,86
XS GIS Cut Line= 2
2223448.60800077461045.9258113372223235.34551438460739.257662306
#Sta/Elev= 30
       0 2371.77     7.8 2370.94    14.8 2368.31    20.4 2364.22    23.8  2362.3
    32.5 2358.74    49.6 2348.21    61.2 2342.74      74 2339.41    84.8 2338.09
   101.4 2333.97   127.3 2333.14   147.1 2334.33   181.2 2333.22   195.8 2334.29
     225 2333.38     260 2333.48     264 2333.13   273.7  2331.2   278.6 2329.34
   282.5 2328.73     288 2328.66   305.5 2329.26     309 2330.23   314.1  2333.8
     317  2336.4     323 2342.79   342.8 2359.66   351.4 2365.56   373.5 2378.12
#Mann= 3 ,-1,0
       0      .1       0   278.6    .045       0   305.5      .1       0
Bank Sta=278.6,305.5
XS Rating Curve= 0 ,0
Exp/Cntr(USF)=0,0
Exp/Cntr=0.3,0.1

Type RM Length L Ch R = 1 ,15750   ,102.7,102.9,99.4
BEGIN DESCRIPTION:
structure xs 4
END DESCRIPTION:
XS GIS Cut Line= 2
2223466.44745112460986.911263211 2223307.0378237460681.158371281
#Sta/Elev= 30
       0 2352.58       3 2351.19    14.8  2343.9      29 2336.48      38 2333.32
    44.5 2332.13    60.6 2331.57    74.1    2333      86 2333.03   123.8  2332.3
   150.8 2333.37   168.9 2332.37   195.9 2332.23   203.9 2332.46     223 2331.29
   236.5 2331.39     241 2330.78   246.1 2328.82   250.1 2327.83   260.9 2327.58
   290.4 2328.62   290.9 2329.05   295.2 2335.02   304.2 2348.77   308.7 2354.12
   313.2 2357.62   323.2 2364.25   332.1 2371.11   335.8 2373.39   344.8 2378.17
#Mann= 5 ,-1,0
       0      .1       0      60     .06       0     170      .1       0
   246.1    .045       0   290.9      .1       0
#XS Ineff= 1 ,-1
   17.15  151.24 2336.05
Permanent Ineff=
       F
Bank Sta=246.1,290.9
XS Rating Curve= 0 ,0
Exp/Cntr(USF)=0,0
Exp/Cntr=0.5,0.3

Type RM Length L Ch R = 1 ,15647   ,73.4,75.2,73
BEGIN DESCRIPTION:
structure xs 3; 25.7 ft between structure and xs
END DESCRIPTION:
XS GIS Cut Line= 4
2223419.47959676461211.400458651 2223540.2409891460912.667210955
2223392.91760333460638.3896109952223291.83823168460652.543102122
#Sta/Elev= 30
       0  2376.2    32.6 2372.49    62.8  2370.1   105.9 2364.75   151.3 2361.03
   222.4 2353.25   235.4  2350.7     244 2346.65   251.1 2347.05   257.3 2346.31
     288 2333.92   300.1 2330.57   304.4 2330.05   507.8 2331.85   521.4 2329.29
   534.6 2330.04   561.2 2329.61   566.8 2328.47571.37812326.349   575.9 2325.41
   584.4 2325.19   596.6 2325.43604.15512326.404   609.8 2328.54   626.1 2341.47
   654.6 2356.99   666.6 2362.74   678.7 2370.49   707.5 2383.32   735.6 2392.79
#Mann= 7 ,-1,0
       0      .1       0     300     .06       0  472.22      .1       0
  522.22     .06       0571.3781    .045       0604.1551     .06       0
  653.56      .1       0
#XS Ineff= 4 ,-1
       0   46.99  2326.9   46.99     500 2336.51     500     546  2326.9
     630     700  2329.2
Permanent Ineff=
       F       F       F       F
Bank Sta=571.3781,604.1551
XS Rating Curve= 0 ,0
Exp/Cntr(USF)=0,0
Exp/Cntr=0.5,0.3

Type RM Length L Ch R = 1 ,15572   ,59.4,55.9,53.6
BEGIN DESCRIPTION:
structure xs 2; 23.6 ft between structure and xs
END DESCRIPTION:
XS GIS Cut Line= 6
 2223840.3941262461158.1930398992223550.69010259460872.004492567
2223511.25503537460800.849914751 2223504.3967628460697.975826342
2223448.16479896 460593.620331782223357.68468064460588.334596904
#Sta/Elev= 30
       0 2422.39      33 2414.27      66 2403.54   122.6 2382.28   185.3 2355.45
   218.8 2343.92   244.3 2337.65   252.8 2333.31     267 2333.28   332.1 2329.19
     342 2327.48   354.9 2329.24   429.9 2329.84   513.4 2331.79   573.5  2331.3
   592.7 2330.19   618.5 2330.76   646.6 2329.05656.34952325.903   666.3 2324.29
   679.1 2324.04     686 2324.37690.94272325.824   698.2 2329.98   719.3 2331.66
   735.3 2336.69   771.4  2337.9   779.4 2342.02   787.4 2349.24   801.9 2356.56
#Mann= 7 ,-1,0
       0      .1       0     180     .06       0     330     .05       0
  373.53     .06       0656.3495    .045       0690.9427     .06       0
  791.28      .1       0
#XS Ineff= 3 ,-1
   33.13     410 2334.89     410     648  2326.9     699   801.9  2328.4
Permanent Ineff=
       F       F       F
Bank Sta=656.3495,690.9427
XS Rating Curve= 0 ,0
Exp/Cntr(USF)=0,0
Exp/Cntr=0.5,0.3