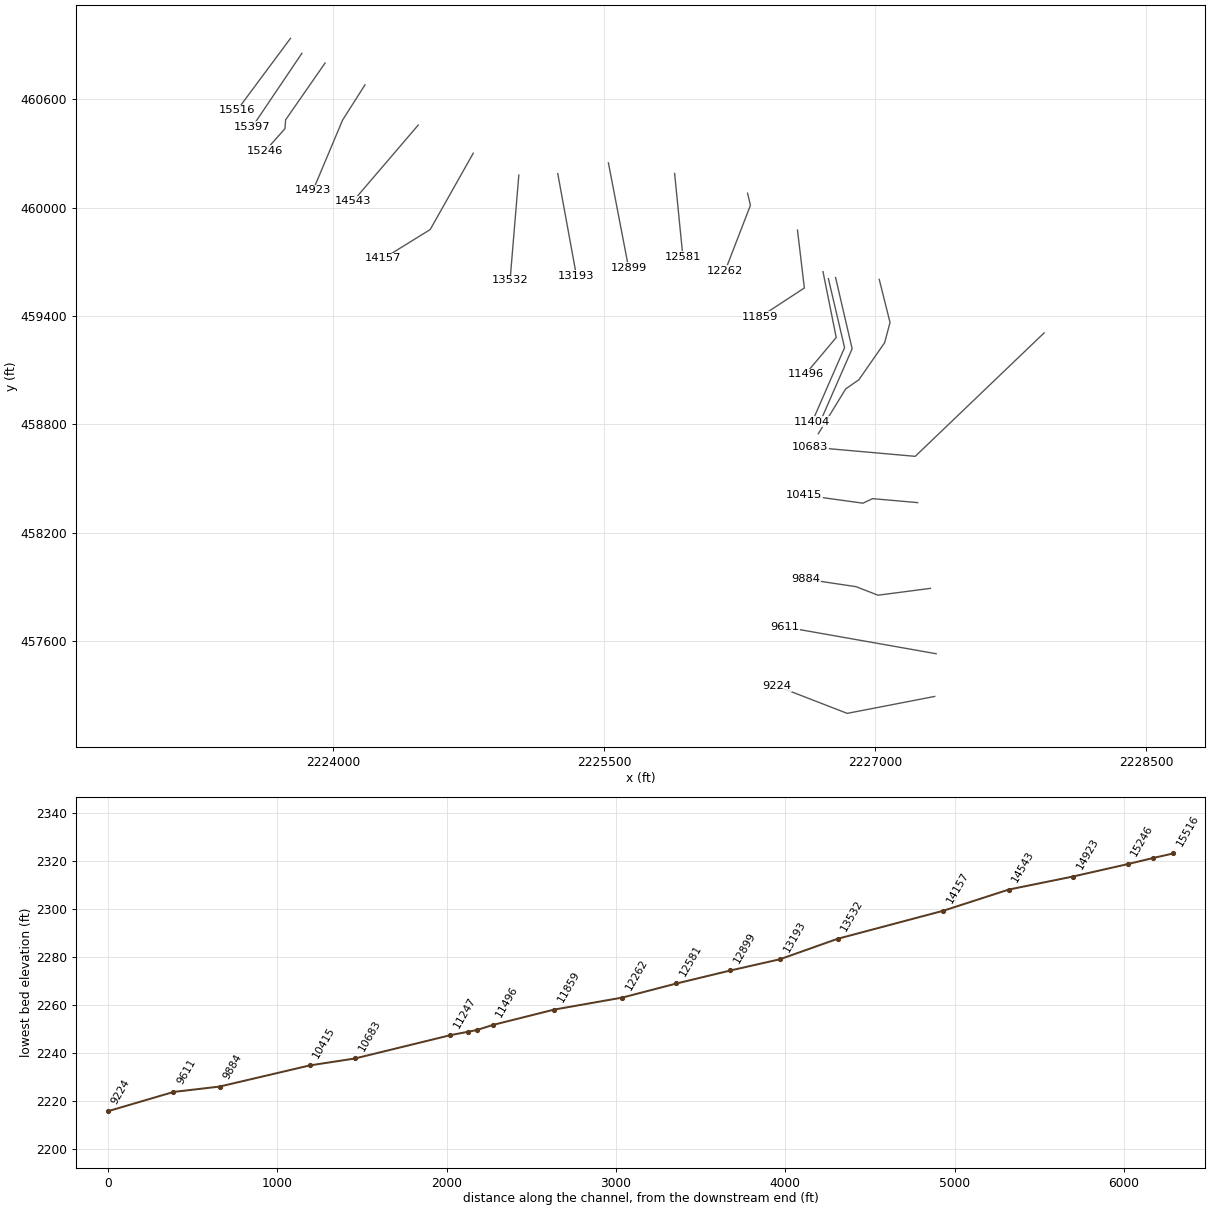
HEC-RAS study STONYCK.prj: STONYCK

--- STONYCK.g01 (geometry) --- (continued)

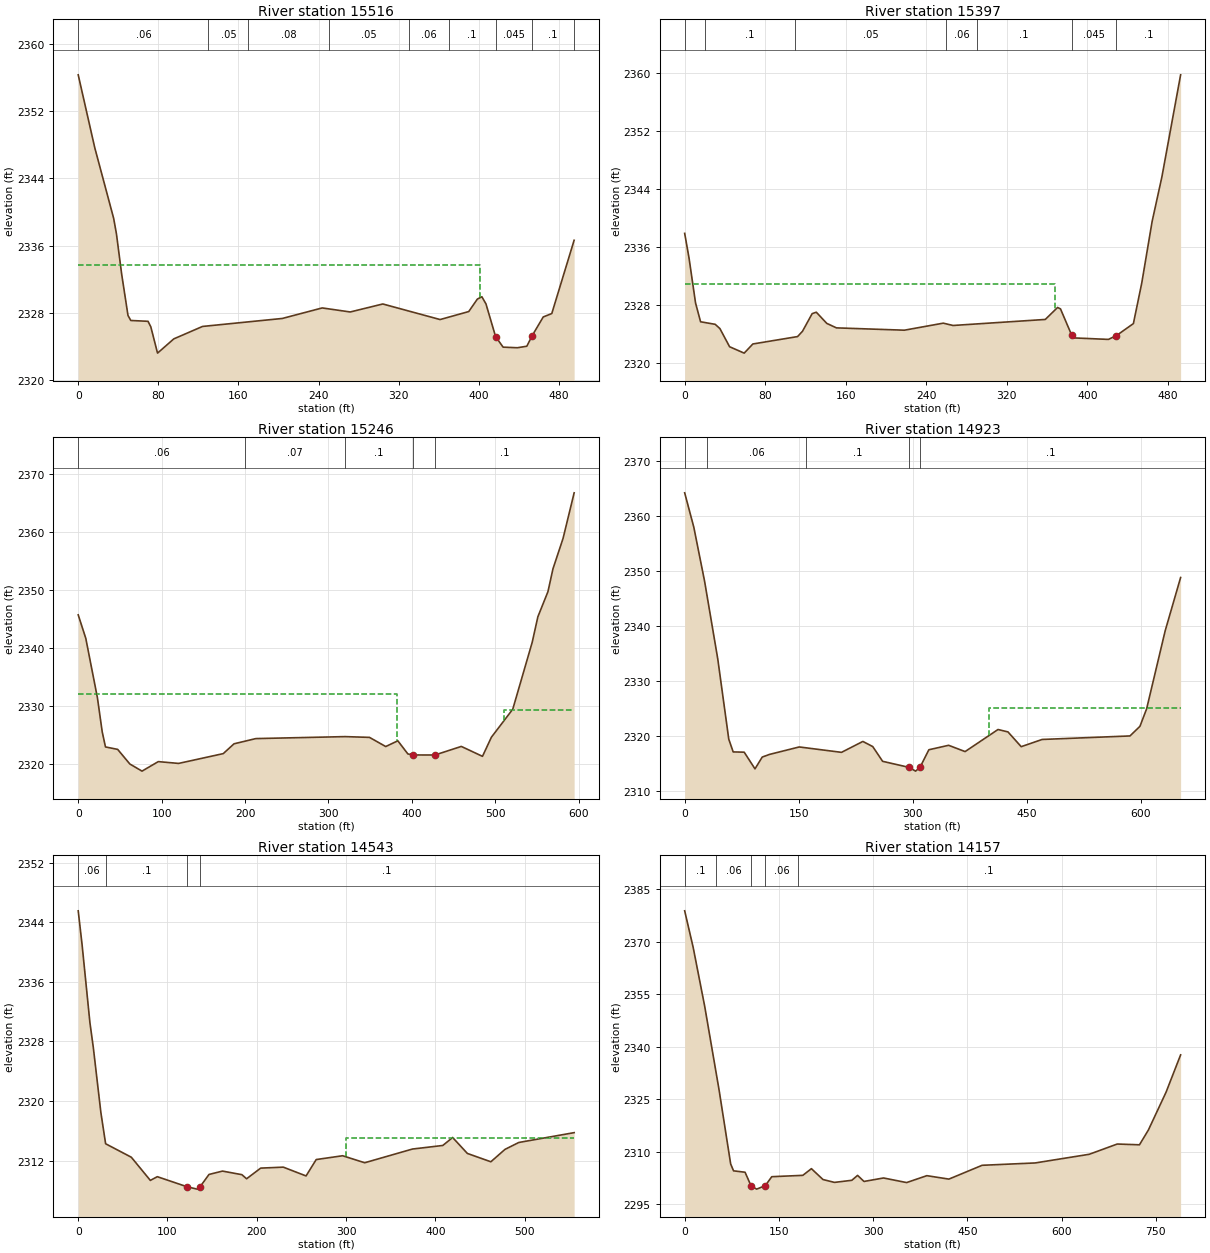
Type RM Length L Ch R = 1 ,15516   ,117.4,119.2,121.4
BEGIN DESCRIPTION:
structure xs 1
END DESCRIPTION:
XS GIS Cut Line= 2
  2223766.021934 460936.814771792223470.92616795460539.220756469
#Sta/Elev= 30
       0 2356.31    16.5 2347.66    35.4 2339.25    38.2 2337.39    43.4 2332.61
    49.7 2327.72    52.5 2327.12    69.7 2327.02    72.5 2326.36    79.2 2323.24
    95.4 2324.93   124.1 2326.41   203.8 2327.36   243.6 2328.61   271.6 2328.13
   304.1 2329.08   361.3 2327.23   389.9 2328.18   398.5 2329.66     403 2329.94
   407.1 2329.09   416.72325.209   424.2 2323.95   438.5 2323.88   447.9 2324.06
   452.8 2325.22   452.8 2325.23   464.3 2327.54   472.8 2327.94   495.1 2336.65
#Mann= 9 ,-1,0
       0     .06       0     130     .05       0     170     .08       0
     250     .05       0     330     .06       0     370      .1       0
   416.7    .045       0   452.8      .1       0  495.14     .06       0
#XS Ineff= 2 , 0
          401.16 2333.76
Permanent Ineff=
       F       F
Bank Sta=416.7,452.8
XS Rating Curve= 0 ,0
Exp/Cntr(USF)=0,0
Exp/Cntr=0.3,0.1

Type RM Length L Ch R = 1 ,15397   ,134.9,150.4,159.9
XS GIS Cut Line= 2
2223829.18179178460854.1730356312223553.96395658460445.725012554
#Sta/Elev= 30
       0 2337.84     4.3 2334.47    10.8 2328.25    15.8 2325.66    30.3 2325.31
      35 2324.72    44.6 2322.22    59.1 2321.34    67.7  2322.6   112.1 2323.62
     117 2324.35   126.6 2326.78   130.7 2326.98   141.1 2325.44   150.7 2324.82
   218.2  2324.5   256.8 2325.47   266.5 2325.15   358.1 2325.98   370.3 2327.63
   373.2 2327.44   384.32323.827   387.6 2323.43   420.8 2323.23   428.8 2323.76
   445.6 2325.41   453.9 2330.99   464.2 2339.48   473.9 2345.62   492.5 2359.69
#Mann= 7 ,-1,0
       0     .06       0      20      .1       0     110     .05       0
     260     .06       0     290      .1       0   384.3    .045       0
   428.8      .1       0
#XS Ineff= 2 , 0
          367.94 2330.93
Permanent Ineff=
       F       F
Bank Sta=384.3,428.8
XS Rating Curve= 0 ,0
Exp/Cntr(USF)=0,0
Exp/Cntr=0.3,0.1

Type RM Length L Ch R = 1 ,15246   ,307.7,323.3,298
XS GIS Cut Line= 4
2223957.33749847460800.0389168382223739.15188346460485.787593637
2223735.43777898460436.7225071972223627.30434473460314.948879596
#Sta/Elev= 30
       0 2345.74     9.1 2341.68      23 2331.47    28.8 2325.55    32.7 2322.96
    47.3 2322.54    61.9 2320.02    76.5 2318.79      96 2320.43   120.4 2320.12
   173.9 2321.81   186.8  2323.5   212.9  2324.4     320 2324.74   349.2 2324.61
   368.7 2323.03   383.2 2324.02   395.2 2321.76   400.8 2321.58   427.7 2321.57
   459.3 2323.05   484.7 2321.34   495.4 2324.64     521 2329.47   544.3    2341
   551.1 2345.41   563.2 2349.74   569.2 2353.68   581.3 2358.92   594.6 2366.78
#Mann= 5 ,-1,0
       0     .06       0     200     .07       0     320      .1       0
   400.8    .045       0   427.7      .1       0
#XS Ineff= 2 , 0
          382.72  2332.1  510.47         2329.38
Permanent Ineff=
       F       F
Bank Sta=400.8,427.7
XS Rating Curve= 0 ,0
Exp/Cntr(USF)=0,0
Exp/Cntr=0.3,0.1

Type RM Length L Ch R = 1 ,14923   ,366.9,379.9,361
XS GIS Cut Line= 3
2224178.14424054460679.2808903092224054.09872095460484.024053922
2223891.00183408460095.807520399
#Sta/Elev= 30
       0 2364.16      12 2357.93    26.2  2348.1    43.5 2334.02      58 2319.43
    63.8 2317.11    78.3 2317.06    92.5 2314.03     102 2316.17   111.5 2316.65
   150.7 2318.01   206.3 2317.03   234.4 2319.01   247.4 2318.08   260.4  2315.4
   295.2  2314.3   303.8 2313.62  309.67 2314.33   321.2  2317.5   347.2 2318.31
   368.9 2317.17   412.2 2321.18   425.3 2320.74   442.7 2318.06   470.2 2319.37
   585.8 2320.01   598.9 2321.76   607.7 2324.94   632.1 2339.11   652.4 2348.78
#Mann= 5 ,-1,0
       0      .1       0      30     .06       0     160      .1       0
   295.2    .045       0  309.67      .1       0
#XS Ineff= 2 , 0
                             400            2325
Permanent Ineff=
       F       F
Bank Sta=295.2,309.67
XS Rating Curve= 0 ,0
Exp/Cntr(USF)=0,0
Exp/Cntr=0.3,0.1

Type RM Length L Ch R = 1 ,14543   ,383.3,386.2,387.4
XS GIS Cut Line= 2
2224472.65739204460456.5341574092224111.73645493460034.302591465
#Sta/Elev= 30
       0 2345.52     4.4 2340.91    13.1 2330.53    16.9 2327.19    25.4 2318.44
    30.7 2314.26    59.5 2312.45    80.8 2309.34    88.6 2309.84   121.9 2308.49
   133.2 2308.17   136.2 2308.44   146.5 2310.14   161.6 2310.59   183.3 2310.11
   188.6 2309.56   204.4 2310.99   229.7 2311.12   255.2 2309.94   266.6 2312.14
   296.2 2312.65   320.9 2311.71   374.4 2313.55   408.4 2314.03   419.4  2315.1
   435.9 2312.96   462.2 2311.84     478  2313.5   493.5 2314.43   555.5 2315.75
#Mann= 4 ,-1,0
       0     .06       0    30.7      .1       0   121.9    .045       0
   136.2      .1       0
#XS Ineff= 2 , 0
                             300            2315
Permanent Ineff=
       F       F
Bank Sta=121.9,136.2
XS Rating Curve= 0 ,0
Exp/Cntr(USF)=0,0
Exp/Cntr=0.3,0.1

Type RM Length L Ch R = 1 ,14157   ,614.4,624.3,626.1
XS GIS Cut Line= 3
2224777.21408758460300.9272108032224538.96500615459878.103145954
2224280.48185997 459718.16742533
#Sta/Elev= 30
       0 2378.78    13.5 2368.36    31.9  2351.5    54.8 2327.61    73.2 2306.54
    77.8 2304.58    96.1 2304.18   105.62300.321   114.5 2299.36   128.3 2300.35
   138.6 2302.91     188 2303.29   201.7  2305.2   220.1  2302.1   238.4 2301.28
     266 2301.88   275.2 2303.28   285.4 2301.55   316.5 2302.54   353.2 2301.23
   385.4  2303.2   420.5 2302.22   473.4 2306.16   557.8 2306.83   643.8  2309.3
   688.5 2312.23   723.8 2312.01     738 2316.23   766.1 2327.01   789.3 2337.67
#Mann= 5 ,-1,0
       0      .1       0      50     .06       0   105.6    .045       0
   128.3     .06       0     180      .1       0
Bank Sta=105.6,128.3
XS Rating Curve= 0 ,0
Exp/Cntr(USF)=0,0
Exp/Cntr=0.3,0.1

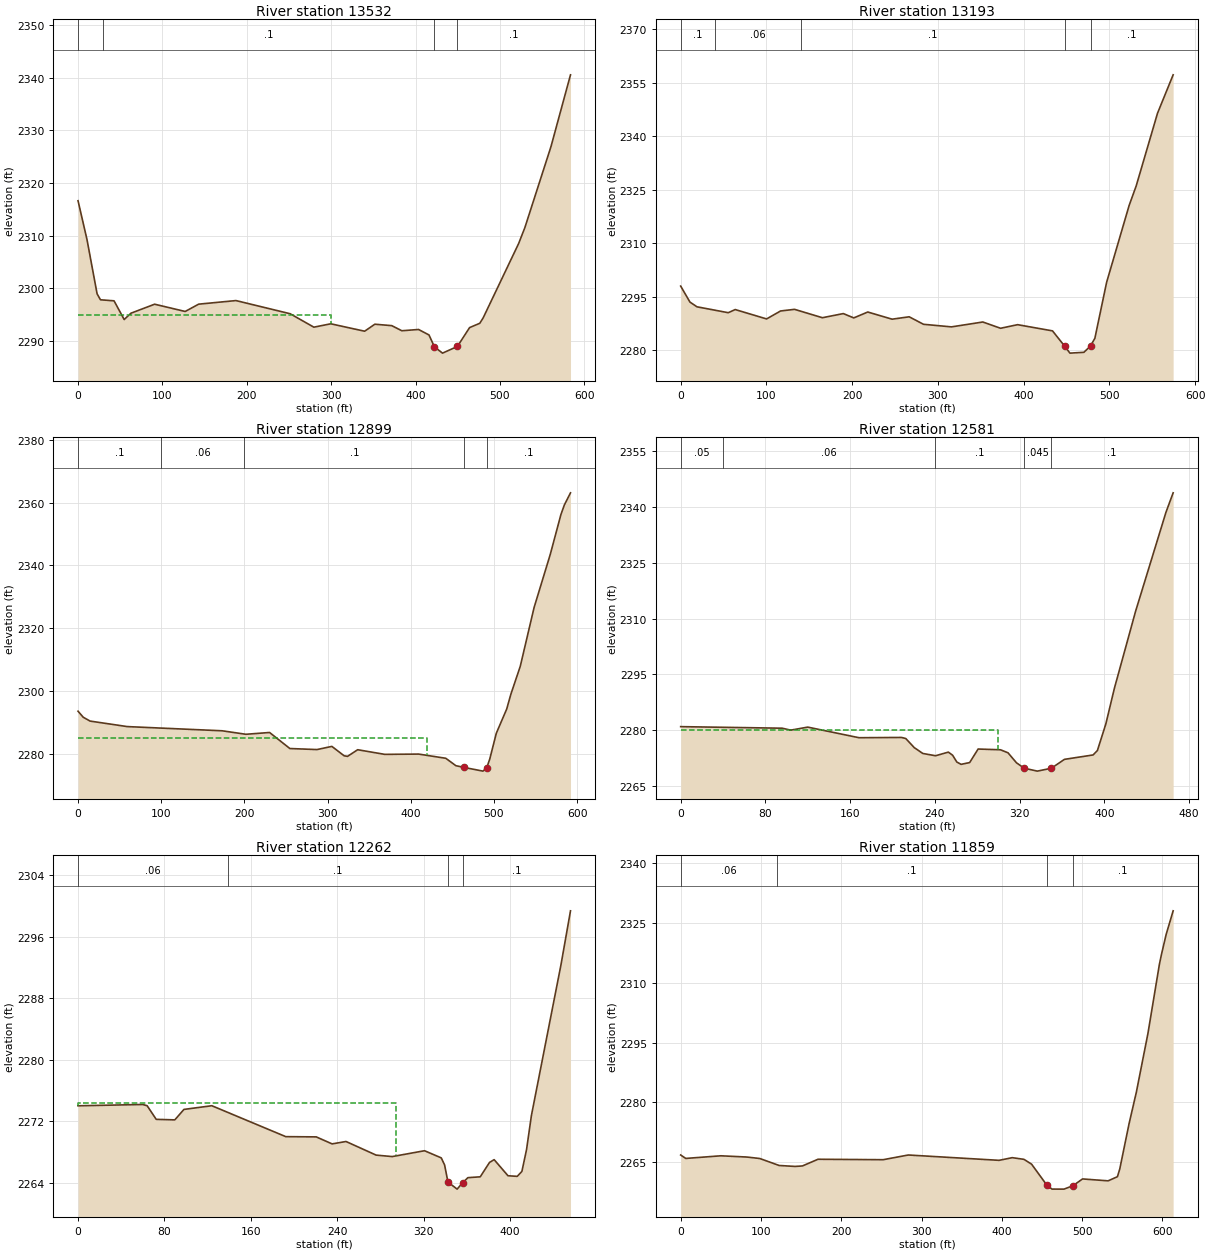
Type RM Length L Ch R = 1 ,13532   ,335.1,340,344.9
XS GIS Cut Line= 2
2225029.33047699460179.7052897142224980.89855683459598.003494402
#Sta/Elev= 30
       0 2316.61    10.6 2309.25    22.6 2298.93    26.6  2297.8    42.7  2297.6
    54.7 2294.05    62.7 2295.25    90.8 2296.96     127 2295.58     143 2296.97
   187.2 2297.65   251.4 2295.15   279.5  2292.6   299.6 2293.24   339.7 2291.83
   351.8 2293.16   371.8 2292.89   383.8 2291.92   403.6 2292.16     416 2291.12
   422.42288.862     432 2287.67   449.62288.932   464.1 2292.52   476.2 2293.34
   480.2 2294.37   522.2 2308.47   529.6  2311.5   560.5 2326.86   583.7 2340.52
#Mann= 4 ,-1,0
       0     .06       0      30      .1       0   422.4    .045       0
   449.6      .1       0
#XS Ineff= 2 , 0
             300    2295
Permanent Ineff=
       F       F
Bank Sta=422.4,449.6
XS Rating Curve= 0 ,0
Exp/Cntr(USF)=0,0
Exp/Cntr=0.3,0.1

Type RM Length L Ch R = 1 ,13193   ,293,293.1,293.2
XS GIS Cut Line= 2
2225244.72157281460187.7887506172225348.00370915459622.782976138
#Sta/Elev= 30
       0 2297.96    10.8 2293.48      19 2292.15    55.5  2290.5    63.6 2291.38
   100.2 2288.75   116.5 2290.98   132.8 2291.44   165.3 2289.09   189.7 2290.25
   201.9 2289.04   218.2 2290.69   246.6 2288.68   266.5 2289.35   283.2 2287.25
   315.8 2286.52   352.4 2287.89   373.1 2286.13     393 2287.14   433.7  2285.4
   447.92281.099     454 2279.16   470.3 2279.39     4782281.165   483.1 2283.32
   496.8 2299.02   523.1  2320.6   531.3 2326.05   556.2 2346.46   574.4 2357.21
#Mann= 5 ,-1,0
       0      .1       0      40     .06       0     140      .1       0
   447.9    .045       0     478      .1       0
Bank Sta=447.9,478
XS Rating Curve= 0 ,0
Exp/Cntr(USF)=0,0
Exp/Cntr=0.3,0.1

Type RM Length L Ch R = 1 ,12899   ,320.4,318.2,317.2
XS GIS Cut Line= 2
2225524.89938315460247.3114776912225636.77032931459665.901973718
#Sta/Elev= 30
       0 2293.56     6.2 2291.65    14.4 2290.42    59.2 2288.66   173.3 2287.32
   201.8 2286.21   230.3 2286.78   254.7 2281.67   287.3 2281.34   305.2 2282.35
   319.9 2279.36     324 2279.17   336.2 2281.29   368.8 2279.81   409.5  2279.9
   442.1 2278.57   454.3  2276.2   464.52275.632   486.9 2274.47   491.42275.557
     495  2278.3   502.9 2286.54   515.4 2294.26   520.4 2298.97   531.7 2307.87
   548.3 2326.58   567.8 2343.55   580.6 2356.24   584.7 2359.26   592.1 2363.14
#Mann= 5 ,-1,0
       0      .1       0     100     .06       0     200      .1       0
   464.5    .045       0   491.4      .1       0
#XS Ineff= 2 , 0
             420    2285
Permanent Ineff=
       F       F
Bank Sta=464.5,491.4
XS Rating Curve= 0 ,0
Exp/Cntr(USF)=0,0
Exp/Cntr=0.3,0.1

Type RM Length L Ch R = 1 ,12581   ,327.5,319.2,312.3
XS GIS Cut Line= 2
2225891.16933215460188.6068589212225937.29667608459726.007243072
#Sta/Elev= 30
       0    2281    95.9 2280.58   103.9 2280.06     120 2280.87   168.3 2278.03
   208.5  2278.1   212.5 2277.81   220.5 2275.37   228.6  2273.8   240.6 2273.19
   252.7 2274.16   256.7 2273.33   260.7  2271.5   264.7 2270.88   272.8 2271.36
   280.8 2274.99   301.9 2274.79     309 2273.98     317  2271.3   324.2 2269.85
   336.7 2269.06   349.92269.833   362.3 2272.22   389.3  2273.4   393.4 2274.59
   401.4 2281.77   409.4 2291.26   429.5 2312.02   458.1 2338.52   464.9 2343.76
#Mann= 5 ,-1,0
       0     .05       0      40     .06       0     240      .1       0
   324.2    .045       0   349.9      .1       0
#XS Ineff= 2 , 0
             300    2280
Permanent Ineff=
       F       F
Bank Sta=324.2,349.9
XS Rating Curve= 0 ,0
Exp/Cntr(USF)=0,0
Exp/Cntr=0.3,0.1

Type RM Length L Ch R = 1 ,12262   ,413.3,402.6,393.1
XS GIS Cut Line= 4
2226294.69940274460079.4670890822226310.71920277460012.582051227
2226256.40629453459871.4794167262226171.32975385459651.238610904
#Sta/Elev= 30
       0 2274.03    59.9  2274.2      64 2274.04    72.4 2272.27    89.6  2272.2
    98.1 2273.56   123.9 2274.04   192.4 2270.02   220.6 2269.99   235.3 2269.08
   248.2 2269.39   276.1 2267.62     291 2267.43   320.9 2268.19   336.4 2267.26
   339.5 2266.34   342.6 2264.12   351.1  2263.2   356.3 2264.05   361.1 2264.69
   372.5  2264.8   381.1 2266.67   385.4 2267.03   398.2 2264.94   406.8 2264.86
   411.1 2265.51   415.4 2268.35   419.9 2272.77   447.2  2292.3   456.1 2299.37
#Mann= 4 ,-1,0
       0     .06       0  138.78      .1       0   342.6    .045       0
   356.3      .1       0
#XS Ineff= 2 , 0
          294.02 2274.44
Permanent Ineff=
       F       F
Bank Sta=342.6,356.3
XS Rating Curve= 0 ,0
Exp/Cntr(USF)=0,0
Exp/Cntr=0.3,0.1

Type RM Length L Ch R = 1 ,11859   ,355.8,363,368.7
XS GIS Cut Line= 3
2226571.01527687459874.9637801662226609.07759201459554.568721966
2226365.87337929459395.428261626
#Sta/Elev= 30
       0 2266.76     6.3  2265.9    50.1 2266.56    82.4 2266.25    98.5 2265.88
   122.6 2264.13   142.4 2263.89   151.6 2264.01     171 2265.69   252.1 2265.58
   283.5 2266.76   396.5 2265.42   412.9 2266.09   427.5 2265.67     437 2264.46
   455.92259.227   462.4  2258.2   477.4 2258.19   488.62259.056   500.5 2260.75
   532.3 2260.27   543.9 2261.31   546.8 2263.23   558.4 2274.62   567.5 2282.56
   581.9 2297.28   596.2 2314.67   598.8 2317.18   604.6 2322.16   613.3 2328.08
#Mann= 4 ,-1,0
       0     .06       0     120      .1       0   455.9    .045       0
   488.6      .1       0
Bank Sta=455.9,488.6
XS Rating Curve= 0 ,0
Exp/Cntr(USF)=0,0
Exp/Cntr=0.3,0.1

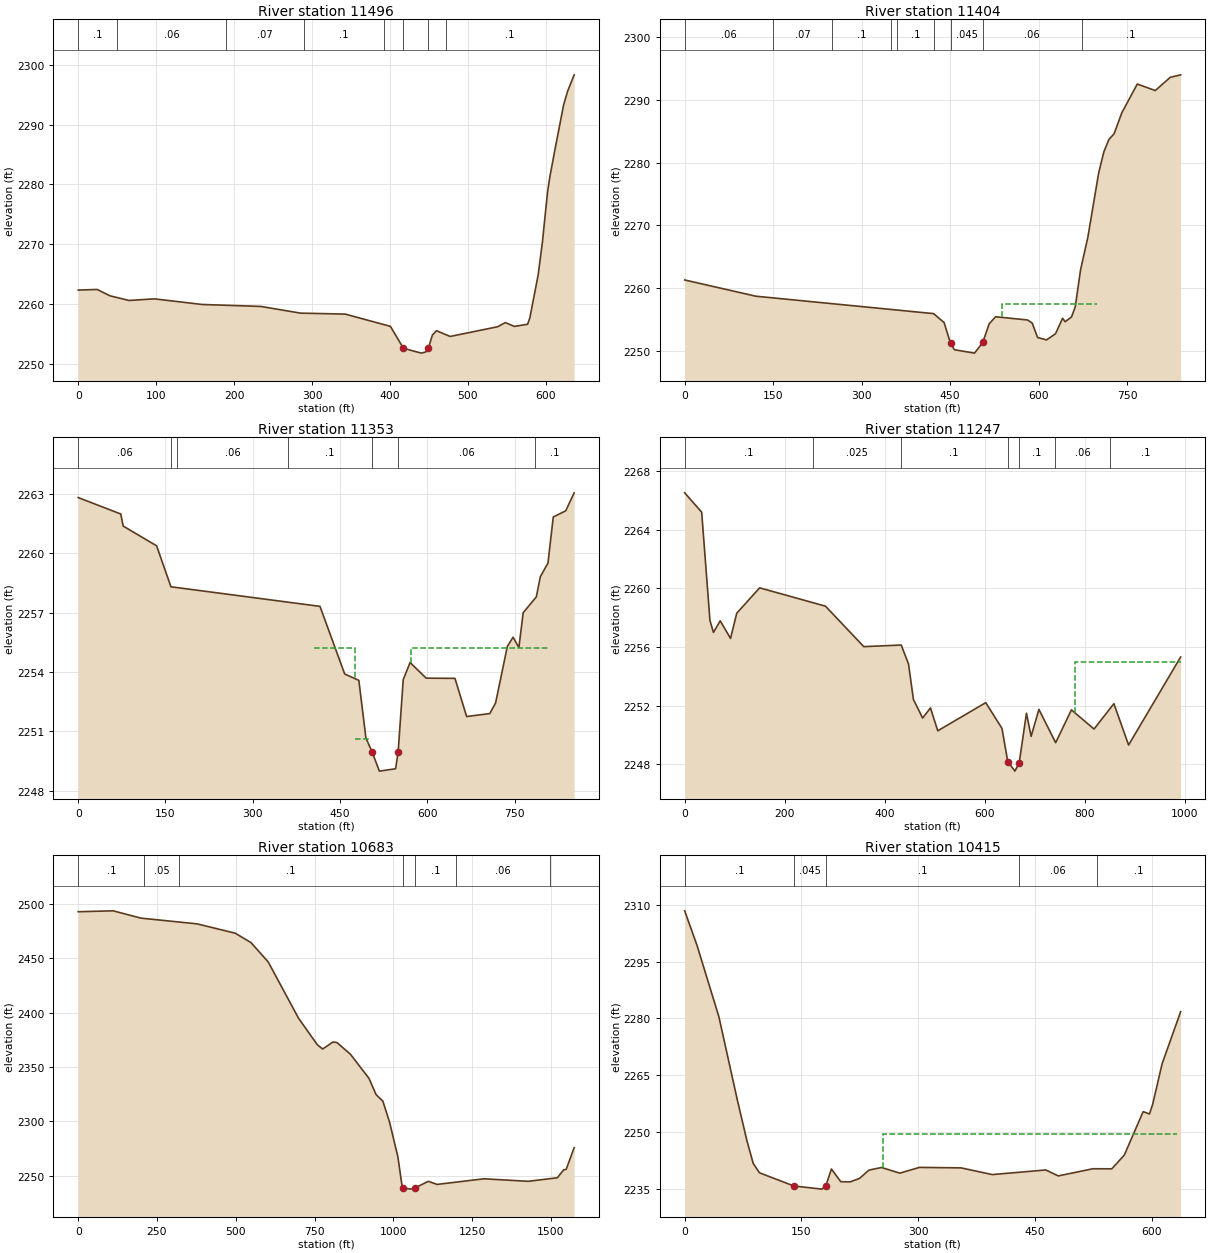
Type RM Length L Ch R = 1 ,11496   ,89.2,92.4,114.1
BEGIN DESCRIPTION:
structure xs 4
END DESCRIPTION:
XS GIS Cut Line= 3
2226712.13199622459644.9957930732226785.30362848 459280.44426808
2226615.44091074459077.915643083
#Sta/Elev= 30
       0 2262.33    24.3 2262.43    40.5 2261.38    65.1 2260.59    97.7 2260.86
   158.9 2259.92   234.3 2259.59   285.3 2258.47   342.5 2258.31   400.5 2256.26
   417.2 2252.59   440.2 2251.78   445.9 2251.98   449.2 2252.63   454.4 2254.81
   459.6 2255.53   477.2 2254.57   537.9 2256.19   547.9 2256.89   559.5 2256.25
   576.5 2256.61   579.4 2257.69   590.1 2264.92   595.4 2270.26   602.1 2278.76
   604.9 2281.16     611 2285.44   622.6 2293.25   627.6 2295.52   636.2 2298.34
#Mann= 8 ,-1,0
       0      .1       0      50     .06       0     190     .07       0
     290      .1       0  391.82     .06       0   417.2    .045       0
   449.2     .06       0  471.82      .1       0
Bank Sta=417.2,449.2
XS Rating Curve= 0 ,0
Exp/Cntr(USF)=0,0
Exp/Cntr=0.5,0.3

Type RM Length L Ch R = 1 ,11404   ,51.4,51.1,46.2
BEGIN DESCRIPTION:
structure xs 3; 14.5 ft between structure and xs
END DESCRIPTION:
XS GIS Cut Line= 3
2226741.92891883459606.5014896372226831.54732009459224.129644282
2226652.31051758458813.876518537
#Sta/Elev= 30
       0 2261.34   120.5 2258.76   421.8 2255.99   439.6 2254.57   450.52251.274
   457.1 2250.25   491.1 2249.71   505.1  2251.4     516 2254.37   526.9 2255.49
     581 2254.98   588.9 2254.49     598  2252.2   613.2 2251.81   628.4 2252.79
   640.4 2255.25   644.8  2254.7   655.5 2255.46   661.8 2257.05   670.9 2262.98
   683.1 2268.08   701.5 2278.33   710.4 2281.73     719 2283.69   727.7 2284.58
   740.7  2287.9     767 2292.49   797.5 2291.45   822.8 2293.55   840.4 2293.95
#Mann= 9 ,-1,0
       0     .06       0     150     .07       0     250      .1       0
     350     .06       0     360      .1       0  422.73     .06       0
   450.5    .045       0   505.1     .06       0  672.73      .1       0
#XS Ineff= 3 ,-1
       0     435  2250.6   519.5  538.03  2252.7  538.03  699.15 2257.55
Permanent Ineff=
       F       F       F
Bank Sta=450.5,505.1
XS Rating Curve= 0 ,0
Exp/Cntr(USF)=0,0
Exp/Cntr=0.5,0.3

Type RM Length L Ch R = 1 ,11353   ,114.2,106.2,83.2
BEGIN DESCRIPTION:
structure xs 2; 21.4 ft between structure and xs
END DESCRIPTION:
XS GIS Cut Line= 3
2226781.75931939459612.4760497212226873.36924067459218.155084199
2226694.13243816458807.901958454
#Sta/Elev= 30
       0 2262.82    73.2 2261.99    77.3 2261.38   134.8 2260.38   159.4 2258.31
   415.6 2257.32   458.1  2253.9   482.4 2253.58   494.6 2250.66   505.2 2249.96
   517.7 2248.99   545.6 2249.11     5502249.975   558.7 2253.62   570.5 2254.48
   598.2 2253.69   647.6 2253.68   667.7 2251.75   707.5  2251.9   717.5 2252.44
   737.6 2255.29   747.5 2255.76   757.5 2255.24   764.9    2257   787.5  2257.8
   794.4 2258.82   807.5 2259.51   816.6 2261.84     838 2262.15   852.5 2263.06
#Mann= 7 ,-1,0
       0     .06       0     160     .07       0     170     .06       0
     360      .1       0   505.2    .045       0     550     .06       0
  784.82      .1       0
#XS Ineff= 4 ,-1
  405.63  474.93 2255.21  474.93     498  2250.6     557  571.27  2252.7
  571.27  808.45 2255.21
Permanent Ineff=
       F       F       F       F
Bank Sta=505.2,550
XS Rating Curve= 0 ,0
Exp/Cntr(USF)=0,0
Exp/Cntr=0.5,0.3

Type RM Length L Ch R = 1 ,11247   ,582,564.2,543.4
BEGIN DESCRIPTION:
structure xs 1
END DESCRIPTION:
XS GIS Cut Line= 6
2227023.31295301459602.1203362672227083.02192379459363.739561906
 2227053.2823183459251.7395076922226910.74071235459046.556372116
2226837.56908009458995.5975567942226685.99927042458747.336661637
#Sta/Elev= 30
       0 2266.52      34  2265.2    50.5 2257.82    57.5    2257    71.1 2257.79
    91.7 2256.59   104.1 2258.31   149.9 2260.04   281.5 2258.79   358.1 2256.03
   432.9 2256.14   447.5 2254.85   457.3 2252.43   475.7 2251.16   491.4 2251.85
     506 2250.29   601.9 2252.21   634.4 2250.45   645.92248.193   660.3 2247.54
   668.82248.107   683.3 2251.49   692.6 2249.91   708.2 2251.75   741.7 2249.48
   773.2 2251.72   818.4 2250.41   858.1 2252.14   887.5 2249.32   991.5 2255.32
#Mann= 7 ,-1,0
       0      .1       0  255.74    .025       0  431.63      .1       0
   645.9    .045       0   668.8      .1       0  740.63     .06       0
  850.63      .1       0
#XS Ineff= 2 , 0
                             780            2255
Permanent Ineff=
       F       F
Bank Sta=645.9,668.8
XS Rating Curve= 0 ,0
Exp/Cntr(USF)=0,0
Exp/Cntr=0.3,0.1

Type RM Length L Ch R = 1 ,10683   ,267.5,267.7,267
XS GIS Cut Line= 3
 2227935.8672602459306.2656971832227222.42832575458622.451551517
2226638.96036397458674.165029381
#Sta/Elev= 30
       0 2492.78   110.9  2493.6     199 2486.89   377.3 2481.62   498.2 2473.04
   548.1 2464.48   602.8 2446.74   699.3 2394.88   758.6 2370.65   775.7 2366.58
   808.5 2373.03     821 2372.58   863.9 2361.82   922.8 2339.66   945.5 2324.63
   966.9 2318.69   988.2 2299.33  1014.6 2267.49  1026.6 2243.17  1030.6 2238.99
  1054.7 2237.82  1068.72238.885    1111 2244.97  1139.1 2242.15  1287.7 2247.32
  1428.3    2245  1520.6 2248.25  1540.6 2255.49  1548.7 2256.01    1574 2275.88
#Mann= 7 ,-1,0
       0      .1       0     210     .05       0     320      .1       0
  1030.6    .045       0  1068.7      .1       0 1198.23     .06       0
 1498.23      .1       0
Bank Sta=1030.6,1068.7
XS Rating Curve= 0 ,0
Exp/Cntr(USF)=0,0
Exp/Cntr=0.3,0.1

Type RM Length L Ch R = 1 ,10415   ,537,531.1,524.5
XS GIS Cut Line= 4
2227235.90897364458366.2139840832226986.23619238 458388.24817148
2226933.32177546458363.0508300852226608.53647742458407.976674268
#Sta/Elev= 30
       0 2308.39    15.8  2299.3    43.9 2280.47      68 2258.13    80.1  2247.6
    88.1 2241.68    96.1 2239.23   140.3 2235.75   176.4 2234.92   181.4 2235.82
   188.5 2240.23   200.5 2236.89   212.6 2236.83   224.6 2237.75   236.7 2239.94
   252.9 2240.63   276.4 2239.14   301.7 2240.66     355 2240.53   395.2 2238.76
   463.9 2239.98     480 2238.41   524.4  2240.3   548.7 2240.28   564.8 2243.93
     589 2255.38   597.1 2254.76   601.2 2257.31   613.3    2268   637.1 2281.74
#Mann= 5 ,-1,0
       0      .1       0   140.3    .045       0   181.4      .1       0
  429.25     .06       0  529.25      .1       0
#XS Ineff= 1 ,-1
  254.76   632.4 2249.48
Permanent Ineff=
       F
Bank Sta=140.3,181.4
XS Rating Curve= 0 ,0
Exp/Cntr(USF)=0,0
Exp/Cntr=0.3,0.1

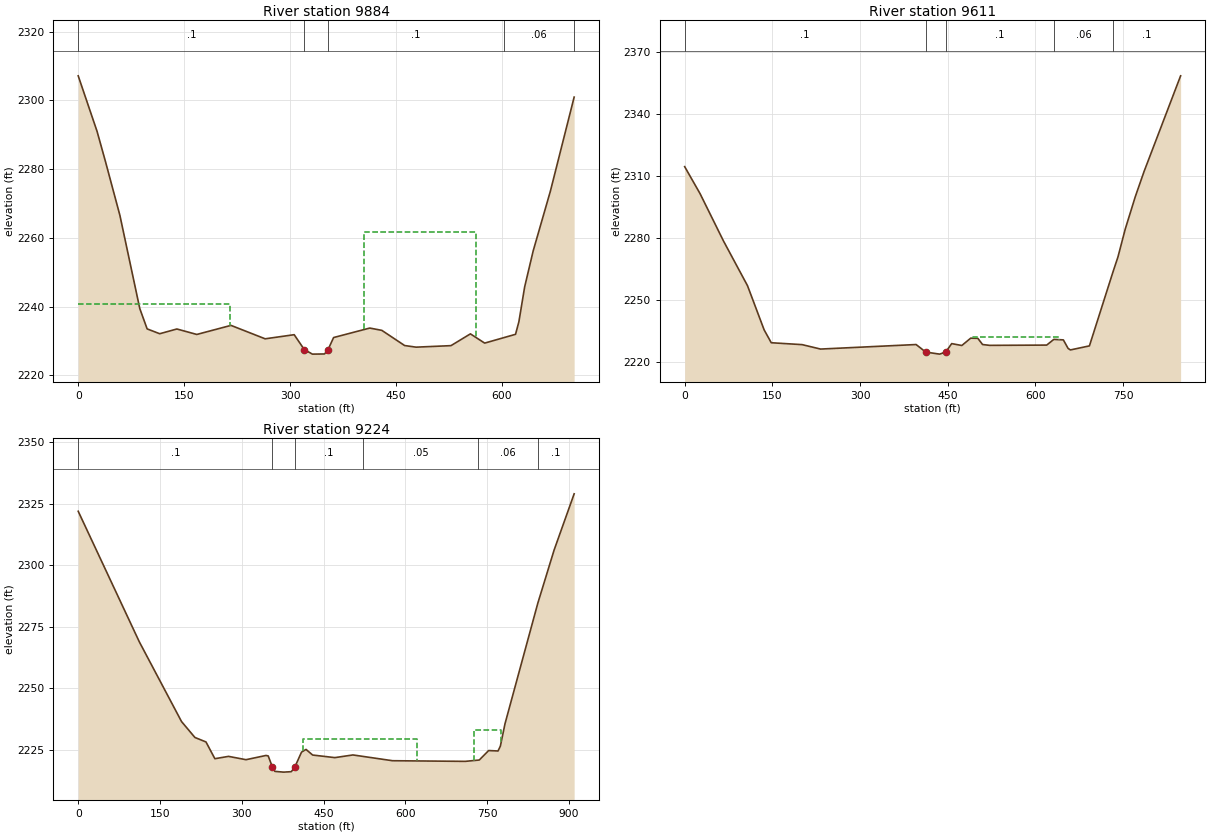
Type RM Length L Ch R = 1 ,9884    ,267.9,272.7,276.8
XS GIS Cut Line= 4
2227306.65150831457891.4898914912227016.57825186457853.597439072
2226895.52576336457900.6796154932226618.89602929457942.267433702
#Sta/Elev= 30
       0 2307.18    26.7    2291    38.8 2282.06      59 2266.56    87.2 2239.39
    97.6 2233.48   115.4 2232.07   139.7 2233.45   167.9 2231.86   216.3  2234.5
   264.7 2230.59   305.8 2231.79   320.12227.466   331.6 2226.13   348.8 2226.18
   353.82227.462   361.6 2230.96   412.8 2233.72   429.9 2233.05   462.2 2228.63
   478.4 2228.16   527.8  2228.6   555.3 2232.03   575.5 2229.34   619.2  2231.9
     624  2235.6   632.1 2245.69   644.2  2256.2   668.6 2273.63   702.2 2300.98
#Mann= 5 ,-1,0
       0      .1       0   320.1    .045       0   353.8      .1       0
  602.42     .06       0  702.16      .1       0
#XS Ineff= 2 ,-1
       0  214.93 2240.63  405.32  563.462261.702
Permanent Ineff=
       F       F
Bank Sta=320.1,353.8
XS Rating Curve= 0 ,0
Exp/Cntr(USF)=0,0
Exp/Cntr=0.3,0.1

Type RM Length L Ch R = 1 ,9611    ,378.8,387.4,397.7
XS GIS Cut Line= 2
2227338.03343575457529.6336102672226502.59369417457677.369068879
#Sta/Elev= 30
       0 2314.57    26.3 2301.52    66.3 2278.66   107.5 2256.97   135.9 2235.63
   148.1 2229.39   200.9 2228.47   232.5 2226.33   395.9 2228.52   412.4 2224.87
   436.1 2223.88   446.5 2224.87   456.8 2228.97   474.1 2228.05   489.3  2231.6
   501.5 2231.52   509.6 2228.52   521.8 2228.12   619.3 2228.25   631.5 2231.01
   647.8 2230.77   655.9 2226.64   659.9 2225.91   692.4 2227.87   732.5 2263.47
   741.2 2270.88   753.7  2284.4   770.9 2300.08   785.9 2312.26   848.4 2358.51
#Mann= 5 ,-1,0
       0      .1       0   412.4    .045       0   446.5      .1       0
   631.5     .06       0   732.5      .1       0
#XS Ineff= 1 ,-1
  493.36  639.53 2232.29
Permanent Ineff=
       T
Bank Sta=412.4,446.5
XS Rating Curve= 0 ,0
Exp/Cntr(USF)=0,0
Exp/Cntr=0.3,0.1

Type RM Length L Ch R = 1 ,9224    ,579.4,563.4,547.5
XS GIS Cut Line= 3
2227330.22322699457293.1288687082226846.19240007457199.313486002
2226457.98429059457349.808472059
#Sta/Elev= 30
       0 2321.98   112.1 2268.84   189.5 2236.41     214 2229.95   234.3 2228.13
   250.6 2221.31   275.6 2222.26   307.7 2220.91   344.3 2222.63   348.4 2222.45
   356.12217.891   360.6 2216.15   376.9 2215.85   390.8 2216.04   397.3 2217.97
   409.5 2223.99   417.7 2225.09   429.9  2222.8   470.6 2221.75   503.8 2222.84
   576.4 2220.49   709.7 2220.23   735.4 2220.77   752.6 2224.63   769.8 2224.45
   774.1 2226.43   782.6 2235.53   842.7 2284.53   872.7 2306.24   909.4 2329.08
#Mann= 6 ,-1,0
       0      .1       0   356.1    .045       0   397.3      .1       0
  523.04     .05       0  733.04     .06       0  843.04      .1       0
#XS Ineff= 2 ,-1
  411.96  621.26 2229.37  725.91  775.75 2233.12
Permanent Ineff=
       F       F
Bank Sta=356.1,397.3
XS Rating Curve= 0 ,0
Exp/Cntr(USF)=0,0
Exp/Cntr=0.3,0.1