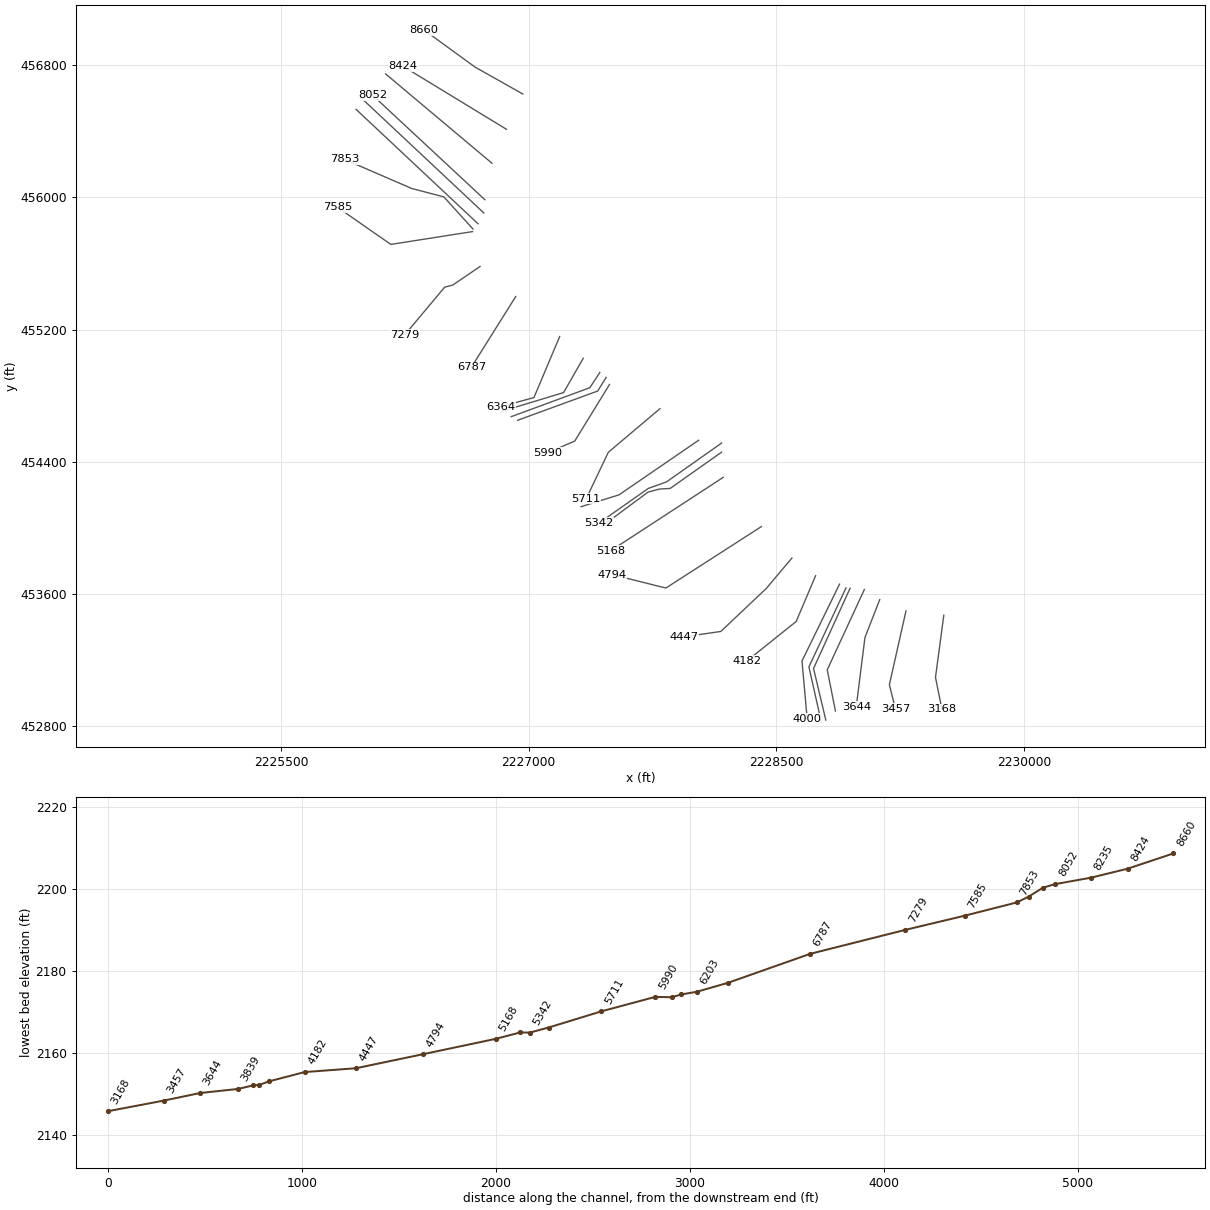
HEC-RAS study STONYCK.prj: STONYCK

--- STONYCK.g01 (geometry) --- (continued)

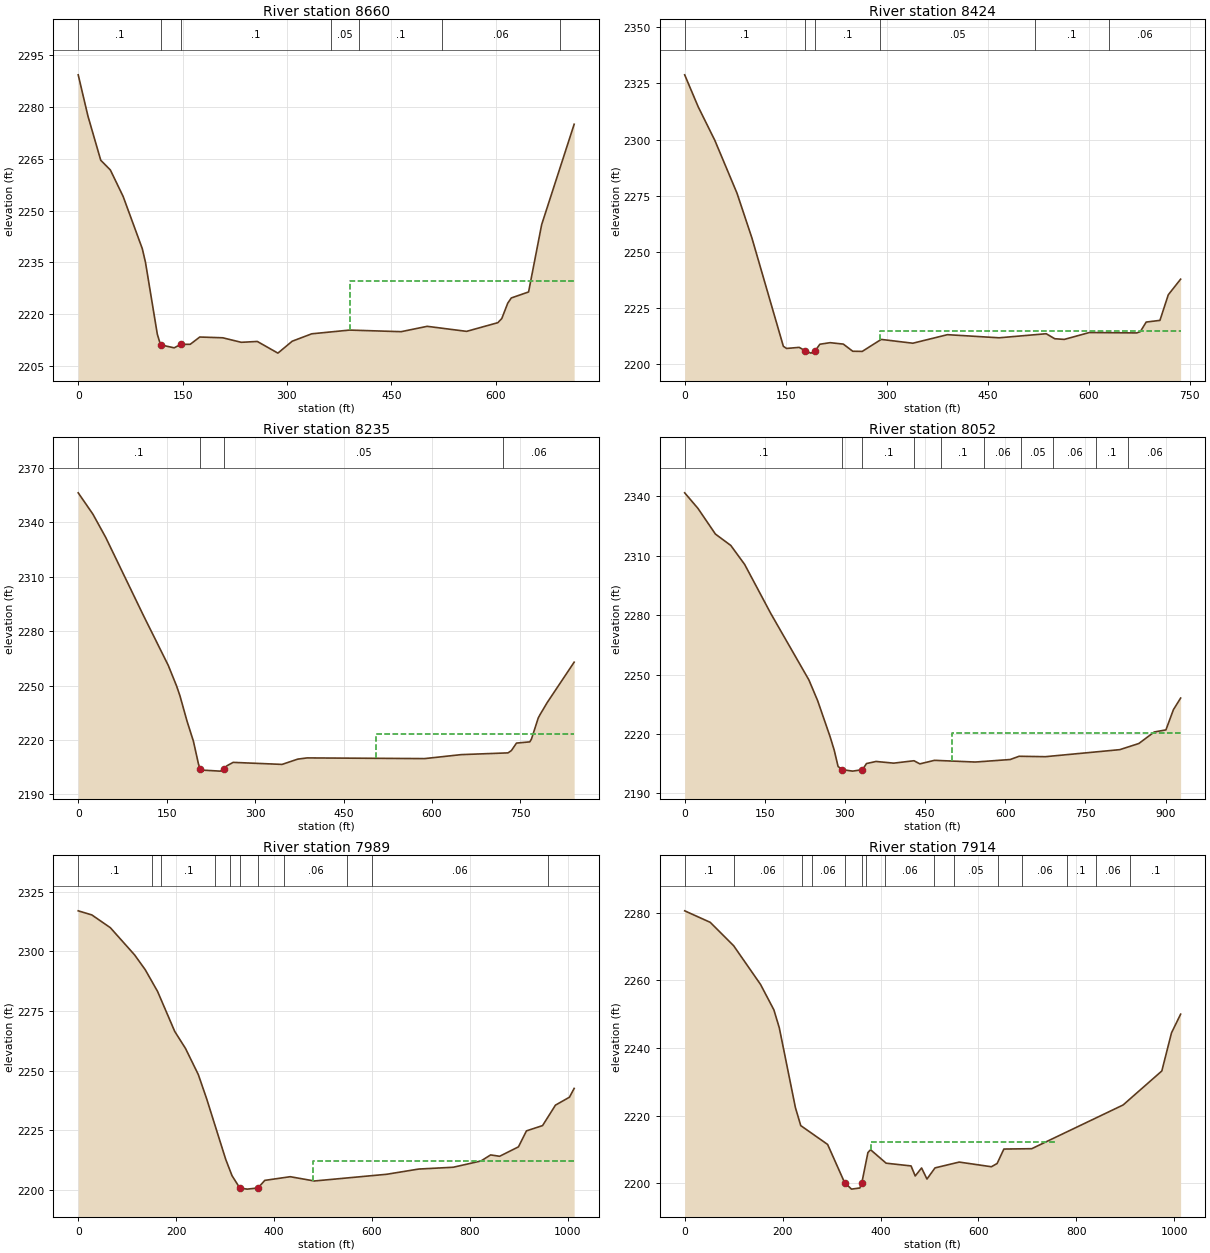
Type RM Length L Ch R = 1 ,8660    ,234.7,235.7,234.9
XS GIS Cut Line= 3
2226964.41504435456626.4933950262226674.23954381456789.995498768
2226367.18001558 457013.43030441
#Sta/Elev= 30
       0 2289.32      14 2277.37    32.4 2264.59    46.2 2261.78    64.6  2254.1
    92.1    2239    96.7 2235.03   113.7 2214.25   118.32211.162     138 2210.29
   147.2  2211.3     161 2211.31   174.7 2213.42   207.7  2213.2   234.4 2211.89
   257.4 2212.14     287 2208.76   307.6 2212.21   335.6 2214.35     390 2215.43
   464.2 2214.97   501.6 2216.52   558.2 2215.06   603.1 2217.57   608.8 2218.78
   617.4 2223.24   622.5 2224.73   647.3 2226.47   666.1 2245.96   712.8 2275.01
#Mann= 7 ,-1,0
       0      .1       0   118.3    .045       0   147.2      .1       0
  363.07     .05       0  403.07      .1       0  523.07     .06       0
  693.07      .1       0
#XS Ineff= 2 , 0
                             390         2229.69
Permanent Ineff=
       F       F
Bank Sta=118.3,147.2
XS Rating Curve= 0 ,0
Exp/Cntr(USF)=0,0
Exp/Cntr=0.3,0.1

Type RM Length L Ch R = 1 ,8424    ,193.4,189.4,185.6
XS GIS Cut Line= 2
2226865.28895369456412.7766061382226236.61528589456795.776195337
#Sta/Elev= 30
       0 2328.84      20 2314.66    44.8 2299.66    77.7 2276.16    99.7 2256.37
   146.5 2208.06   151.2 2207.11   169.9 2207.59   178.7 2206.14   187.4 2205.03
   193.9 2206.13   200.7 2208.99     216 2209.68   235.5 2209.05   249.5 2205.86
   263.6  2205.8   291.7 2211.13   338.7 2209.44   390.1 2213.24   466.8 2211.85
   536.7 2213.66   549.3 2211.44   563.4 2211.13   600.7 2214.19   671.1 2214.02
   676.4  2214.6   685.1 2218.85   705.5  2219.6   717.9 2230.99   736.2 2237.93
#Mann= 6 ,-1,0
       0      .1       0   178.7    .045       0   193.9      .1       0
     290     .05       0     520      .1       0     630     .06       0
#XS Ineff= 2 , 0
                             290            2215
Permanent Ineff=
       F       F
Bank Sta=178.7,193.9
XS Rating Curve= 0 ,0
Exp/Cntr(USF)=0,0
Exp/Cntr=0.3,0.1

Type RM Length L Ch R = 1 ,8235    ,183.5,182.8,181.4
XS GIS Cut Line= 2
2226777.46381074456207.2357132952226133.29211962456748.183137479
#Sta/Elev= 30
       0 2356.37      25 2344.56    46.6 2331.81   110.2 2288.99   152.8 2261.14
     167 2249.68   172.6 2244.37   184.5 2230.48   195.4 2219.35   203.9  2206.9
   206.7  2204.1   210.6 2203.38   240.8 2202.83   247.2  2203.8   252.1 2205.76
   262.8 2207.66   345.8 2206.54   372.5 2209.46   388.2 2210.12   587.7 2209.74
   649.4 2211.93   729.1  2212.9   734.8 2214.19   743.4  2218.3     766 2218.98
   768.9 2220.62   780.2 2232.07   783.1 2233.87   795.6 2240.71   841.2 2262.94
#Mann= 4 ,-1,0
       0      .1       0   206.7    .045       0   247.2     .05       0
     720     .06       0
#XS Ineff= 2 , 0
                          505.35         2223.58
Permanent Ineff=
       F       F
Bank Sta=206.7,247.2
XS Rating Curve= 0 ,0
Exp/Cntr(USF)=0,0
Exp/Cntr=0.3,0.1

Type RM Length L Ch R = 1 ,8052    ,63.5,63.4,63.5
BEGIN DESCRIPTION:
structure xs 4
END DESCRIPTION:
XS GIS Cut Line= 2
2226734.34481316455986.414180234 2226054.8939422456618.826144739
#Sta/Elev= 30
       0 2341.78    24.8 2333.94    57.6 2320.94    86.3 2315.22   112.3 2305.61
   161.4 2280.74   232.5 2247.32   248.9 2236.83   272.4 2218.48     280 2211.74
   287.1 2203.62     295 2202.01   314.4 2201.28   332.8 2202.03   340.3 2205.11
   358.2 2206.16   391.2 2205.31   429.2 2206.52   440.1 2204.94   467.5 2206.73
     544 2205.87   609.2 2207.14   625.9 2208.78   675.1 2208.57   814.3 2212.12
     850 2215.22   878.8 2221.03   900.7  2222.1   914.8 2232.35   928.2 2238.16
#Mann= 10 ,-1,0
       0      .1       0     295    .045       0   332.8      .1       0
     430     .06       0     480      .1       0     560     .06       0
     630     .05       0     690     .06       0     770      .1       0
     830     .06       0
#XS Ineff= 2 , 0
                          500.85         2220.61
Permanent Ineff=
       F       F
Bank Sta=295,332.8
XS Rating Curve= 0 ,0
Exp/Cntr(USF)=0,0
Exp/Cntr=0.3,0.1

Type RM Length L Ch R = 1 ,7989    ,75.6,75.2,76
BEGIN DESCRIPTION:
structure xs 3; 27.2 ft between structure and xs
END DESCRIPTION:
XS GIS Cut Line= 2
2226727.98827864 455906.257277822225989.13434829456599.306247525
#Sta/Elev= 30
       0 2316.93    27.7 2315.23    65.6 2309.88   115.4 2298.42   136.9 2292.28
   162.1 2283.19   197.2 2266.43   219.1 2259.34   245.3 2248.39   262.3 2238.29
   301.4 2212.82   314.2 2206.04   330.2 2200.85   345.3 2200.42   367.2 2200.92
   381.1 2204.08     433 2205.62   482.4 2203.83   630.2 2206.64   695.3 2208.82
     766 2209.58   822.6  2212.2   842.4 2214.74   860.8 2214.17   899.2 2218.11
   915.6 2224.81   948.5 2227.02   974.8 2235.58  1003.4 2238.91    1013 2242.58
#Mann= 11 ,-1,0
       0      .1       0     150     .06       0     170      .1       0
     280     .06       0     310      .1       0   330.2    .045       0
   367.2      .1       0     420     .06       0     550     .05       0
     600     .06       0     960      .1       0
#XS Ineff= 3 ,-1
       0     323  2200.3     375  479.32  2201.6  479.32    1013 2212.18
Permanent Ineff=
       F       F       F
Bank Sta=330.2,367.2
XS Rating Curve= 0 ,0
Exp/Cntr(USF)=0,0
Exp/Cntr=0.3,0.1

Type RM Length L Ch R = 1 ,7914    ,48.4,60.8,70.3
BEGIN DESCRIPTION:
structure xs 2; 19.6 ft between structure and xs
END DESCRIPTION:
XS GIS Cut Line= 2
2226693.13667815  455840.5371169 2225954.2827478456533.586086605
#Sta/Elev= 30
       0 2280.63    52.1 2277.23     100  2270.3   154.9 2258.84   182.2 2251.31
   193.3 2245.97   226.2 2222.35   237.1 2217.02     292 2211.44   326.6 2200.16
   340.7 2198.21   357.8 2198.55   361.92200.116   374.3 2209.04   379.7 2209.88
   411.5 2205.89   462.4 2205.08   470.9 2202.11   483.9 2204.48   494.9  2201.2
   511.4  2204.5   560.7 2206.22   626.5 2204.84   638.2  2205.8     652 2210.08
   708.8 2210.18   895.5 2223.13   974.6  2233.2   994.4  2244.5    1013 2250.02
#Mann= 15 ,-1,0
       0      .1       0     100     .06       0     240     .07       0
     260     .06       0   326.6    .045       0   361.9     .06       0
     370     .07       0     410     .06       0     510      .1       0
     550     .05       0     640      .1       0     690     .06       0
     780      .1       0     840     .06       0     910      .1       0
#XS Ineff= 4 ,-1
       0     320  2200.3     368  379.94  2201.6  379.94  759.21  2212.1
  759.21    1013  2201.6
Permanent Ineff=
       F       F       F       F
Bank Sta=326.6,361.9
XS Rating Curve= 0 ,0
Exp/Cntr(USF)=0,0
Exp/Cntr=0.3,0.1

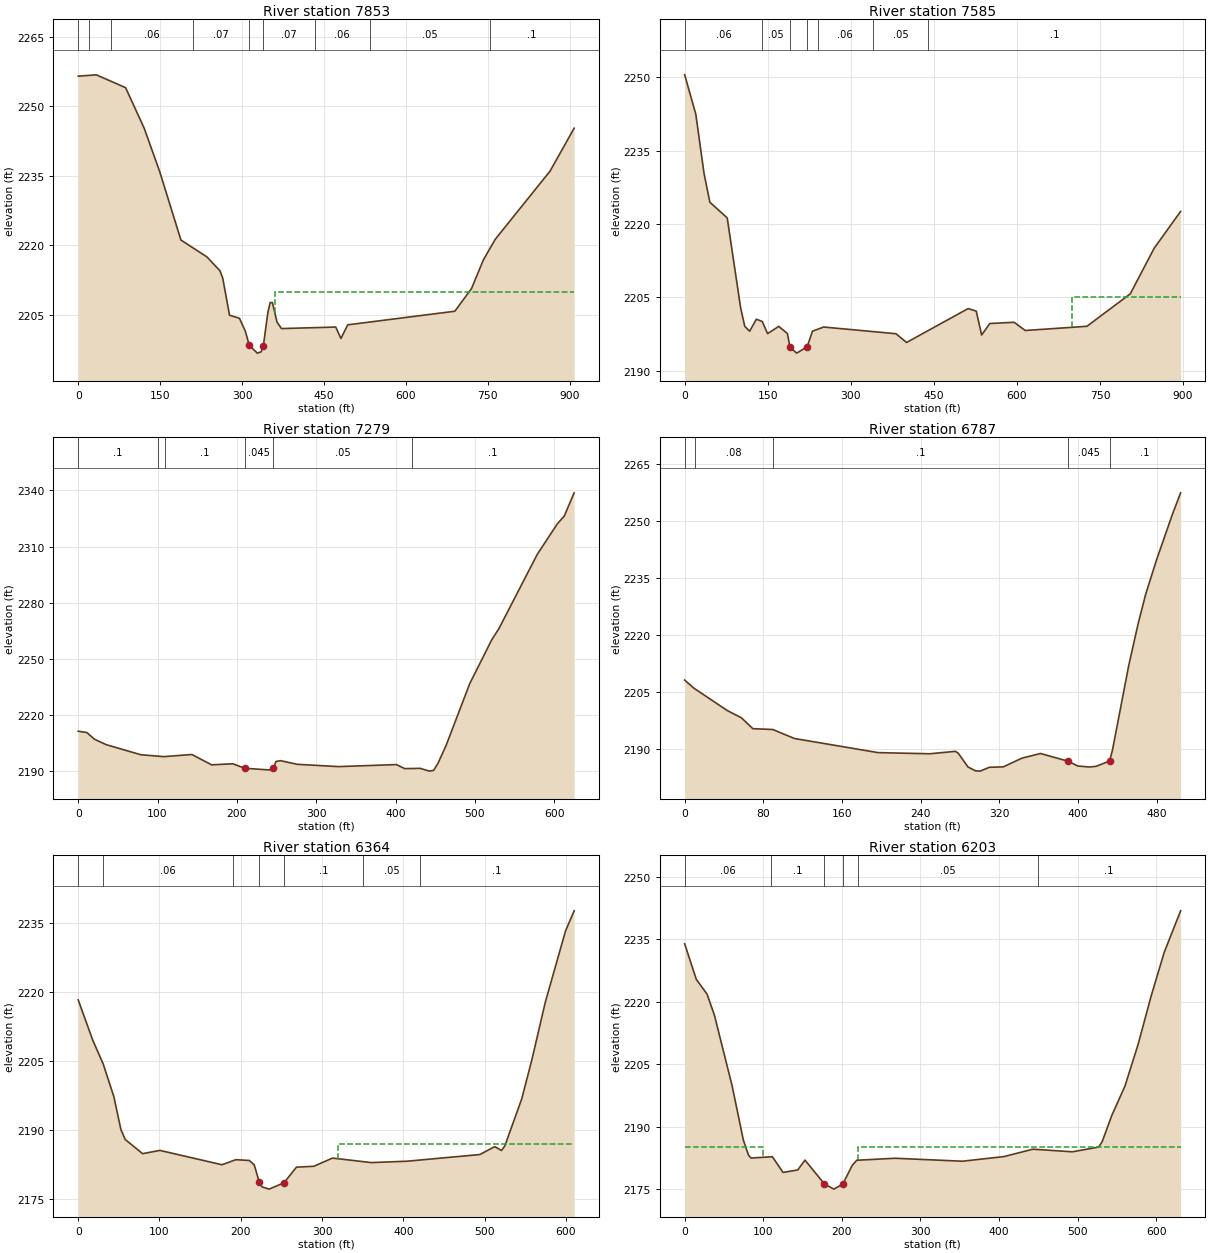
Type RM Length L Ch R = 1 ,7853    ,259.1,267.8,273.7
BEGIN DESCRIPTION:
structure xs 1
END DESCRIPTION:
XS GIS Cut Line= 4
2226662.47981719455808.711644754  2226486.083918456003.400452008
2226291.39511075 456054.359267332225883.72458817 456230.75516652
#Sta/Elev= 30
       0 2256.48    33.2 2256.77    86.8    2254   120.9 2245.24   149.2 2235.93
   188.1 2221.17   235.8 2217.52   259.6 2214.54   264.7 2212.94   277.1 2204.96
   295.2 2204.31     306 2201.54   313.3 2198.45     328 2196.79     335 2197.07
   339.1 2198.42   347.4 2205.59   351.5 2207.69   355.7 2207.66     364  2203.5
   372.2 2202.08   471.6 2202.41   481.1 2199.95   493.6 2202.89   689.7 2205.82
   720.3 2210.71     742  2216.9   763.8 2221.34   864.1 2236.02   908.2 2245.27
#Mann= 9 ,-1,0
       0     .06       0      20      .1       0      60     .06       0
     210     .07       0   313.3    .045       0   339.1     .07       0
  432.72     .06       0  533.96     .05       0  753.96      .1       0
#XS Ineff= 2 , 0
                             360            2210
Permanent Ineff=
       F       F
Bank Sta=313.3,339.1
XS Rating Curve= 0 ,0
Exp/Cntr(USF)=0,0
Exp/Cntr=0.3,0.1

Type RM Length L Ch R = 1 ,7585    ,303.9,306.2,307.9
XS GIS Cut Line= 3
2226660.05791724455793.3227229342226164.98794503455715.560420991
 2225841.3623229455940.858398862
#Sta/Elev= 30
       0  2250.5    20.1 2242.44      35 2230.31    45.5 2224.43    76.8 2221.23
   101.1 2202.79   108.5 2199.04   117.3 2198.05   129.5  2200.5     140 2200.04
   149.7 2197.55   169.9 2199.03   185.5 2197.57   190.2 2194.77   202.3 2193.56
   221.22194.865   230.7 2198.04   250.9  2198.9   381.5 2197.53   400.7 2195.74
   511.9 2202.68   526.5 2202.15   536.2 2197.27   550.9 2199.62   594.8 2199.87
     615 2198.19   726.3 2199.05   804.6 2205.69   847.7 2215.01   895.5 2222.56
#Mann= 7 ,-1,0
       0     .06       0     140     .05       0   190.2    .045       0
   221.2     .05       0     240     .06       0     340     .05       0
     440      .1       0
#XS Ineff= 2 , 0
                             700            2205
Permanent Ineff=
       F       F
Bank Sta=190.2,221.2
XS Rating Curve= 0 ,0
Exp/Cntr(USF)=0,0
Exp/Cntr=0.3,0.1

Type RM Length L Ch R = 1 ,7279    ,469.1,491.6,507.8
XS GIS Cut Line= 4
2226705.21841758455581.8802103412226539.83262636455469.164167954
2226491.07577076455456.6914839632226250.41273678455169.444149483
#Sta/Elev= 30
       0 2211.41    10.9 2210.71    20.6 2207.11    35.1 2204.26      79 2198.85
   107.8 2197.84   143.3 2198.97   168.2 2193.46   194.9 2194.03   209.7 2191.65
   241.1 2190.72   245.9 2191.68   249.3 2195.25     255 2195.69   275.9 2193.75
   328.1 2192.51   401.2 2193.59   411.6 2191.44   431.1 2191.58   442.9  2190.1
   448.1 2190.53   453.4 2194.16   463.8 2203.84   493.5 2236.73   521.2 2260.15
   530.4 2266.23   578.7 2305.84   603.8 2322.02   612.8 2326.35   625.2  2338.7
#Mann= 6 ,-1,0
       0      .1       0     100     .05       0     110      .1       0
   209.7    .045       0   245.9     .05       0  420.47      .1       0
Bank Sta=209.7,245.9
XS Rating Curve= 0 ,0
Exp/Cntr(USF)=0,0
Exp/Cntr=0.3,0.1

Type RM Length L Ch R = 1 ,6787    ,416.2,423.3,426.5
XS GIS Cut Line= 2
2226921.19380267 455399.734485892226653.33336316454972.464418962
#Sta/Elev= 30
       0 2208.14     9.4 2206.01    43.2 2200.16    57.7 2198.23    69.3 2195.38
    89.6 2195.16   111.6  2192.8   196.6 2189.09   249.3 2188.79   275.4 2189.43
   278.3 2188.89   288.1 2185.32   295.7 2184.31   300.4 2184.23   309.9 2185.24
     324 2185.35   342.9 2187.63   361.8 2188.86   390.1 2186.82   399.6 2185.58
   411.8 2185.31   418.5  2185.5   432.1 2186.89     435 2189.75   451.5 2211.92
   461.1 2222.94   468.8 2230.72   479.8 2239.69   495.9 2251.64   504.3 2257.32
#Mann= 5 ,-1,0
       0     .06       0      10     .08       0      90      .1       0
   390.1    .045       0   432.1      .1       0
Bank Sta=390.1,432.1
XS Rating Curve= 0 ,0
Exp/Cntr(USF)=0,0
Exp/Cntr=0.3,0.1

Type RM Length L Ch R = 1 ,6364    ,163.2,160.9,158.3
XS GIS Cut Line= 3
2227187.50067799455157.544672283 2227031.8202823454788.133563855
2226829.96349805 454732.72189759
#Sta/Elev= 30
       0 2218.31    17.8 2209.59    30.8 2204.34    43.8  2197.3    52.5 2190.15
    57.8 2187.96    79.2 2184.87   100.5 2185.58   176.9 2182.46     194 2183.56
   210.5 2183.39   216.6 2182.43   222.7 2178.74   226.1 2177.66   234.9 2177.16
   253.2 2178.54   268.5 2181.93   289.9 2182.13   312.9 2183.91   360.7 2182.93
   404.7 2183.23   494.1 2184.68   512.5  2186.4   520.8 2185.56   524.9 2186.56
   545.7 2196.78   558.1 2205.23   574.7  2217.8   599.6  2233.3   610.2 2237.67
#Mann= 7 ,-1,0
       0      .1       0      30     .06       0     190      .1       0
   222.7    .045       0   253.2      .1       0     350     .05       0
  420.88      .1       0
#XS Ineff= 2 , 0
                             320            2187
Permanent Ineff=
       F       F
Bank Sta=222.7,253.2
XS Rating Curve= 0 ,0
Exp/Cntr(USF)=0,0
Exp/Cntr=0.3,0.1

Type RM Length L Ch R = 1 ,6203    ,109.3,80.4,72
BEGIN DESCRIPTION:
structure xs 4
END DESCRIPTION:
XS GIS Cut Line= 3
2227330.17096153455026.0365068642227211.26705912454818.281336706
 2226836.2624438 454704.60397945
#Sta/Elev= 30
       0 2233.86    14.8 2225.32    28.5 2221.78    37.9  2216.7    60.4 2199.75
    74.7 2186.73    81.2 2183.13    84.5 2182.43   111.6 2182.75   125.2 2178.98
   143.9 2179.57   153.1 2181.94   177.82176.218   189.9 2174.97   201.32176.188
   213.1 2180.63     219  2181.9   267.7 2182.38   353.5 2181.67   406.3 2182.78
   443.2 2184.56   493.4 2183.93   526.8 2185.06   531.4 2186.38   543.5 2192.61
   560.3 2199.68     577 2209.65   593.7 2221.33   610.4 2231.86   631.2 2241.78
#Mann= 6 ,-1,0
       0     .06       0     110      .1       0   177.8    .045       0
   201.3      .1       0     220     .05       0  449.37      .1       0
#XS Ineff= 2 , 0
             100    2185     220            2185
Permanent Ineff=
       F       F
Bank Sta=177.8,201.3
XS Rating Curve= 0 ,0
Exp/Cntr(USF)=0,0
Exp/Cntr=0.5,0.3

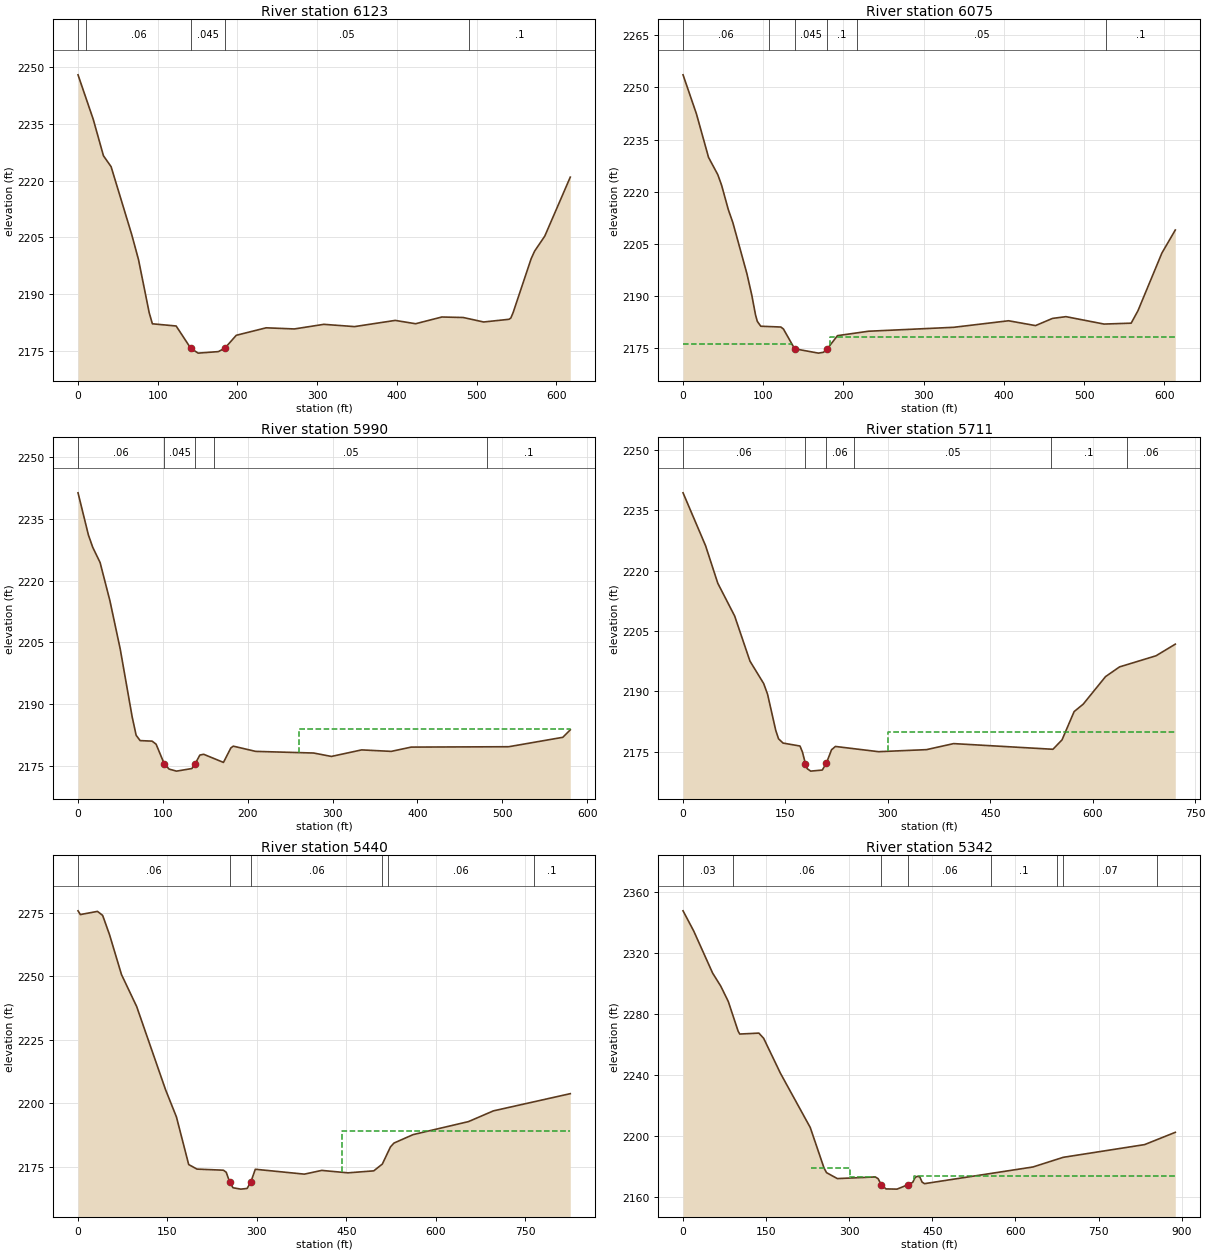
Type RM Length L Ch R = 1 ,6123    ,44.4,47.3,46
BEGIN DESCRIPTION:
structure xs 3; 22.1 ft between structure and xs
END DESCRIPTION:
XS GIS Cut Line= 3
2227430.62562554454939.8435423342227370.21131788454847.699902433
2226894.15493923454672.411677933
#Sta/Elev= 30
       0 2247.98    19.1 2236.19    31.9 2226.56    41.5 2223.66    67.3 2205.74
    75.9 2199.05    89.3 2184.99    93.3 2182.08   123.1  2181.5   141.52175.578
   150.7 2174.32     176 2174.72   184.22175.635   198.5 2179.04     236 2181.02
   271.3 2180.72   308.4 2181.94   346.8 2181.34   397.9 2182.98   423.5  2182.1
   456.4 2183.88   483.2 2183.75   508.8 2182.56   540.5 2183.27   542.9  2183.6
   545.8 2185.05   568.4  2199.3   572.7  2201.3   585.5 2205.29   617.5  2220.9
#Mann= 5 ,-1,0
       0      .1       0      10     .06       0   141.5    .045       0
   184.2     .05       0  490.18      .1       0
#XS Ineff= 2 , 0
             119  2176.3     206          2178.4
Permanent Ineff=
       F       F
Bank Sta=141.5,184.2
XS Rating Curve= 0 ,0
Exp/Cntr(USF)=0,0
Exp/Cntr=0.5,0.3

Type RM Length L Ch R = 1 ,6075    ,62.4,85.7,95.6
BEGIN DESCRIPTION:
structure xs 2; 10.4 ft between structure and xs
END DESCRIPTION:
XS GIS Cut Line= 3
2227468.93923389454910.0443660252227417.90956606 454827.61536082
2226932.46854758454650.452319366
#Sta/Elev= 30
       0 2253.61    16.7 2242.39    31.8 2229.89    43.4 2224.89    48.1 2221.87
    56.4 2214.91    62.1 2211.15    79.6  2196.5    85.7 2190.32    90.4 2184.59
    92.6 2182.77    96.9 2181.37     122 2181.14   125.2 2180.56   139.1 2174.89
   168.8 2173.64   175.1 2173.89   179.7 2174.84   192.5 2178.66   231.2 2179.93
   337.4 2181.06   405.9 2182.94   439.4 2181.55   460.7 2183.62   477.4 2184.12
   524.9 2181.99   558.7 2182.25   567.2 2185.84     597  2202.4   613.7 2209.02
#Mann= 6 ,-1,0
       0     .06       0  106.95      .1       0   139.1    .045       0
   179.7      .1       0  216.95     .05       0  526.95      .1       0
#XS Ineff= 2 , 0
             136  2176.3     183          2178.4
Permanent Ineff=
       F       F
Bank Sta=139.1,179.7
XS Rating Curve= 0 ,0
Exp/Cntr(USF)=0,0
Exp/Cntr=0.5,0.3

Type RM Length L Ch R = 1 ,5990    ,284.8,278.4,273
BEGIN DESCRIPTION:
structure xs 1
END DESCRIPTION:
XS GIS Cut Line= 3
2227489.54694515454867.5432738062227278.82753867454524.634249662
2227115.88208887454453.845789921
#Sta/Elev= 30
       0 2241.38    12.2 2231.16    17.3 2228.15      26 2224.44    37.6 2215.13
    49.7 2203.44    63.8 2186.92    68.5 2182.44    73.2 2181.15    87.3 2181.02
      92 2180.28   101.6 2175.51   107.4 2174.22   116.1 2173.73   134.2 2174.36
  137.772175.426   143.6 2177.64   148.1 2177.82   171.4 2175.85   180.1 2179.37
     183  2179.8   209.3 2178.53   277.7 2178.13   298.6  2177.3   334.2 2178.89
   369.1 2178.53   392.7 2179.57   507.5 2179.66   571.3 2181.95   580.1 2183.77
#Mann= 5 ,-1,0
       0     .06       0   101.6    .045       0  137.77     .06       0
     160     .05       0  482.48      .1       0
#XS Ineff= 2 , 0
                             260            2184
Permanent Ineff=
       F       F
Bank Sta=101.6,137.77
XS Rating Curve= 0 ,0
Exp/Cntr(USF)=0,0
Exp/Cntr=0.3,0.1

Type RM Length L Ch R = 1 ,5711    ,273.5,271.5,269.2
XS GIS Cut Line= 3
2227795.03818793454720.8031285322227482.08720781454456.609004009
  2227348.289325454175.406674045
#Sta/Elev= 30
       0 2239.35      33 2226.21    50.9 2216.88    75.6 2208.74      98 2197.54
   118.1 2191.96   123.8  2189.3   135.8 2180.31   139.9 2178.22   146.5 2177.16
   171.3 2176.43   174.9 2174.93   179.2 2172.07   181.7 2170.82     187 2170.19
     204 2170.46  210.05 2172.23   217.5  2175.5   223.2 2176.32   286.4 2175.02
   356.6 2175.53   396.3 2177.03   541.8 2175.62   555.1 2177.96   572.8 2184.98
   586.1 2186.83   618.8 2193.67   639.3 2196.09   692.7 2198.85     721 2201.74
#Mann= 6 ,-1,0
       0     .06       0   179.2    .045       0  210.05     .06       0
     250     .05       0  539.56      .1       0  649.56     .06       0
#XS Ineff= 2 , 0
                             300            2180
Permanent Ineff=
       F       F
Bank Sta=179.2,210.05
XS Rating Curve= 0 ,0
Exp/Cntr(USF)=0,0
Exp/Cntr=0.3,0.1

Type RM Length L Ch R = 1 ,5440    ,97.2,97.8,97.8
BEGIN DESCRIPTION:
structure xs 4
END DESCRIPTION:
XS GIS Cut Line= 3
2228029.22137685 454529.514716552227547.07258573454198.935735104
2227317.10459863454127.070739138
#Sta/Elev= 30
       0 2275.78     3.9 2274.31    32.6 2275.56    41.3 2273.98    52.8 2266.42
    72.9 2250.69    98.3 2238.14   146.8 2205.37     165 2194.68   185.6 2175.92
   199.5 2174.13   243.8  2173.7   248.6 2172.87   254.2  2169.1   259.9 2166.79
   272.9 2166.25   283.5 2166.51   289.72169.007   297.3 2174.07   379.6 2172.15
   408.7 2173.62   452.7 2172.66   495.9 2173.44   510.3 2176.11     524 2182.89
   529.9 2184.39     562 2187.71   654.7 2192.82   696.6 2197.05   825.5 2203.82
#Mann= 6 ,-1,0
       0     .06       0   254.2    .045       0   289.7     .06       0
     510      .1       0     520     .06       0  764.59      .1       0
#XS Ineff= 2 , 0
                          442.82         2189.08
Permanent Ineff=
       F       F
Bank Sta=254.2,289.7
XS Rating Curve= 0 ,0
Exp/Cntr(USF)=0,0
Exp/Cntr=0.5,0.3

Type RM Length L Ch R = 1 ,5342    ,45.1,47.3,49.2
BEGIN DESCRIPTION:
structure xs 3; 10.4 ft between structure and xs
END DESCRIPTION:
XS GIS Cut Line= 4
 2228167.8572588454512.1932582982227834.47934276454277.255487227
2227724.06972737454237.6746817112227426.78940589454028.751334835
#Sta/Elev= 30
       0 2347.77    19.2 2334.57    53.4 2306.89    68.1  2298.3    81.6  2288.3
    99.5 2268.67   102.4 2266.85   136.9 2267.45   145.5 2264.06   175.8  2241.1
   229.6 2205.48   254.5 2178.84     259 2175.82   278.5 2171.92     347    2173
   352.1 2171.87   357.9 2167.88   366.3 2165.14   386.2    2165   406.7    2168
   414.5 2169.44   419.1 2172.72     423  2173.4   427.3 2173.06   431.5 2169.61
   435.8 2168.59   631.6 2179.55   686.3 2185.89     833 2194.23   888.5  2202.3
#Mann= 8 ,-1,0
       0     .03       0      90     .06       0   357.9    .045       0
   406.7     .06       0  555.13      .1       0  675.13     .06       0
  685.13     .07       0  855.13     .06       0
#XS Ineff= 4 ,-1
       0  230.74  2167.5  230.74   300.8 2178.69   300.8     347  2172.7
     417   888.5  2173.3
Permanent Ineff=
       F       F       F       F
Bank Sta=357.9,406.7
XS Rating Curve= 0 ,0
Exp/Cntr(USF)=0,0
Exp/Cntr=0.5,0.3

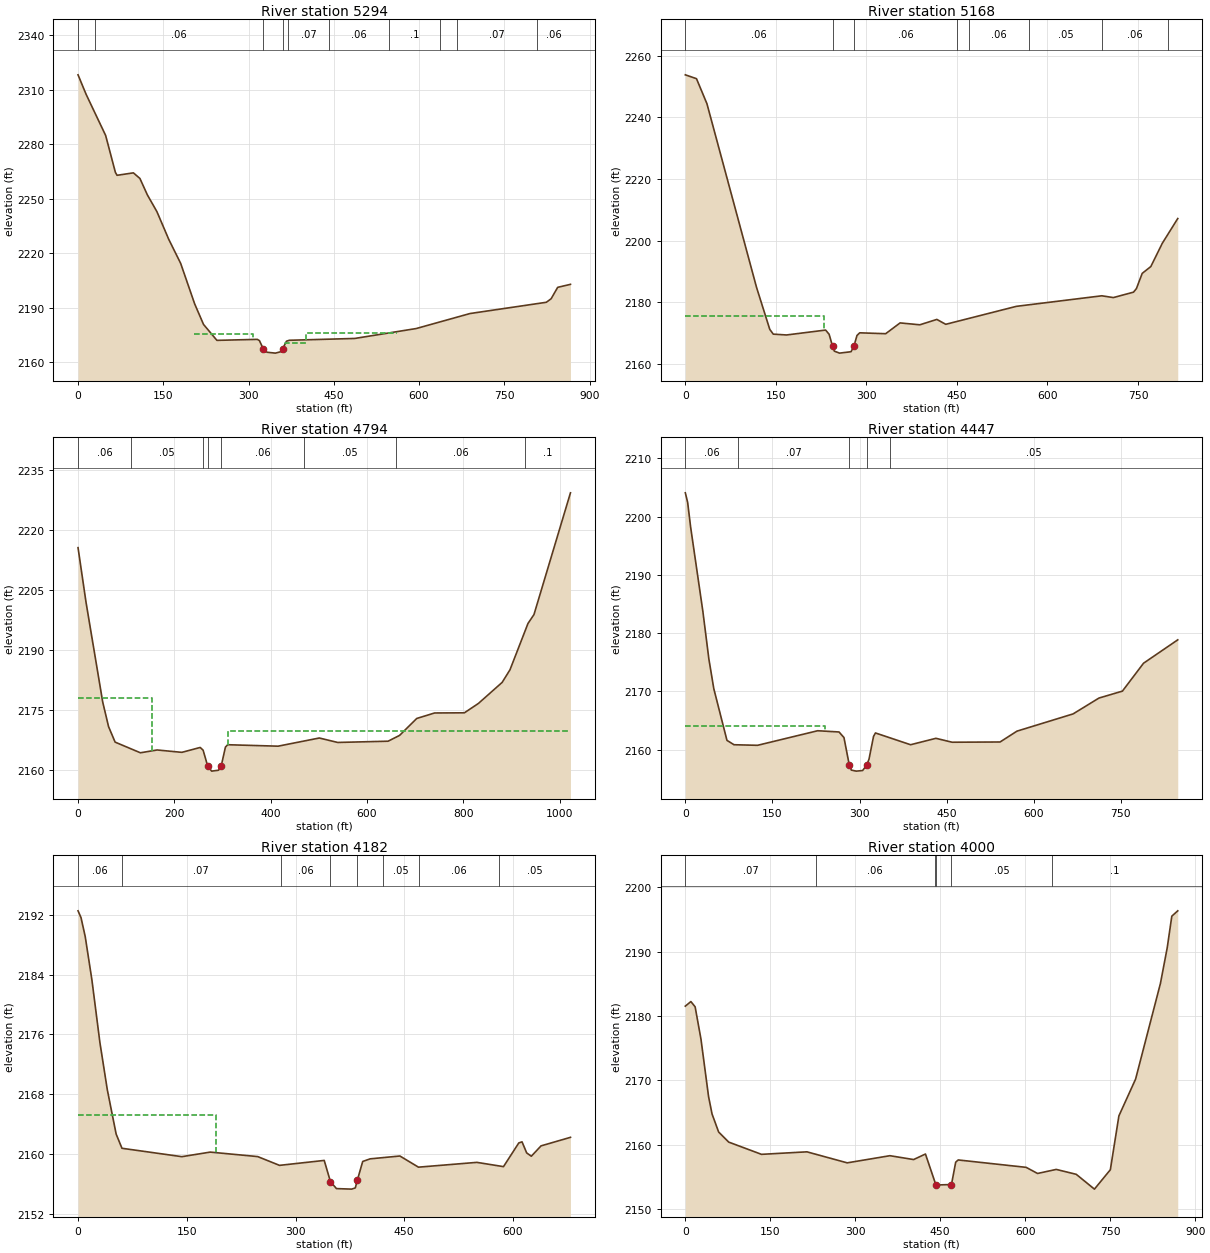
Type RM Length L Ch R = 1 ,5294    ,121.8,126.1,120.2
BEGIN DESCRIPTION:
structure xs 2; 23.7 ft between structure and xs
END DESCRIPTION:
XS GIS Cut Line= 5
 2228167.8572588454457.2167778762227856.70014585454237.674681711
2227792.81533695454234.2026812282227722.68092718454215.453878615
2227442.06620802454007.800459155
#Sta/Elev= 30
       0 2318.17    14.3 2307.38    48.6  2284.8    65.8 2264.44    68.7 2262.89
    97.4 2264.24   108.9 2261.15     122 2252.12   138.8  2242.9   159.6 2227.68
   180.6 2214.43   205.2 2192.18   220.8 2180.86   244.4 2172.08   315.5 2172.63
   319.2 2171.93   326.2 2167.27   332.5 2165.55   347.2 2165.06     357 2165.85
  359.91 2167.38   366.8 2171.61   371.7 2172.13   486.9 2173.13   595.1 2178.59
   689.7 2186.84     824 2193.03   832.5 2194.98     844 2201.25   866.5  2202.9
#Mann= 10 ,-1,0
       0     .03       0      30     .06       0   326.2    .045       0
  359.91     .06       0     370     .07       0  440.81     .06       0
  547.39      .1       0  637.39     .06       0  667.39     .07       0
  807.39     .06       0
#XS Ineff= 6 ,-1
       0  203.88  2167.5  203.88   307.4 2175.81   307.4     320  2170.5
   364.5  401.81  2170.5  401.81  561.89 2175.99  561.89   866.5  2170.3
Permanent Ineff=
       F       F       F       F       F       F
Bank Sta=326.2,359.91
XS Rating Curve= 0 ,0
Exp/Cntr(USF)=0,0
Exp/Cntr=0.5,0.3

Type RM Length L Ch R = 1 ,5168    ,374.3,374.4,374.2
BEGIN DESCRIPTION:
structure xs 1
END DESCRIPTION:
XS GIS Cut Line= 2
2228178.17791394454304.7732746192227494.80713411453859.210299627
#Sta/Elev= 30
       0 2253.79    18.5 2252.54    35.8 2244.42     118 2184.82   139.9 2171.21
   145.7 2169.66   167.7 2169.39   232.4 2170.98   238.2 2169.63     244  2165.7
   246.8 2164.15   255.5  2163.5   274.6 2163.96   279.3 2165.79   284.4 2169.23
   288.9 2170.09   331.9  2169.8   355.8  2173.3   388.5 2172.69   416.7 2174.44
   431.4 2172.85   548.5 2178.68     690  2182.1   709.1 2181.52   742.5 2183.28
   747.3 2184.43   756.9 2189.37   771.2 2191.59   790.2 2199.14   815.8 2207.17
#Mann= 8 ,-1,0
       0     .06       0     244    .045       0   279.3     .06       0
     450     .07       0     470     .06       0     570     .05       0
     690     .06       0     800      .1       0
#XS Ineff= 2 , 0
           229.3 2175.39
Permanent Ineff=
       F       F
Bank Sta=244,279.3
XS Rating Curve= 0 ,0
Exp/Cntr(USF)=0,0
Exp/Cntr=0.3,0.1

Type RM Length L Ch R = 1 ,4794    ,343.8,347.1,350.8
XS GIS Cut Line= 3
2228409.45253732 454006.860200432227830.61266072453634.468857695
2227506.56686073453715.480307694
#Sta/Elev= 30
       0 2215.55    16.6  2201.9    51.3 2176.96    63.4 2170.85      77 2166.99
   129.5 2164.33   164.2 2165.03   215.6 2164.44   253.6 2165.66   259.7 2164.97
   269.1 2161.03   277.4 2159.75   291.7 2159.97   297.4 2161.12     306 2165.75
   310.7 2166.34   415.3 2165.98   500.9 2168.02     539 2166.91   643.6 2167.22
   667.4 2168.66   703.2  2172.9   740.3 2174.27   802.1 2174.31     831 2176.63
   880.5 2181.91   896.8 2185.07   934.1 2196.62   946.5 2198.83  1022.3 2229.24
#Mann= 8 ,-1,0
       0     .06       0     110     .05       0     260     .08       0
   269.1    .045       0   297.4     .06       0     470     .05       0
     660     .06       0  928.28      .1       0
#XS Ineff= 2 , 0
          153.49  2177.9  310.99         2169.83
Permanent Ineff=
       F       F
Bank Sta=269.1,297.4
XS Rating Curve= 0 ,0
Exp/Cntr(USF)=0,0
Exp/Cntr=0.3,0.1

Type RM Length L Ch R = 1 ,4447    ,266.6,265,263.1
XS GIS Cut Line= 4
 2228594.2282356453816.2289566752228438.00471895453631.028497425
2228163.35369775 453371.495881062227937.83749227453338.739337247
#Sta/Elev= 30
       0 2204.07       4 2202.43     9.2 2198.14    30.2 2183.73    40.5 2175.59
      49 2170.47    71.7 2161.59    83.8 2160.84   124.4 2160.74   227.9 2163.24
   264.7 2163.03   273.2 2162.07   282.32157.385   285.8 2156.49   294.3 2156.31
   305.3 2156.41   312.8  2157.4   316.4  2158.4   324.1 2162.26   327.4 2162.86
   387.9 2160.84   431.6 2161.94   459.4 2161.27     542 2161.31   571.1 2163.17
   667.8 2166.13   712.3 2168.85   752.7 2170.04   789.1 2174.83     848 2178.84
#Mann= 5 ,-1,0
       0     .06       0      90     .07       0   282.3    .045       0
   312.8     .07       0  352.29     .05       0
#XS Ineff= 2 , 0
             240    2164
Permanent Ineff=
       F       F
Bank Sta=282.3,312.8
XS Rating Curve= 0 ,0
Exp/Cntr(USF)=0,0
Exp/Cntr=0.3,0.1

Type RM Length L Ch R = 1 ,4182    ,174.4,182,190.8
XS GIS Cut Line= 3
2228737.41824619453708.9471262422228619.82098006453431.940232699
2228324.52117845453195.439064154
#Sta/Elev= 30
       0  2192.5     4.1  2191.6     9.9 2189.07    19.1 2183.31    30.2 2174.91
    40.4 2168.62    52.6 2162.71    60.6 2160.82   143.2  2159.7   182.3 2160.31
   247.9 2159.71   277.9 2158.54   339.6  2159.2   348.2 2156.37   356.5 2155.44
   377.4 2155.37   382.5 2155.53   385.2 2156.53   392.7 2159.06     403 2159.41
     444 2159.79   469.6  2158.3   550.2 2158.94   586.9 2158.37     608 2161.53
   612.5 2161.68   618.9  2160.2   625.3 2159.76   638.7 2161.14   679.3 2162.28
#Mann= 8 ,-1,0
       0     .06       0      60     .07       0     280     .06       0
   348.2    .045       0   385.2     .06       0  420.94     .05       0
  470.94     .06       0  580.94     .05       0
#XS Ineff= 2 , 0
           190.7 2165.24
Permanent Ineff=
       F       F
Bank Sta=348.2,385.2
XS Rating Curve= 0 ,0
Exp/Cntr(USF)=0,0
Exp/Cntr=0.3,0.1

Type RM Length L Ch R = 1 ,4000    ,53.1,53.3,55.2
BEGIN DESCRIPTION:
structure xs 4
END DESCRIPTION:
XS GIS Cut Line= 3
2228882.45487441 453657.98831092 2228655.1001599453192.825791574
2228686.45943087452842.647265774
#Sta/Elev= 30
       0 2181.53     9.8 2182.24    17.3 2181.43    27.6 2176.42      41 2167.51
    47.2 2164.78    58.8 2161.99    76.6 2160.42   134.5 2158.52   214.7 2158.91
   285.8  2157.2   361.2 2158.31     403 2157.71   423.9 2158.57   442.4 2153.76
   469.8 2153.83   477.3  2157.3   481.7 2157.65   601.7  2156.5   621.8 2155.55
   654.8 2156.18   690.1 2155.42   722.2 2153.12   750.3 2156.13   765.4 2164.49
   794.9 2170.21   838.7 2185.05   850.7 2190.59   858.8  2195.5   869.3 2196.33
#Mann= 6 ,-1,0
       0     .07       0     230     .06       0     440     .05       0
   442.4    .045       0   469.8     .05       0  647.75      .1       0
Bank Sta=442.4,469.8
XS Rating Curve= 0 ,0
Exp/Cntr(USF)=0,0
Exp/Cntr=0.5,0.3

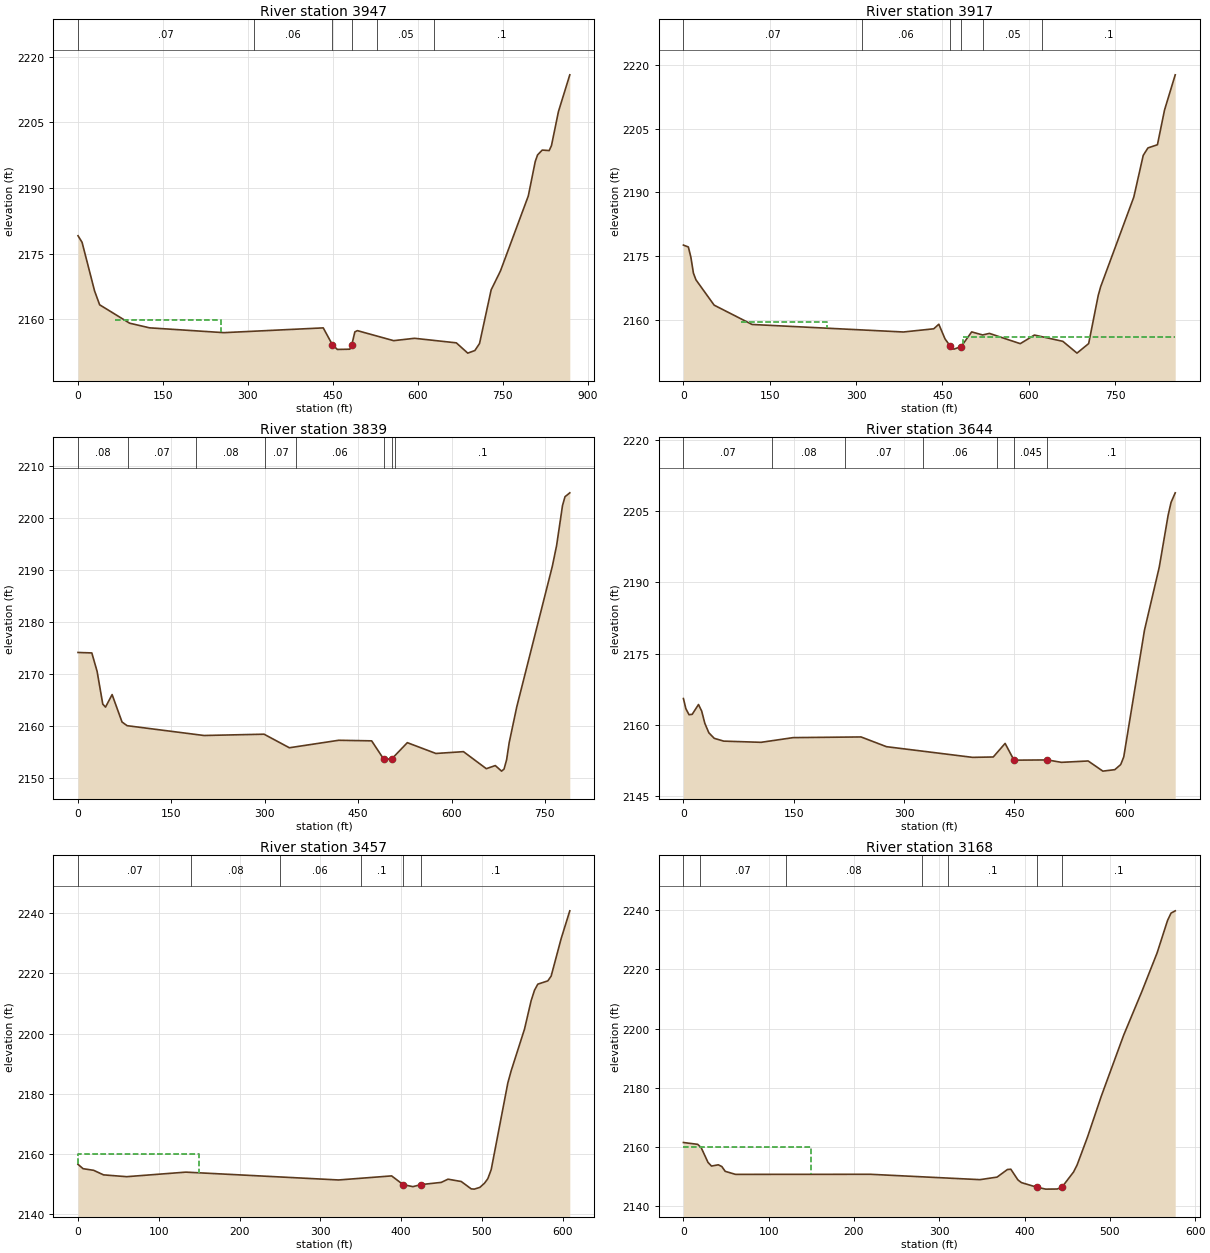
Type RM Length L Ch R = 1 ,3947    ,29.5,29.1,30.5
BEGIN DESCRIPTION:
structure xs 3; 7.3 ft between structure and xs
END DESCRIPTION:
XS GIS Cut Line= 3
2228921.74298182453635.7289964832228696.94472723453157.131775504
2228771.39295197452825.614496499
#Sta/Elev= 30
       0 2179.06     7.2 2177.55    29.3 2166.43    38.2 2163.28    91.2 2159.07
   126.4 2158.01   257.7 2156.91   433.1    2158   449.2 2154.16     458 2153.07
   480.1 2153.13   483.5 2154.11   488.9 2157.08   493.4 2157.37   557.4 2155.08
   594.3 2155.62   668.1 2154.58   688.3 2152.23   700.9 2152.83   709.1 2154.43
   729.6 2166.69     746    2171   795.2 2188.15   807.5 2196.04   811.6 2197.54
   819.8 2198.64   832.1 2198.53   836.1 2199.65   848.5 2207.47   868.5 2215.84
#Mann= 6 ,-1,0
       0     .07       0     310     .06       0   449.2    .045       0
   483.5     .06       0  528.76     .05       0  628.76      .1       0
#XS Ineff= 4 ,-1
       0   65.59  2153.5   65.59  253.29 2159.79  253.29     442  2153.5
     491   868.5  2155.9
Permanent Ineff=
       F       F       F       F
Bank Sta=449.2,483.5
XS Rating Curve= 0 ,0
Exp/Cntr(USF)=0,0
Exp/Cntr=0.5,0.3

Type RM Length L Ch R = 1 ,3917    ,79.1,79,79.4
BEGIN DESCRIPTION:
structure xs 2; 6.8 ft between structure and xs
END DESCRIPTION:
XS GIS Cut Line= 3
2228946.32185668453633.0316885582228725.07428324453147.247004839
2228799.11700636452835.106113268
#Sta/Elev= 30
       0 2177.58     8.6 2177.13      13 2174.69    17.4 2170.96    21.8 2169.39
    53.4 2163.43   119.3 2158.88   382.2 2157.11     435 2157.86   443.8 2158.94
   454.5 2155.51   463.6 2153.78   470.1 2153.06   482.7 2153.69   500.9 2157.13
     520 2156.41   531.7 2156.78   585.3 2154.36   609.9 2156.39   659.3 2154.91
   683.9 2152.13   704.2 2154.38   720.8 2165.71     725 2167.76   782.6 2188.88
     799 2198.71   807.2 2200.47   823.7 2201.22     836 2209.39   854.6 2217.69
#Mann= 6 ,-1,0
       0     .07       0     310     .06       0   463.6    .045       0
   482.7     .06       0     520     .05       0   623.8      .1       0
#XS Ineff= 4 ,-1
       0   99.57  2153.5   99.57  250.35 2159.48  250.35   461.3  2153.5
     485   854.6  2155.9
Permanent Ineff=
       F       F       F       F
Bank Sta=463.6,482.7
XS Rating Curve= 0 ,0
Exp/Cntr(USF)=0,0
Exp/Cntr=0.5,0.3

Type RM Length L Ch R = 1 ,3839    ,190.6,194.9,198.3
BEGIN DESCRIPTION:
structure xs 1
END DESCRIPTION:
XS GIS Cut Line= 3
 2229032.7180478453625.3224036632228807.97660586453139.253703672
 2228857.6287849452889.686172224
#Sta/Elev= 30
       0  2174.1    22.2 2174.01    30.7 2170.45    39.8 2164.15    44.2 2163.58
    54.8 2165.99    70.7 2160.71    78.9    2160   202.4 2158.11   298.9 2158.36
   339.5 2155.75   418.8 2157.19   471.7 2157.08     491 2153.58   503.8 2153.58
     529 2156.73   574.9 2154.65   619.2    2155   655.9 2151.72   670.3 2152.32
   680.4 2151.25   684.4 2151.65   688.5 2153.44   692.6 2156.71   704.8 2163.63
   761.9 2190.68   768.8 2194.69   778.3  2202.4   782.3 2204.09     790 2204.84
#Mann= 8 ,-1,0
       0     .08       0      80     .07       0     190     .08       0
     300     .07       0     350     .06       0     491    .045       0
   503.8     .06       0     510      .1       0
Bank Sta=491,503.8
XS Rating Curve= 0 ,0
Exp/Cntr(USF)=0,0
Exp/Cntr=0.3,0.1

Type RM Length L Ch R = 1 ,3644    ,188.4,186.9,185.4
XS GIS Cut Line= 4
2229125.89213903453564.2555427292229036.44157708453334.959736037
2228987.30676136 452944.400944422228987.30676136452915.424001816
#Sta/Elev= 30
       0 2165.55     3.3 2163.42     7.6 2162.15    11.9 2162.22    20.5 2164.29
    24.8 2162.92    29.1 2160.33    34.6 2158.33    41.9 2157.17    54.8 2156.58
   105.6 2156.33   149.3 2157.32   241.5 2157.46   276.1 2155.41   393.1 2153.16
   421.3 2153.24   437.4  2156.1   449.5 2152.57     495 2152.62     514 2152.11
   550.3  2152.4   570.3 2150.26   586.6 2150.57   594.6 2151.65   598.7 2153.25
   626.9 2179.95     647 2193.24     659 2204.12     663 2206.86   668.7 2208.89
#Mann= 7 ,-1,0
       0     .07       0     120     .08       0     220     .07       0
  326.13     .06       0  426.13      .1       0   449.5    .045       0
     495      .1       0
Bank Sta=449.5,495
XS Rating Curve= 0 ,0
Exp/Cntr(USF)=0,0
Exp/Cntr=0.3,0.1

Type RM Length L Ch R = 1 ,3457    ,281.6,289.2,296.9
XS GIS Cut Line= 3
2229284.89885182453495.9654109232229184.28785747453049.095799641
 2229220.8736736452902.752535127
#Sta/Elev= 30
       0 2156.63     6.3 2155.19    19.3 2154.66    31.6 2153.14    60.3 2152.54
   133.5 2154.05   322.7 2151.45   388.3  2152.8   402.62149.898   414.6 2149.23
   424.6 2149.91   449.8 2150.65   458.1 2151.71   474.5 2150.94   486.8  2148.5
   490.6 2148.41   497.5 2148.99   503.3 2150.38   507.4 2151.88   511.6 2154.89
   532.2 2183.67   536.3 2187.67   552.8 2201.48     561  2210.9   565.2 2214.41
   569.3 2216.42   581.7 2217.51   585.8 2219.09   598.2 2231.54   608.9 2240.75
#Mann= 6 ,-1,0
       0     .07       0     140     .08       0     250     .06       0
     350      .1       0   402.6    .045       0   424.6      .1       0
#XS Ineff= 2 , 0
             150    2160
Permanent Ineff=
       F       F
Bank Sta=402.6,424.6
XS Rating Curve= 0 ,0
Exp/Cntr(USF)=0,0
Exp/Cntr=0.3,0.1

Type RM Length L Ch R = 1 ,3168    ,290.4,297,304.4
XS GIS Cut Line= 3
2229513.93119651453469.7655124992229463.53651372453093.065258648
2229502.59239288452900.305596979
#Sta/Elev= 30
       0 2161.55    16.7 2160.94    20.8 2159.83    28.8 2154.85    32.9  2153.6
    40.9 2154.02      45 2153.45      49 2151.82    61.1 2150.79   219.2 2150.82
   347.7 2149.01   367.8 2149.87   379.9 2152.43   383.9 2152.54   392.2 2148.94
   396.3 2148.02   414.4 2146.46   424.8 2145.81   438.2 2145.85   443.7  2146.4
   457.5 2151.61   461.6 2153.94   473.8 2163.36   490.1 2177.27   516.2 2197.77
   537.8  2212.7   555.4 2225.54   567.7 2236.54   571.8 2239.02   576.7 2239.79
#Mann= 7 ,-1,0
       0     .06       0      20     .07       0     120     .08       0
     280     .07       0     310      .1       0   414.4    .045       0
   443.7      .1       0
#XS Ineff= 2 , 0
             150    2160
Permanent Ineff=
       F       F
Bank Sta=414.4,443.7
XS Rating Curve= 0 ,0
Exp/Cntr(USF)=0,0
Exp/Cntr=0.3,0.1