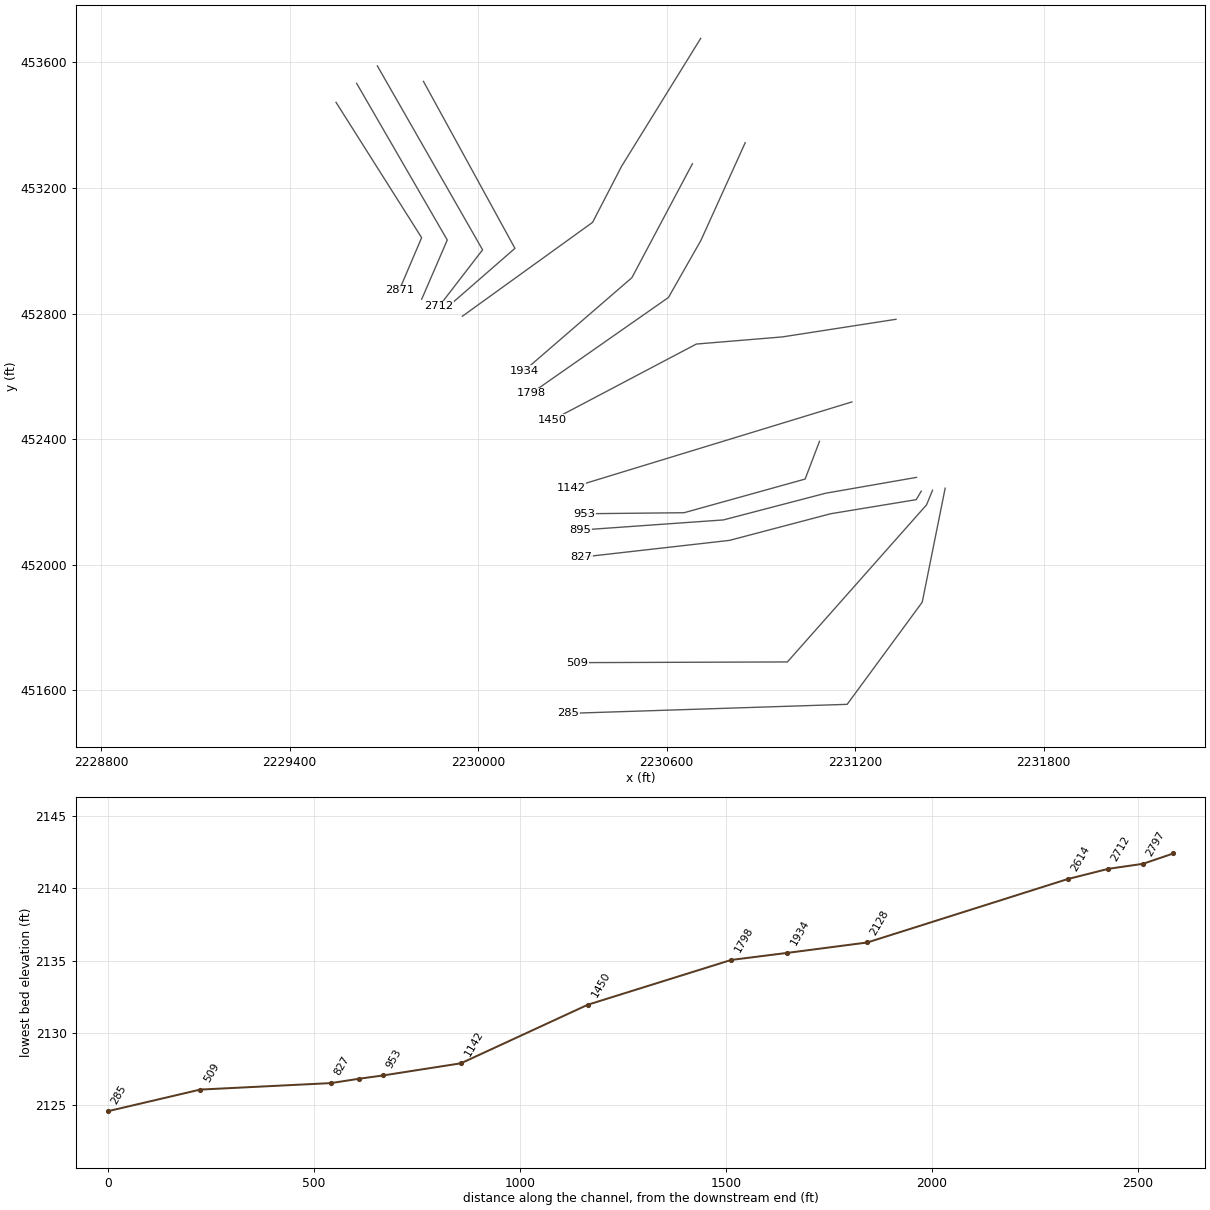
HEC-RAS study STONYCK.prj: STONYCK

--- STONYCK.g01 (geometry) --- (continued)

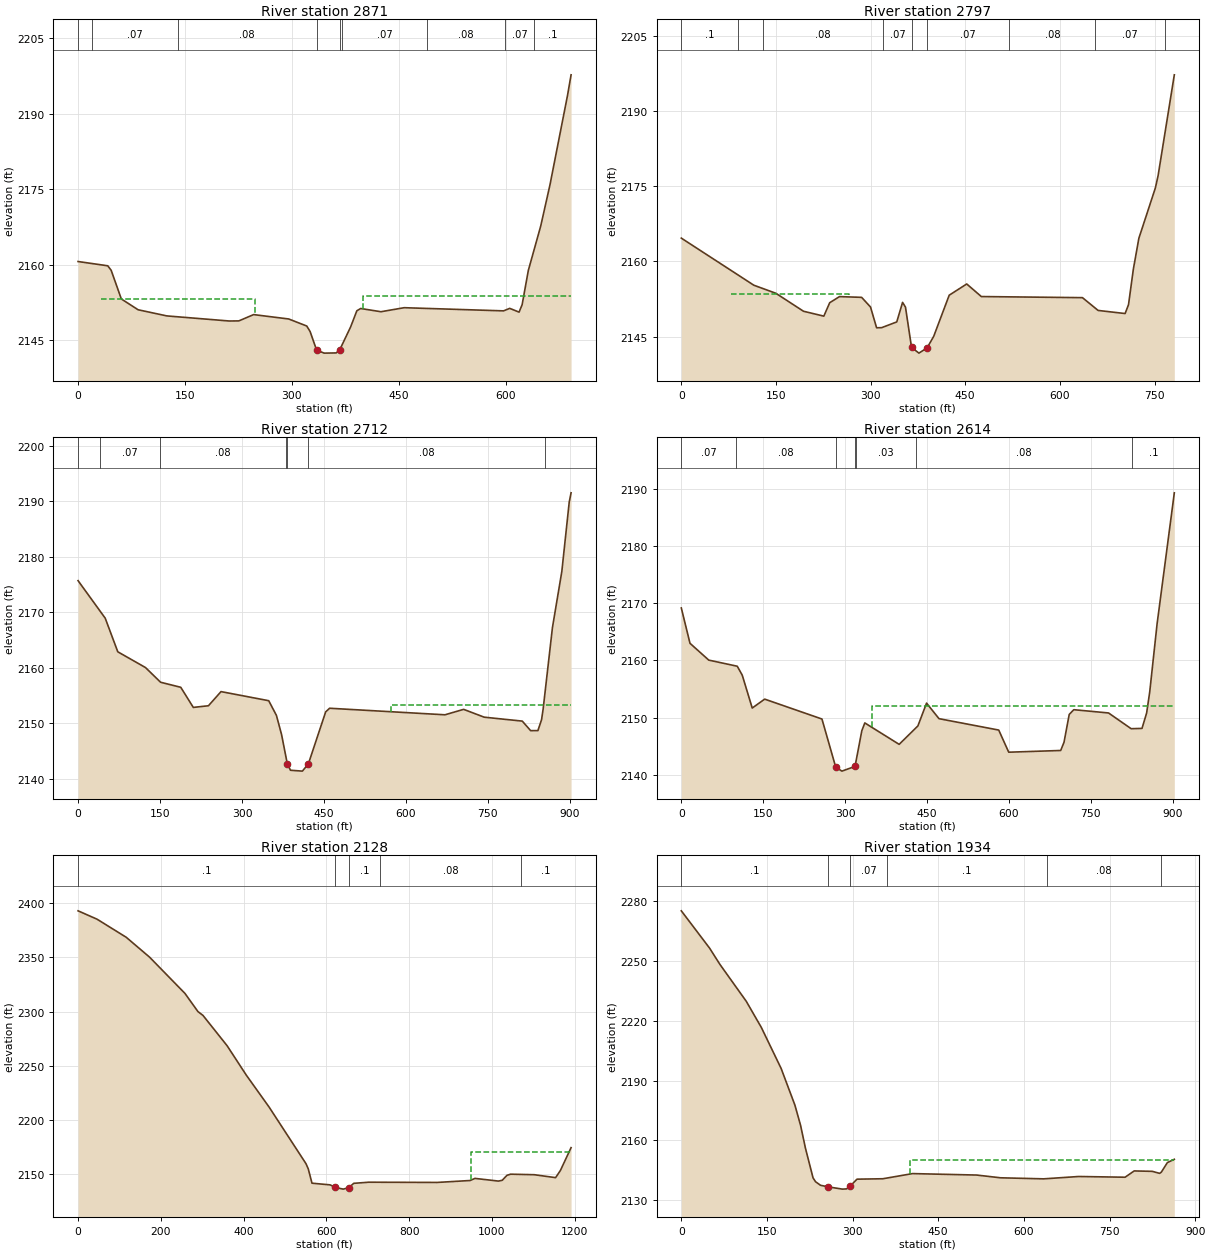
Type RM Length L Ch R = 1 ,2871    ,75.1,73.8,72.7
BEGIN DESCRIPTION:
structure xs 4
END DESCRIPTION:
XS GIS Cut Line= 3
2229547.53274617453472.4459576982229820.05383537453041.536177033
2229748.60119921452873.943449151
#Sta/Elev= 30
       0 2160.61    41.7 2159.76    46.5 2158.86    60.7 2153.18    84.3 2151.03
   124.6 2149.81   212.1  2148.8   225.7 2148.82   246.4 2150.07   295.7  2149.2
     321  2147.8   325.7 2146.71   334.82143.031   345.4 2142.42   362.3 2142.46
   367.12143.025   382.5  2147.6   391.3 2150.83   396.7 2151.28   425.1 2150.64
   457.7 2151.44   597.2 2150.81   605.9 2151.31     619 2150.56   623.3 2152.04
     632 2158.84   649.4 2167.66   662.4 2175.85   686.9 2193.51     692 2197.68
#Mann= 9 ,-1,0
       0     .06       0      20     .07       0     140     .08       0
   334.8    .045       0   367.1     .08       0     370     .07       0
     490     .08       0  599.85     .07       0  639.85      .1       0
#XS Ineff= 2 ,-1
   32.11  247.89 2153.07     400     692 2153.76
Permanent Ineff=
       F       F
Bank Sta=334.8,367.1
XS Rating Curve= 0 ,0
Exp/Cntr(USF)=0,0
Exp/Cntr=0.5,0.3

Type RM Length L Ch R = 1 ,2797    ,83.4,84.5,84.5
BEGIN DESCRIPTION:
structure xs 3; 33 ft between structure and xs
END DESCRIPTION:
XS GIS Cut Line= 3
 2229613.1927269453532.7564738392229901.67867232453034.021465574
2229820.25103725452845.597424612
#Sta/Elev= 30
       0 2164.65     115 2155.25   149.8 2153.65   193.6 2150.06   225.9 2149.08
   235.2 2151.76   250.7 2152.98   285.8 2152.83   299.9  2150.9   309.5 2146.76
   317.5 2146.78   341.5 2147.93   350.7 2151.83   355.3 2150.88   364.9 2142.85
   376.6  2141.7   389.52142.738     400 2145.04   424.6 2153.26   452.4  2155.5
   475.5 2152.99   635.8 2152.77   660.6 2150.22   703.4  2149.6   708.8 2151.37
   716.5 2158.48   725.2 2164.62   751.4 2174.68   755.7 2177.13   781.4 2197.24
#Mann= 9 ,-1,0
       0      .1       0      90     .07       0     130     .08       0
     320     .07       0   364.9    .045       0   389.5     .07       0
     520     .08       0  656.16     .07       0  766.16      .1       0
#XS Ineff= 5 ,-1
       0   78.31  2142.5   78.31  266.48 2153.56  266.48   331.9  2142.5
   422.5  747.61  2142.9  747.61   781.4 2152.84
Permanent Ineff=
       F       F       F       F       F
Bank Sta=364.9,389.5
XS Rating Curve= 0 ,0
Exp/Cntr(USF)=0,0
Exp/Cntr=0.5,0.3

Type RM Length L Ch R = 1 ,2712    ,99.1,98.6,97.9
BEGIN DESCRIPTION:
structure xs 2; 10.7 ft between structure and xs
END DESCRIPTION:
XS GIS Cut Line= 3
2229679.17785956453588.2885161772230014.11208257453002.747167445
2229875.06224837452822.492624807
#Sta/Elev= 30
       0  2175.7    49.7 2168.93    72.7 2162.87   123.4 2160.03     151 2157.38
   187.9 2156.47   210.9 2152.84   238.6 2153.14   261.6 2155.69   348.9 2154.05
     363  2151.4   372.4 2147.95   382.82142.724   388.7 2141.51   410.5 2141.35
   421.52142.672   453.1 2152.03   460.3 2152.69   671.4 2151.51   705.6 2152.49
   743.2 2151.08   812.9 2150.37   828.2 2148.65   841.5 2148.66   848.2 2150.63
     851 2152.49   868.1 2167.24   885.3 2177.38   898.8 2189.86   902.2 2191.54
#Mann= 7 ,-1,0
       0     .06       0      40     .07       0     150     .08       0
     380     .07       0   382.8    .045       0   421.5     .08       0
  854.57      .1       0
#XS Ineff= 3 ,-1
       0   379.5  2142.5     425  571.94  2142.9  571.94   902.2 2153.19
Permanent Ineff=
       F       F       F
Bank Sta=382.8,421.5
XS Rating Curve= 0 ,0
Exp/Cntr(USF)=0,0
Exp/Cntr=0.5,0.3

Type RM Length L Ch R = 1 ,2614    ,508.7,485.9,464.7
BEGIN DESCRIPTION:
structure xs 1
END DESCRIPTION:
XS GIS Cut Line= 3
2229825.84627601453539.0844085032230117.13049041 453007.51976615
2229893.37733684452812.446522249
#Sta/Elev= 30
       0 2169.17    15.9 2162.99    50.3 2160.05   102.5 2158.98   111.6 2157.42
   129.9 2151.67   152.7 2153.23   257.6 2149.75   282.82141.347   294.1 2140.64
   318.22141.467   330.6 2147.69   336.1 2149.07     399 2145.32   433.3 2148.54
   449.2 2152.53     472 2149.81   581.4 2147.82   599.7 2143.95   694.9 2144.25
     701  2145.7   710.5 2150.55   718.9 2151.38   782.5 2150.81   823.9 2148.06
   843.8 2148.11   852.3 2150.81     858 2154.53   871.4 2166.36     903  2189.3
#Mann= 7 ,-1,0
       0     .07       0     100     .08       0   282.8    .045       0
   318.2     .07       0     320     .03       0     430     .08       0
  826.14      .1       0
#XS Ineff= 2 , 0
                          348.85         2152.05
Permanent Ineff=
       F       F
Bank Sta=282.8,318.2
XS Rating Curve= 0 ,0
Exp/Cntr(USF)=0,0
Exp/Cntr=0.3,0.1

Type RM Length L Ch R = 1 ,2128    ,194,193.7,193.5
XS GIS Cut Line= 4
2230708.57398313453676.1547227592230456.81676486453269.076351821
2230364.31640949453090.2930326312229949.79945184 452791.37689791
#Sta/Elev= 30
       0 2392.97    45.8 2385.27   116.4 2368.56   172.8 2350.21   258.2  2316.8
   289.7 2299.98   301.8 2296.48   359.9 2268.62   406.4 2241.42   461.6 2211.89
   550.6 2159.73   556.2 2154.83   565.1 2141.73   609.1 2140.17   621.62137.799
   640.7 2136.25   654.32137.702     666  2141.6   702.4 2142.63   867.5 2142.42
   947.3  2144.2   958.8 2146.15  1015.5 2143.67  1024.7 2144.41  1036.1 2148.98
    1045 2150.03    1102 2149.55  1153.6 2146.85  1165.1 2153.36    1191  2174.5
#Mann= 5 ,-1,0
       0      .1       0   621.6    .045       0   654.3      .1       0
  729.93     .08       0 1069.93      .1       0
#XS Ineff= 2 , 0
                             950         2170.69
Permanent Ineff=
       F       F
Bank Sta=621.6,654.3
XS Rating Curve= 0 ,0
Exp/Cntr(USF)=0,0
Exp/Cntr=0.3,0.1

Type RM Length L Ch R = 1 ,1934    ,137.2,136.5,136.1
XS GIS Cut Line= 3
2230682.19063018453276.8934395322230489.43096851452914.051723449
2230146.99909895452618.108948768
#Sta/Elev= 30
       0 2275.29    49.5 2256.57    67.6  2248.4   113.7 2229.89   140.1 2216.76
   174.8 2196.16     199  2177.7   208.9 2167.56   217.4 2156.12   230.7 2141.22
     235 2139.28   243.8 2137.46   257.22136.665   282.3 2135.53   289.6 2135.66
   295.82137.064   307.7 2140.53     353 2140.74     405 2143.33   517.3  2142.6
     559 2141.22   634.6 2140.69     696 2141.87   777.3 2141.51   793.2 2144.67
   824.9 2144.46   837.8 2143.45   840.8 2144.08   851.3 2148.85   863.5 2150.52
#Mann= 6 ,-1,0
       0      .1       0   257.2    .045       0   295.8     .07       0
     360      .1       0  640.87     .08       0  840.87      .1       0
#XS Ineff= 2 , 0
                             400            2150
Permanent Ineff=
       F       F
Bank Sta=257.2,295.8
XS Rating Curve= 0 ,0
Exp/Cntr(USF)=0,0
Exp/Cntr=0.3,0.1

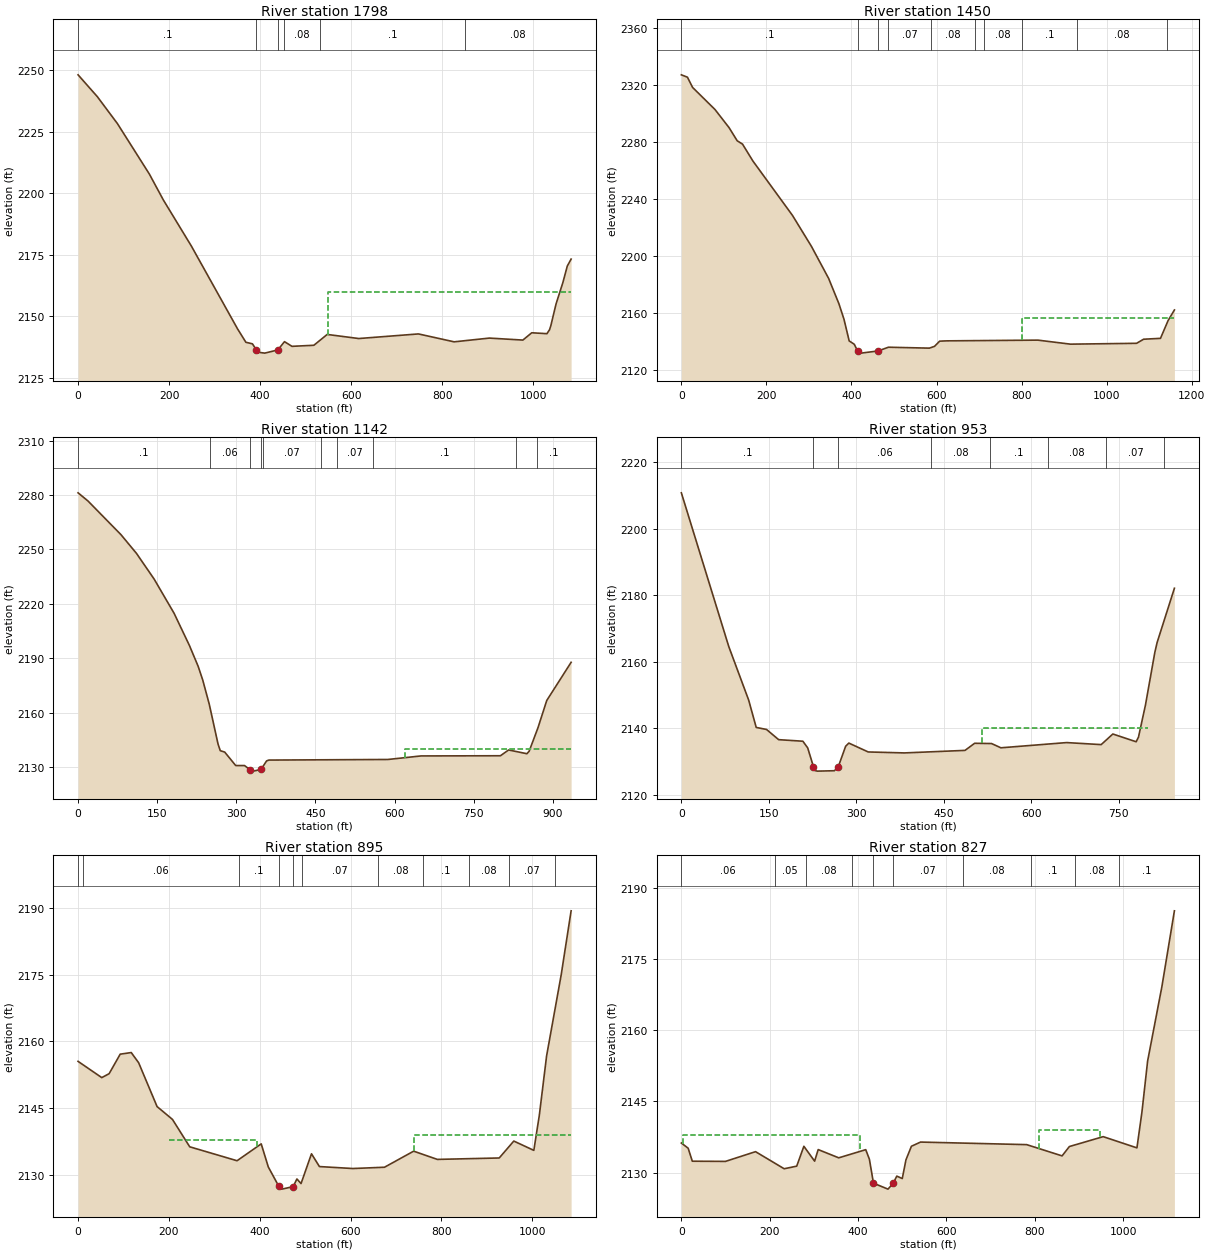
Type RM Length L Ch R = 1 ,1798    ,377.2,347.7,311.3
XS GIS Cut Line= 4
2230850.24426647453343.8313367912230709.01603977453032.465134131
2230605.83292676452851.044276089 2230169.2889871452546.030458507
#Sta/Elev= 30
       0 2248.12    42.4 2239.23    86.4 2228.32   156.6 2207.81   187.4 2197.26
   248.9 2178.55   350.3 2144.92   368.7 2139.45   383.1 2138.82   391.9 2136.27
   396.3 2135.39   410.1 2135.04   438.8 2136.33   453.5  2139.7   469.9  2137.8
     518 2138.23   547.3 2142.63   616.7 2140.97   747.8 2142.84   826.2 2139.63
   903.6 2141.15   977.2 2140.34   996.7 2143.31    1030 2142.94  1035.8 2144.54
  1038.6 2146.17  1050.1 2155.02    1065 2163.65  1074.8 2170.42  1083.2 2173.25
#Mann= 6 ,-1,0
       0      .1       0   391.9    .045       0   438.8      .1       0
   451.9     .08       0   531.9      .1       0  850.61     .08       0
#XS Ineff= 2 , 0
                             550            2160
Permanent Ineff=
       F       F
Bank Sta=391.9,438.8
XS Rating Curve= 0 ,0
Exp/Cntr(USF)=0,0
Exp/Cntr=0.3,0.1

Type RM Length L Ch R = 1 ,1450    ,301.3,308,311.9
XS GIS Cut Line= 4
 2231330.3248207 452781.662446732230968.12870258452725.491006998
2230694.75940906452702.8371827122230236.13007116452461.109469006
#Sta/Elev= 30
       0 2327.02    14.3 2325.36    26.5 2318.16    79.1  2302.7   112.2    2290
   131.3 2280.79   143.8 2278.46   168.1 2266.66   261.2 2228.51   305.8 2206.81
   346.2 2184.37   370.5 2166.55   382.5 2155.58   394.6  2140.5   406.6 2138.14
   414.6 2133.31   422.4 2131.94   462.8 2133.47   486.9 2136.08   583.2 2135.44
   595.3  2136.7   607.3 2140.33   624.3 2140.54   838.2 2141.05     915 2138.23
  1070.4 2138.82  1086.9 2141.69  1126.6  2142.3  1144.4 2154.74  1159.3 2162.19
#Mann= 10 ,-1,0
       0      .1       0   414.6    .045       0   462.8      .1       0
  486.53     .07       0  586.53     .08       0  690.83      .1       0
  710.83     .08       0  800.83      .1       0  930.83     .08       0
 1140.83     .06       0
#XS Ineff= 2 , 0
                             800         2156.45
Permanent Ineff=
       F       F
Bank Sta=414.6,462.8
XS Rating Curve= 0 ,0
Exp/Cntr(USF)=0,0
Exp/Cntr=0.3,0.1

Type RM Length L Ch R = 1 ,1142    ,189.5,188.8,188
XS GIS Cut Line= 2
2231190.02268089452518.5322003062230296.04597981452245.431919309
#Sta/Elev= 30
       0 2281.22    18.7 2276.75    81.4 2258.15   110.7 2247.87   144.1 2233.75
     182 2214.88   211.1 2197.13   227.8 2185.54   236.4 2178.05   248.7  2164.8
   265.4 2142.79   269.6 2139.15     278 2138.38   298.9 2130.95   315.6 2130.95
   325.9 2128.68   332.3 2127.88   346.9 2128.81     350 2130.19   357.4 2133.49
   361.6 2133.97   587.5  2134.3   650.2 2136.25   800.8 2136.35   816.3 2139.54
     851 2137.47   855.2 2138.84   871.9 2151.73   888.6  2166.8   934.8 2187.83
#Mann= 10 ,-1,0
       0      .1       0     250     .06       0   325.9    .045       0
   346.9     .06       0     350     .07       0     460     .06       0
     490     .07       0     560      .1       0     830     .08       0
     870      .1       0
#XS Ineff= 2 , 0
                             620            2140
Permanent Ineff=
       F       F
Bank Sta=325.9,346.9
XS Rating Curve= 0 ,0
Exp/Cntr(USF)=0,0
Exp/Cntr=0.3,0.1

Type RM Length L Ch R = 1 ,953     ,58.7,58.5,59.1
BEGIN DESCRIPTION:
structure xs 4
END DESCRIPTION:
XS GIS Cut Line= 4
2231086.75029615452393.1643819112231041.01802599452272.953843203
2230655.56032035452165.8096673992230338.56808598452162.574642265
#Sta/Elev= 30
       0  2210.8    81.3 2164.55   115.5  2148.4   128.4 2140.19   146.1 2139.58
   166.9 2136.51   208.4 2136.04   216.7 2134.04   226.6 2128.37   229.1 2127.21
   233.1 2127.04   262.4 2127.16   268.8 2128.18   281.8 2134.53   287.3 2135.48
   320.5 2132.81   382.7 2132.52   486.5 2133.28   503.1 2135.42   532.1 2135.34
   548.1 2134.06   660.8 2135.63   720.1 2135.02   740.1 2138.21   780.1 2135.88
   784.1 2137.28   796.1 2146.98   812.1 2162.75   816.1 2165.78   845.7 2182.08
#Mann= 8 ,-1,0
       0      .1       0   226.6    .045       0   268.8     .06       0
  428.62     .08       0  528.62      .1       0  628.69     .08       0
  728.69     .07       0  828.69      .1       0
#XS Ineff= 1 ,-1
  515.49     800    2140
Permanent Ineff=
       F
Bank Sta=226.6,268.8
XS Rating Curve= 0 ,0
Exp/Cntr(USF)=0,0
Exp/Cntr=0.5,0.3

Type RM Length L Ch R = 1 ,895     ,70.4,67.9,68
BEGIN DESCRIPTION:
structure xs 3; 21.4 ft between structure and xs
END DESCRIPTION:
XS GIS Cut Line= 4
2231395.57598214452278.3434421142231105.81396645 452227.76368198
 2230780.9033039452142.8925590442230326.33350504452110.645573083
#Sta/Elev= 30
       0 2155.52    52.2 2151.87    68.4 2152.75    92.8 2157.14   117.1  2157.5
   133.4 2155.21     174 2145.36   207.9 2142.47   245.9 2136.32   350.1 2133.19
   403.3 2136.98   418.9 2131.79   441.8 2127.49   448.8 2126.81   473.6 2127.37
   481.9 2129.09     491 2128.06     514 2134.75   531.5 2131.88   605.1 2131.44
   674.8 2131.73     739 2135.34   791.1 2133.49   927.4 2133.81   959.5 2137.61
  1003.6 2135.52  1015.7 2143.41  1031.7 2156.74  1063.8 2174.94  1085.7 2189.35
#Mann= 11 ,-1,0
       0      .1       0      10     .06       0  354.14      .1       0
   441.8    .045       0   473.6     .06       0  494.14     .07       0
  659.96     .08       0  759.96      .1       0  859.96     .08       0
  949.96     .07       0 1049.96      .1       0
#XS Ineff= 4 ,-1
  199.44  394.82 2137.81  394.82   420.4  2126.9     495  739.61  2126.7
  739.61  1085.7 2138.88
Permanent Ineff=
       F       F       F       F
Bank Sta=441.8,473.6
XS Rating Curve= 0 ,0
Exp/Cntr(USF)=0,0
Exp/Cntr=0.5,0.3

Type RM Length L Ch R = 1 ,827     ,299.8,317.2,332.5
BEGIN DESCRIPTION:
structure xs 2; 18.4 ft between structure and xs
END DESCRIPTION:
XS GIS Cut Line= 5
2231410.79836025452234.4561423962231394.73644588452207.429142857
2231122.53100582452162.6100926552230800.19219548452077.738969719
2230327.97566826452024.139167227
#Sta/Elev= 30
       0 2136.22    15.4 2135.13    24.8 2132.39    99.8 2132.35   167.9  2134.4
   232.7  2130.8   261.1 2131.35   277.3 2135.53   301.6  2132.4   309.7 2134.84
   356.2  2133.1   417.3 2134.82   425.6  2132.8   434.82127.765   467.6 2126.51
   479.3 2127.71   487.6 2129.25     500 2128.74   508.3 2132.67   520.7 2135.54
   541.4 2136.42   781.6 2135.88   861.7 2133.51   878.2 2135.48   954.7 2137.56
  1031.1  2135.2  1042.5  2142.8  1055.3  2153.5  1087.5 2169.11  1115.9 2185.12
#Mann= 10 ,-1,0
       0     .06       0  211.44     .05       0  281.44     .08       0
  387.31     .07       0   434.8    .045       0   479.3     .07       0
  637.31     .08       0  790.63      .1       0  890.63     .08       0
  990.63      .1       0
#XS Ineff= 4 ,-1
    4.06  404.96 2137.81  404.96     428  2126.9     483  809.24  2126.7
  809.24  946.48 2138.95
Permanent Ineff=
       F       F       F       F
Bank Sta=434.8,479.3
XS Rating Curve= 0 ,0
Exp/Cntr(USF)=0,0
Exp/Cntr=0.5,0.3

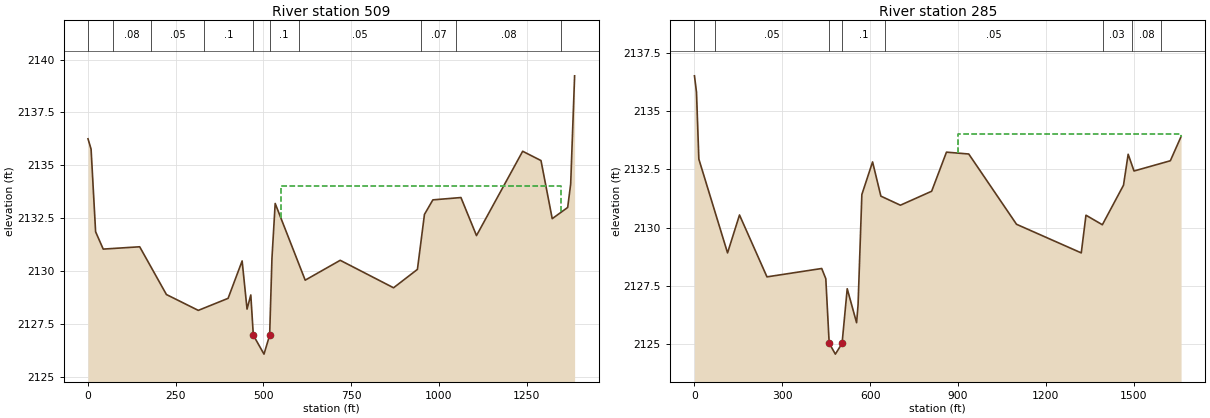
Type RM Length L Ch R = 1 ,509     ,224.5,224.5,224.5
BEGIN DESCRIPTION:
structure xs 1
END DESCRIPTION:
XS GIS Cut Line= 4
2231446.70154485452237.2952832262231427.66368039452190.965525599
2230984.56743929451690.7201509372230316.30182993451688.507350906
#Sta/Elev= 30
       0 2136.25     8.8 2135.76    21.7 2131.85    43.4 2131.03   147.3 2131.14
   223.5 2128.88   314.3 2128.13   399.2  2128.7   439.2 2130.47   453.2 2128.19
   463.9 2128.86   471.12126.955   501.5 2126.06   517.62126.953   524.2  2130.6
   533.4 2133.19   618.9 2129.56   718.7  2130.5   870.7  2129.2   938.7 2130.07
   958.7 2132.67   982.7 2133.36  1062.7 2133.47    1107 2131.67  1238.6 2135.66
  1290.8 2135.22  1322.8 2132.47  1366.8    2133  1375.4 2134.11  1386.6 2139.23
#Mann= 10 ,-1,0
       0     .06       0   70.09     .08       0  180.09     .05       0
  330.09      .1       0   471.1    .045       0   517.6      .1       0
  600.09     .05       0  948.35     .07       0 1048.35     .08       0
 1348.35     .06       0
#XS Ineff= 1 ,-1
     550  1347.1    2134
Permanent Ineff=
       F
Bank Sta=471.1,517.6
XS Rating Curve= 0 ,0
Exp/Cntr(USF)=0,0
Exp/Cntr=0.3,0.1

Type RM Length L Ch R = 1 ,285     ,,,
XS GIS Cut Line= 4
2231486.87304633452243.920158685 2231413.8506453451881.020953602
2231174.86824196451555.7393490472230287.53542953451526.972948644
#Sta/Elev= 30
       0 2136.52     6.9 2135.82      15 2132.94     113 2128.91   153.8 2130.54
   247.6 2127.88   434.5 2128.24   448.5  2127.8     460 2125.03   481.1 2124.56
     504 2125.02   521.6 2127.37   553.6 2125.91   558.6 2126.67   571.6 2131.42
   608.2 2132.82   636.5 2131.35   703.2 2130.96   809.9 2131.56   860.5 2133.24
   936.6 2133.16  1099.7 2130.14  1320.8 2128.91  1336.8 2130.53  1392.8 2130.12
    1465 2131.82  1480.9 2133.15  1500.9 2132.43  1624.9 2132.87  1661.6 2133.91
#Mann= 8 ,-1,0
       0     .06       0      70     .05       0     460    .045       0
     504      .1       0  650.17     .05       0 1393.81     .03       0
 1493.81     .08       0 1593.81     .07       0
#XS Ineff= 2 , 0
                             900            2134
Permanent Ineff=
       F       F
Bank Sta=460,504
XS Rating Curve= 0 ,0
Exp/Cntr(USF)=0,0
Exp/Cntr=0.3,0.1
LCMann Table=0

Chan Stop Cuts=-1
Use User Specified Reach Order=0
Composite Channel Slope=5